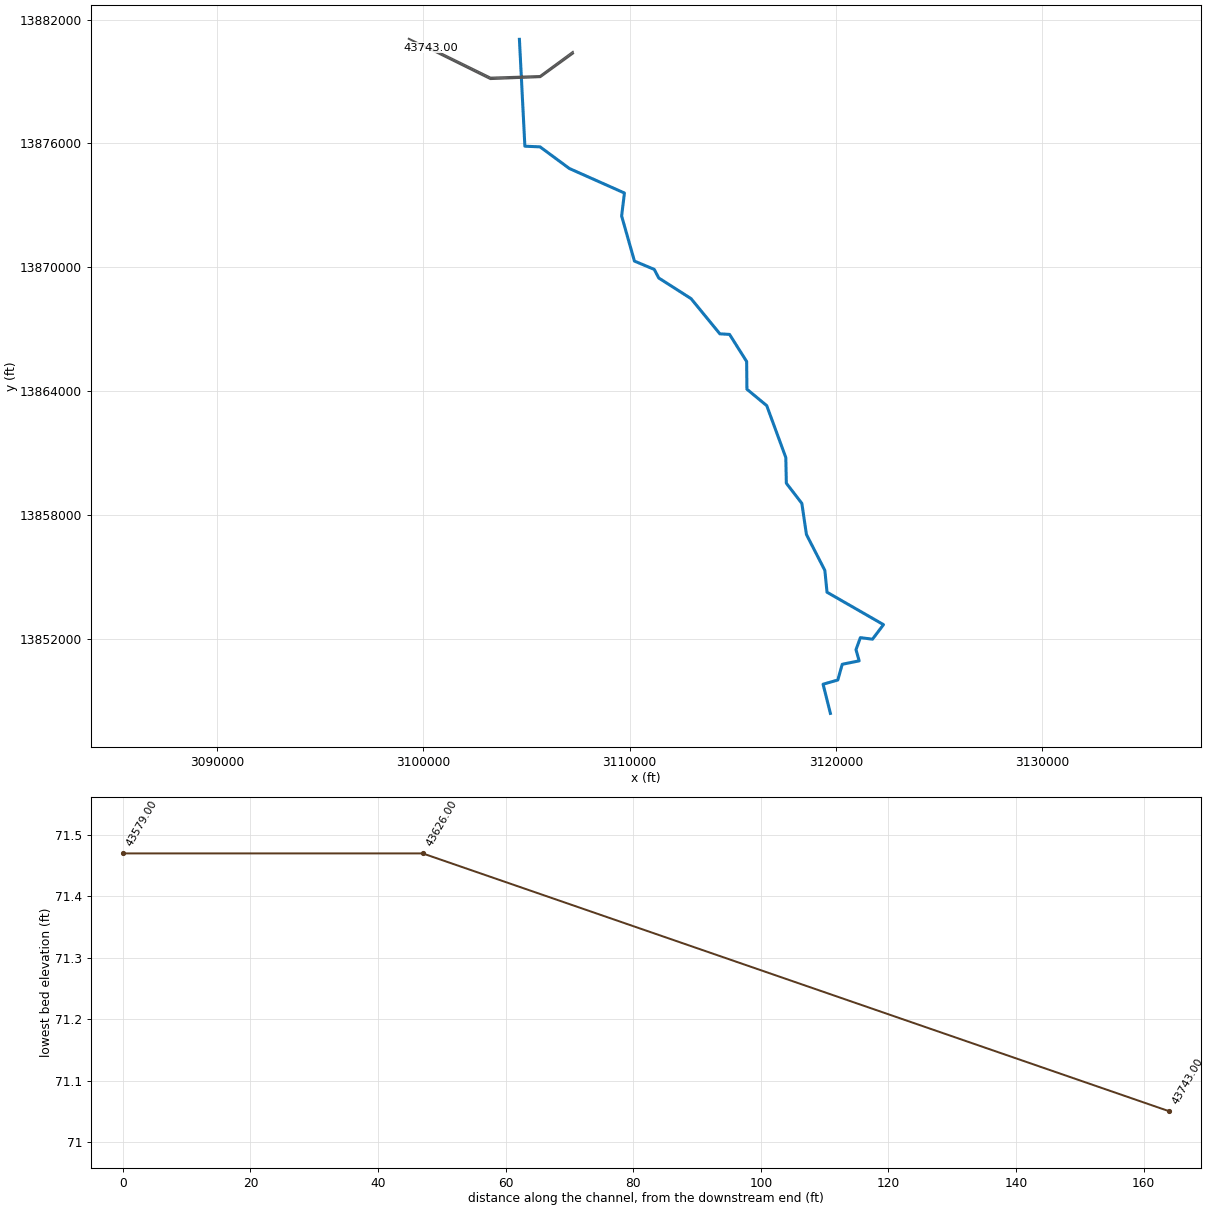
--- E101_00_00.prj (project) ---

Proj Title=E101-00-00
Current Plan=p03
Default Exp/Contr=.3,.1
English Units
Geom File=g01
Flow File=f01
Flow File=f02
Plan File=p01
Plan File=p03
Y Axis Title=Elevation
X Axis Title(PF)=Main Channel Distance
X Axis Title(XS)=Station
BEGIN DESCRIPTION:
White Oak Bayou Watershed
Little White Oak Bayou
HCFCD Unit E101-00-00
Flood Hazard Model
10, 2, 1, 0.2%
Filename E101-00-00
Prepared by:  Kelly Hay  DATE: March 10, 2004
Reviewed by:  _________  DATE:  __________________
STATUS (Final)
END DESCRIPTION:
DSS File=dss
DSS Export Rating Curves= 0
DSS Export Rating Curve Sorted= 0
DSS Export Volume Flow Curves= 0
DXF OffsetX= 0
DXF OffsetY= 0
DXF ScaleX= 1
DXF ScaleY= 10

--- E101_00_00.p03 (plan) ---

Plan Title=FEMA Effective Floodway 2013
Version=Version 3.0.1  May 2012
Short Identifier=Eff+LOMR FW
Geom File=g01
Flow File=f02
Subcritical Flow
K Sum by GR= 0
Std Step Tol= 0.01
Critical Tol= 0.01
Num of Std Step Trials= 20
Max Error Tol= 0.3
Flow Tol Ratio= 0.001
Split Flow NTrial= 30
Split Flow Tol= 0.02
Split Flow Ratio= 0.02
Log Output Level= 0
Friction Slope Method= 1
Unsteady Friction Slope Method= 2
Parabolic Critical Depth
Global Vel Dist= 0 , 0 , 0
Global Log Level= 0
CheckData=True
Encroach Param= 0 ,0,0, 3
Encroach River=E101-00-00
Encroach Reach=Reach - 1
Encroach Node=43743.00
       1    4663    5267       1    4663    5267
Encroach Node=43626.00
       1    4663    5267       1    4663    5267
Encroach Node=43602.00
       1    4663    5267       1    4663    5267
Encroach Node=43579.00
       1    4663    5267       1    4663    5267
Encroach Node=43547.00
       1    4663    5267       1    4663    5267
Encroach Node=43363.00
       1    4663    5267       1    4663    5267
Encroach Node=43257.00
       1    4663    5267       1    4663    5267
Encroach Node=43233.00
       1    4663    5267       1    4663    5267
Encroach Node=43207.00
       1    4663    5267       1    4663    5267
Encroach Node=42987.00
       1    4663    5267       1    4663    5267
Encroach Node=42896.00
       1    4870    5267       1    4870    5267
Encroach Node=42872.50
       1    4870    5267       1    4870    5267
Encroach Node=42847.00
       1    4870    5267       1    4870    5267
Encroach Node=42781.00
       1    4870    5267       1    4870    5267
Encroach Node=42628.00
       1    4870    5178       1    4870    5178
Encroach Node=42611.00
       1    4870    5178       1    4870    5178
Encroach Node=42590.00
       1    4797    5178       1    4797    5178
Encroach Node=42569.00
       1 4974.83 5152.38       1 4974.83 5152.38
Encroach Node=42158.00
       1    4594    5267       1    4594    5267
Encroach Node=41314.00
       1    4581    5267       1    4581    5267
Encroach Node=40713.00
       1    4509    5267       1    4509    5267
Encroach Node=39932.
       1  4971.5  5028.6       1  4971.5  5028.6
Encroach Node=39831
       1    4807    5176       1    4807    5176
Encroach Node=39622.50
       1    4807    5176       1    4807    5176
Encroach Node=39477.00
       1    4948    5050       1    4948    5050
Encroach Node=39361.
       1    4882    5110       1    4882    5110
Encroach Node=39016.00
       1    4807    5176       1    4807    5176
Encroach Node=38579.00
       1    4807    5176       1    4807    5176
Encroach Node=38471.00
       1    4807 5127.19       1    4807 5127.19
Encroach Node=38433.00
       1    4807 5127.19       1    4807 5127.19
Encroach Node=38394.00
       1    4755 5127.19       1    4755 5127.19
Encroach Node=38205.00
       1    4793    5110       1    4793    5110
Encroach Node=38062.00
       1    4754    5188       1    4754    5188
Encroach Node=38034.00
       1    4754    5188       1    4754    5188
Encroach Node=38013.00
       1    4754    5188       1    4754    5188
Encroach Node=37966.00
       1    4754    5188       1    4754    5188
Encroach Node=36718.00
       1    4800    5188       1    4800    5188
Encroach Node=36142.00
       1 4917.36 5088.36       1 4917.36 5088.36
Encroach Node=36083.00
       1  4987.8  5018.4       1  4987.8  5018.4
Encroach Node=36053.50
       1  4987.8  5029.1       1  4987.8  5029.1
Encroach Node=36024.00
       1  4987.8  5029.1       1  4987.8  5029.1
Encroach Node=35953.
       1    4979  5022.2       1    4979  5022.2
Encroach Node=35537.00
       1 4945.39 5045.89       1 4945.39 5045.89
Encroach Node=35225.00
       1  4972.5 5033.46       1  4972.5 5033.46
Encroach Node=34406.00
       1 4971.12    5048       1 4971.12    5048
Encroach Node=34325.00
       1    4960    5048       1    4960    5048
Encroach Node=34297.50
       1    4960    5048       1    4960    5048
Encroach Node=34266.00
       1    4960    5022       1    4960    5022
Encroach Node=34234.00
       1    4910    5025       1    4910    5025
Encroach Node=33983.00
       1    4860 5051.09       1    4860 5051.09
Encroach Node=33667.00
       1    4760 5089.65       1    4760 5089.65
Encroach Node=33575.00
       1    4660    5154       1    4660    5154
Encroach Node=33525.00
       1    4660    5154       1    4660    5154
Encroach Node=33473.00
       1    4660    5154       1    4660    5154
Encroach Node=33424.00
       1    4760    5054       1    4760    5054
Encroach Node=33031.00
       1    4660 5025.38       1    4660 5025.38
Encroach Node=32678.00
       1    4610    5117       1    4610    5117
Encroach Node=32570.00
       1    4500    5139       1    4500    5139
Encroach Node=32553.00
       1    4500    5161       1    4500    5161
Encroach Node=32536.00
       1    4500    5185       1    4500    5185
Encroach Node=32450.00
       1    4500    5284       1    4500    5284
Encroach Node=31975.00
       1    4500    5266       1    4500    5266
Encroach Node=30984.00
       1    4500    5272       1    4500    5272
Encroach Node=30651.00
       1    4500    5344       1    4500    5344
Encroach Node=30580.00
       1    4500    5500       1    4500    5500
Encroach Node=30552.00
       1    4500    5500       1    4500    5500
Encroach Node=30522.00
       1    4500    5500       1    4500    5500
Encroach Node=30466.00
       1    4500    5500       1    4500    5500
Encroach Node=29665.00
       1    4600    5400       1    4500    5500
Encroach Node=28715.00
       1    4525    5475       1    4500    5500
Encroach Node=28652.00
       1    4500    5500       1    4500    5500
Encroach Node=28639.50
       1    4500    5500       1    4500    5500
Encroach Node=28627.00
       1    4500    5500       1    4500    5500
Encroach Node=28589.00
       1    4500    5500       1    4500    5500
Encroach Node=28271.00
       1    4500    5400       1    4500    5400
Encroach Node=27838.00
       1    4500    5345       1    4500    5345
Encroach Node=27692.00
       1    4583    5346       1    4583    5346
Encroach Node=27650.50
       1    4583    5346       1    4583    5346
Encroach Node=27600.00
       1    4583    5346       1    4583    5346
Encroach Node=27458.00
       1    4650  5130.6       1    4650  5130.6
Encroach Node=27090.00
       1    4650  5130.6       1    4650  5130.6
Encroach Node=26937.00
       1    4807    5111       1    4807    5111
Encroach Node=26909.00
       1    4807    5111       1    4807    5111
Encroach Node=26884.00
       1    4737    5111       1    4737    5111
Encroach Node=26602.00
       1    4746    5225       1    4746    5225
Encroach Node=26304.00
       1    4709    5342       1    4709    5342
Encroach Node=26180.00
       1    3550    4200       1    3550    4200
Encroach Node=26140.50
       1    3550    4150       1    3550    4150
Encroach Node=26097.00
       1    3550    4120       1    3550    4120
Encroach Node=26016.00
       1    4850    5150       1    4850    5150
Encroach Node=25769.00
       1    4760    5365       1    4760    5365
Encroach Node=25306.00
       1    4750    5375       1    4750    5375
Encroach Node=25182.00
       1    4750    5375       1    4750    5375
Encroach Node=25137.00
       1    4745    5350       1    4745    5350
Encroach Node=25087.00
       1    4745    5350       1    4745    5350
Encroach Node=24940.00
       1    4745  5324.4       1    4745  5324.4
Encroach Node=24854.00
       1    4745 5325.35       1    4745 5325.35
Encroach Node=24808.00
       1    4745 5325.35       1    4745 5325.35
Encroach Node=24761.00
       1    4745 5325.35       1    4745 5325.35
Encroach Node=24693.00
       1    4745  5325.4       1    4745  5325.4
Encroach Node=24176.00
       1    4745  5263.9       1    4745  5263.9
Encroach Node=23475.00
       1  4761.6  5261.6       1  4761.6  5261.6
Encroach Node=23015.00
       1    4750    5250       1    4750    5250
Encroach Node=22928.00
       1 4750.75 5250.75       1 4750.75 5250.75
Encroach Node=22902.50
       1 4750.75 5250.75       1 4750.75 5250.75
Encroach Node=22873.00
       1 4750.75 5250.75       1 4750.75 5250.75
Encroach Node=22815.00
       1  4748.8  5248.8       1  4748.8  5248.8
Encroach Node=22303.00
       1 4842.25 5142.25       1 4842.25 5142.25
Encroach Node=21808.00
       1  4821.4  5055.2       1  4821.4  5055.2
Encroach Node=20818.00
       1    4869    5313       1    4869    5313
Encroach Node=20705.00
       1    4871    5325       1    4871    5325
Encroach Node=20688.00
       1    4871    5325       1    4871    5325
Encroach Node=20670.00
       1    4871    5325       1    4871    5325
Encroach Node=20611.00
       1    4857    5325       1    4857    5325
Encroach Node=20562.00
       1    4844    5362       1    4844    5362
Encroach Node=20513.00
       1    4844    5325       1    4844    5325
Encroach Node=20258.00
       1  4834.6    5325       1  4834.6    5325
Encroach Node=19806.00
       1 4778.55    5325       1 4778.55    5325
Encroach Node=19340.00
       1 4712.34    5325       1 4712.34    5325
Encroach Node=19205.00
       1 4692.77    5325       1 4692.77    5325
Encroach Node=18492.00
       1 3865.36 6789.46       1 3865.36 6789.46
Encroach Node=17777.00
       1 4891.34 5169.44       1 4891.34 5169.44
Encroach Node=17644.00
       1 4823.07 5169.44       1 4823.07 5169.44
Encroach Node=17621.00
       1 4823.07 5169.44       1 4823.07 5169.44
Encroach Node=17598.00
       1 4897.34 5169.44       1 4897.34 5169.44
Encroach Node=17565.00
       1 4823.07 5168.59       1 4823.07 5168.59
Encroach Node=16747.00
       1 4734.78 5321.85       1 4734.78 5321.85
Encroach Node=16410.00
       1  4698.3 5241.36       1  4698.3 5241.36
Encroach Node=16341.00
       1    4732 5196.66       1    4732 5196.66
Encroach Node=16318.00
       1    4745 5149.53       1    4745 5149.53
Encroach Node=16293.00
       1    4745 5149.53       1    4745 5149.53
Encroach Node=16220.
       1 4842.85    5165       1 4842.85    5165
Encroach Node=16143.00
       1 4743.15 5186.13       1 4743.15 5186.13
Encroach Node=16110.50
       1 4743.15 5182.48       1 4743.15 5182.48
Encroach Node=16074.00
       1 4743.15 5182.48       1 4743.15 5182.48
Encroach Node=15999.00
       1 4769.73  5138.1       1 4769.73  5138.1
Encroach Node=15374.00
       1 4922.66 5208.77       1 4922.66 5208.77
Encroach Node=14721.00
       1 4836.38  5159.2       1 4836.38  5159.2
Encroach Node=14637.00
       1 4814.85 5164.85       1 4814.85 5164.85
Encroach Node=14560.00
       14859.665 5164.85       14859.665 5164.85
Encroach Node=14482.00
       1 4904.48 5164.85       1 4904.48 5164.85
Encroach Node=14240.00
       1  4838.4  5119.9       1  4838.4  5119.9
Encroach Node=13919.00
       1 4838.65 5188.65       1 4838.65 5188.65
Encroach Node=13247.00
       1  4885.4  5092.9       1  4885.4  5092.9
Encroach Node=13164.00
       1  4915.3  5125.8       1  4915.3  5125.8
Encroach Node=12676.00
       1  4915.3  5125.8       1  4915.3  5125.8
Encroach Node=12177.00
       1  4915.3  5125.8       1  4915.3  5125.8
Encroach Node=12084.
       1  4919.8  5089.8       1  4919.8  5089.8
Encroach Node=11540.00
       1  4886.1  5098.3       1  4886.1  5098.3
Encroach Node=10539.00
       1  4927.9  5127.4       1  4927.9  5127.4
Encroach Node=10015.00
       1  4859.3  5192.5       1  4859.3  5192.5
Encroach Node=9905.000
       1  4877.8 5112.11       1  4877.8 5112.11
Encroach Node=9874.500
       1  4877.8  5112.4       1  4877.8  5112.4
Encroach Node=9845.000
       1  4877.8  5112.4       1  4877.8  5112.4
Encroach Node=9840.000
       1 4899.61 5112.21       1 4899.61 5112.21
Encroach Node=9829.500
       1 4899.61 5112.21       1 4899.61 5112.21
Encroach Node=9819.000
       1 4899.61 5112.21       1 4899.61 5112.21
Encroach Node=9750.000
       1  4888.9  5116.2       1  4888.9  5116.2
Encroach Node=9000.000
       1  4843.3 5150.15       1  4843.3 5150.15
Encroach Node=8469.000
       1 4888.89 5180.75       1 4888.89 5180.75
Encroach Node=7984.000
       1  4905.4  5164.3       1  4905.4  5164.3
Encroach Node=6838.000
       1 4752.22  5138.9       1 4752.22  5138.9
Encroach Node=5861.000
       1  4783.2  5153.6       1  4783.2  5153.6
Encroach Node=4720.000
       1  4832.9  5182.9       1  4832.9  5182.9
Encroach Node=4279.000
       1 4854.05 5154.05       1 4854.05 5154.05
Encroach Node=4130.000
       1 4866.05 5166.05       1 4866.05 5166.05
Encroach Node=4091.000
       1 4866.05 5166.05       1 4866.05 5166.05
Encroach Node=4050.000
       1 4866.05 5166.05       1 4866.05 5166.05
Encroach Node=3952.
       1  4896.3 5123.21       1  4896.3 5123.21
Encroach Node=3466.000
       1  4854.7  5154.7       1  4854.7  5154.7
Encroach Node=3300.
       1    4830    5160       1    4830    5160
Encroach Node=3203.000
       1 4822.55 5172.55       1 4822.55 5172.55
Encroach Node=2797.000
       1 4822.555140.605       1 4822.555140.605
Encroach Node=2389.000
       1 4822.55 5108.66       1 4822.55 5108.66
Encroach Node=2325.
       1 4822.55 5108.66       1 4822.55 5108.66
Encroach Node=1855.000
       1 4811.85 5161.85       1 4811.85 5161.85
Encroach Node=1126.
       1 4738.15 5263.15       1 4738.15 5263.15
Encroach Node=1070.000
       1 4738.15 5263.15       1 4738.15 5263.15
Encroach Node=1029.500
       1 4738.15 5263.15       1 4738.15 5263.15
Encroach Node=987.000
       1 4738.15 5263.15       1 4738.15 5263.15
Encroach Node=911.
       1    4772    5298       1    4772    5298
Encroach Node=756.
       1 4867.47    5338       1 4867.47    5338
Encroach Node=637.000
       1    4830  5355.3       1    4830  5355.3
Encroach Node=538.000
       1    4830  5355.3       1    4830  5355.3
Encroach Node=442.000
       1    4830  5355.3       1    4830  5355.3
Encroach Node=306.000
       1 4791.76 5491.38       1 4791.76 5491.38
Encroach Reach=E101-00-00_0003
Encroach Node=43743.00
       1    4663    5267       0       0       0
Encroach Node=43626.00
       1    4663    5267       0       0       0
Encroach Node=43602.00
       1    4663    5267       0       0       0
Encroach Node=43579.00
       1    4663    5267       0       0       0
Encroach Node=43547.00
       1    4663    5267       0       0       0
Encroach Node=43363.00
       1    4663    5267       0       0       0
Encroach Node=43257.00
       1    4663    5267       0       0       0
Encroach Node=43233.00
       1    4663    5267       0       0       0
Encroach Node=43207.00
       1    4663    5267       0       0       0
Encroach Node=42987.00
       1    4663    5267       0       0       0
Encroach Node=42896.00
       1    4870    5267       0       0       0
Encroach Node=42872.50
       1    4870    5267       0       0       0
Encroach Node=42847.00
       1    4870    5267       0       0       0
Encroach Node=42781.00
       1    4870    5267       0       0       0
Encroach Node=42628.00
       1    4870    5178       0       0       0
Encroach Node=42611.00
       1    4870    5178       0       0       0
Encroach Node=42590.00
       1    4797    5178       0       0       0
Encroach Node=42569.00
       1 4974.83 5152.38       0       0       0
Encroach Node=42158.00
       1    4594    5267       0       0       0
Encroach Node=41314.00
       1    4581    5267       0       0       0
Encroach Node=40713.00
       1    4509    5267       0       0       0
Encroach Node=39932.
       1  4971.5  5028.6       0       0       0
Encroach Node=39831
       1    4807    5176       0       0       0
Encroach Node=39622.50
       1    4807    5176       0       0       0
Encroach Node=39477.00
       1    4948    5050       0       0       0
Encroach Node=39361.
       1    4882    5110       0       0       0
Encroach Node=39016.00
       1    4807    5176       0       0       0
Encroach Node=38579.00
       1    4807    5176       0       0       0
Encroach Node=38471.00
       1    4807 5127.19       0       0       0
Encroach Node=38433.00
       1    4807 5127.19       0       0       0
Encroach Node=38394.00
       1    4755 5127.19       0       0       0
Encroach Node=38205.00
       1    4793    5110       0       0       0
Encroach Node=38062.00
       1    4754    5188       0       0       0
Encroach Node=38034.00
       1    4754    5188       0       0       0
Encroach Node=38013.00
       1    4754    5188       0       0       0
Encroach Node=37966.00
       1    4754    5188       0       0       0
Encroach Node=36718.00
       1    4800    5188       0       0       0
Encroach Node=36142.00
       1 4917.36 5088.36       0       0       0
Encroach Node=36083.00
       1  4987.8  5018.4       0       0       0
Encroach Node=36053.50
       1  4987.8  5029.1       0       0       0
Encroach Node=36024.00
       1  4987.8  5029.1       0       0       0
Encroach Node=35953.
       1    4979  5022.2       0       0       0
Encroach Node=35537.00
       1 4945.39 5045.89       0       0       0
Encroach Node=35225.00
       1  4972.5 5033.46       0       0       0
Encroach Node=34406.00
       1 4971.12    5048       0       0       0
Encroach Node=34325.00
       1    4960    5048       0       0       0
Encroach Node=34297.50
       1    4960    5048       0       0       0
Encroach Node=34266.00
       1    4960    5022       0       0       0
Encroach Node=34234.00
       1    4910    5025       0       0       0
Encroach Node=33983.00
       1    4860 5051.09       0       0       0
Encroach Node=33667.00
       1    4760 5089.65       0       0       0
Encroach Node=33575.00
       1    4660    5154       0       0       0
Encroach Node=33525.00
       1    4660    5154       0       0       0
Encroach Node=33473.00
       1    4660    5154       0       0       0
Encroach Node=33424.00
       1    4760    5054       0       0       0
Encroach Node=33031.00
       1    4660 5025.38       0       0       0
Encroach Node=32678.00
       1    4610    5117       0       0       0
Encroach Node=32570.00
       1    4500    5139       0       0       0
Encroach Node=32553.00
       1    4500    5161       0       0       0
Encroach Node=32536.00
       1    4500    5185       0       0       0
Encroach Node=32450.00
       1    4500    5284       0       0       0
Encroach Node=31975.00
       1    4500    5266       0       0       0
Encroach Node=30984.00
       1    4500    5272       0       0       0
Encroach Node=30651.00
       1    4500    5344       0       0       0
Encroach Node=30580.00
       1    4500    5500       0       0       0
Encroach Node=30552.00
       1    4500    5500       0       0       0
Encroach Node=30522.00
       1    4500    5500       0       0       0
Encroach Node=30466.00
       1    4500    5500       0       0       0
Encroach Node=29665.00
       1    4600    5400       0       0       0
Encroach Node=28715.00
       1    4525    5475       0       0       0
Encroach Node=28652.00
       1    4500    5500       0       0       0
Encroach Node=28639.50
       1    4500    5500       0       0       0
Encroach Node=28627.00
       1    4500    5500       0       0       0
Encroach Node=28589.00
       1    4500    5500       0       0       0
Encroach Node=28271.00
       1    4500    5400       0       0       0
Encroach Node=27838.00
       1    4500    5345       0       0       0
Encroach Node=27692.00
       1    4583    5346       0       0       0
Encroach Node=27650.50
       1    4583    5346       0       0       0
Encroach Node=27600.00
       1    4663    5346       0       0       0
Encroach Node=27458.00
       1    4750  5130.6       0       0       0
Encroach Node=27090.00
       1    4750  5130.6       0       0       0
Encroach Node=26937.00
       1    4837    5111       0       0       0
Encroach Node=26909.00
       1    4837    5111       0       0       0
Encroach Node=26884.00
       1    4870    5111       0       0       0
Encroach Node=26602.00
       1    4875    5175       0       0       0
Encroach Node=26304.00
       1    4885    5300       0       0       0
Encroach Node=26180.00
       1    3650    4150       0       0       0
Encroach Node=26140.50
       1    3620    4120       0       0       0
Encroach Node=26097.00
       1    3620    4120       0       0       0
Encroach Node=26016.00
       1    4850    5150       0       0       0
Encroach Node=25769.00
       1    4760    5365       0       0       0
Encroach Node=25306.00
       1    4750    5375       0       0       0
Encroach Node=25182.00
       1    4750    5375       0       0       0
Encroach Node=25137.00
       1    4745    5350       0       0       0
Encroach Node=25087.00
       1    4745    5350       0       0       0
Encroach Node=24940.00
       1    4745  5324.4       0       0       0
Encroach Node=24854.00
       1    4745 5325.35       0       0       0
Encroach Node=24808.00
       1    4745 5325.35       0       0       0
Encroach Node=24761.00
       1    4745 5325.35       0       0       0
Encroach Node=24693.00
       1    4745  5325.4       0       0       0
Encroach Node=24176.00
       1    4745  5263.9       0       0       0
Encroach Node=23475.00
       1  4761.6  5261.6       0       0       0
Encroach Node=23015.00
       1    4750    5250       0       0       0
Encroach Node=22928.00
       1 4750.75 5250.75       0       0       0
Encroach Node=22902.50
       1 4750.75 5250.75       0       0       0
Encroach Node=22873.00
       1 4750.75 5250.75       0       0       0
Encroach Node=22815.00
       1  4748.8  5248.8       0       0       0
Encroach Node=22303.00
       1 4842.25 5142.25       0       0       0
Encroach Node=21808.00
       1  4821.4  5055.2       0       0       0
Encroach Node=20818.00
       1    4869    5313       0       0       0
Encroach Node=20705.00
       1    4871    5325       0       0       0
Encroach Node=20688.00
       1    4871    5325       0       0       0
Encroach Node=20670.00
       1    4871    5325       0       0       0
Encroach Node=20611.00
       1    4857    5325       0       0       0
Encroach Node=20562.00
       1    4844    5362       0       0       0
Encroach Node=20513.00
       1    4844    5325       0       0       0
Encroach Node=20258.00
       1  4834.6    5325       0       0       0
Encroach Node=19806.00
       1 4778.55    5325       0       0       0
Encroach Node=19340.00
       1 4712.34    5325       0       0       0
Encroach Node=19205.00
       1 4692.77    5325       0       0       0
Encroach Node=18492.00
       1 3865.36 6789.46       0       0       0
Encroach Node=17777.00
       1 4891.34 5169.44       0       0       0
Encroach Node=17644.00
       1 4823.07 5169.44       0       0       0
Encroach Node=17621.00
       1 4823.07 5169.44       0       0       0
Encroach Node=17598.00
       1 4897.34 5169.44       0       0       0
Encroach Node=17565.00
       1 4823.07 5168.59       0       0       0
Encroach Node=16747.00
       1 4734.78 5321.85       0       0       0
Encroach Node=16410.00
       1  4698.3 5241.36       0       0       0
Encroach Node=16341.00
       1    4732 5196.66       0       0       0
Encroach Node=16318.00
       1    4745 5149.53       0       0       0
Encroach Node=16293.00
       1    4745 5149.53       0       0       0
Encroach Node=16220.
       1 4842.85    5165       0       0       0
Encroach Node=16143.00
       1 4743.15 5186.13       0       0       0
Encroach Node=16110.50
       1 4743.15 5182.48       0       0       0
Encroach Node=16074.00
       1 4743.15 5182.48       0       0       0
Encroach Node=15999.00
       1 4769.73  5138.1       0       0       0
Encroach Node=15374.00
       1 4922.66 5208.77       0       0       0
Encroach Node=14721.00
       1 4836.38  5159.2       0       0       0
Encroach Node=14637.00
       1 4814.85 5164.85       0       0       0
Encroach Node=14560.00
       14859.665 5164.85       0       0       0
Encroach Node=14482.00
       1 4904.48 5164.85       0       0       0
Encroach Node=14240.00
       1  4838.4  5119.9       0       0       0
Encroach Node=13919.00
       1 4838.65 5188.65       0       0       0
Encroach Node=13247.00
       1  4885.4  5092.9       0       0       0
Encroach Node=13164.00
       1  4915.3  5125.8       0       0       0
Encroach Node=12676.00
       1  4915.3  5125.8       0       0       0
Encroach Node=12177.00
       1  4915.3  5125.8       0       0       0
Encroach Node=12084.
       1  4919.8  5089.8       0       0       0
Encroach Node=11540.00
       1  4886.1  5098.3       0       0       0
Encroach Node=10539.00
       1  4927.9  5127.4       0       0       0
Encroach Node=10015.00
       1  4859.3  5192.5       0       0       0
Encroach Node=9905.000
       1  4877.8 5112.11       0       0       0
Encroach Node=9874.500
       1  4877.8  5112.4       0       0       0
Encroach Node=9845.000
       1  4877.8  5112.4       0       0       0
Encroach Node=9840.000
       1 4899.61 5112.21       0       0       0
Encroach Node=9829.500
       1 4899.61 5112.21       0       0       0
Encroach Node=9819.000
       1 4899.61 5112.21       0       0       0
Encroach Node=9750.000
       1  4888.9  5116.2       0       0       0
Encroach Node=9000.000
       1  4843.3 5150.15       0       0       0
Encroach Node=8469.000
       1 4888.89 5180.75       0       0       0
Encroach Node=7984.000
       1  4905.4  5164.3       0       0       0
Encroach Node=6838.000
       1 4752.22  5138.9       0       0       0
Encroach Node=5861.000
       1  4783.2  5153.6       0       0       0
Encroach Node=4720.000
       1  4832.9  5182.9       0       0       0
Encroach Node=4279.000
       1 4854.05 5154.05       0       0       0
Encroach Node=4130.000
       1 4866.05 5166.05       0       0       0
Encroach Node=4091.000
       1 4866.05 5166.05       0       0       0
Encroach Node=4050.000
       1 4866.05 5166.05       0       0       0
Encroach Node=3952.
       1  4896.3 5123.21       0       0       0
Encroach Node=3466.000
       1  4854.7  5154.7       0       0       0
Encroach Node=3300.
       1    4830    5160       0       0       0
Encroach Node=3203.000
       1 4822.55 5172.55       0       0       0
Encroach Node=2797.000
       1 4822.555140.605       0       0       0
Encroach Node=2389.000
       1 4822.55 5108.66       0       0       0
Encroach Node=2325.
       1 4822.55 5108.66       0       0       0
Encroach Node=1855.000
       1 4811.85 5161.85       0       0       0
Encroach Node=1126.
       1 4738.15 5263.15       0       0       0
Encroach Node=1070.000
       1 4738.15 5263.15       0       0       0
Encroach Node=1029.500
       1 4738.15 5263.15       0       0       0
Encroach Node=987.000
       1 4738.15 5263.15       0       0       0
Encroach Node=911.
       1    4772    5298       0       0       0
Encroach Node=756.
       1 4867.47    5338       0       0       0
Encroach Node=637.000
       1    4830  5355.3       0       0       0
Encroach Node=538.000
       1    4830  5355.3       0       0       0
Encroach Node=442.000
       1    4830  5355.3       0       0       0
Encroach Node=306.000
       1 4791.76 5491.38       0       0       0
BEGIN DESCRIPTION:
FEMA Effective 2013 + LOMR 11-06-2873P
END DESCRIPTION:
Computation Interval=1HOUR
Output Interval=1HOUR
Run HTab= 0
Run UNet= 0
Run PostProcess= 0
UNET Theta= 1
UNET ZTol= 0.02
UNET ZSATol= 0.1
UNET MxIter= 20
UNET MaxInSteps= 20
UNET DtIC= 0
UNET DtMin= 0
UNET MaxCRTS= 20
UNET WFStab= 2
UNET SFStab= 1
UNET WFX= 1
UNET SFX= 1
UNET Convert EG Bridges=-1
UNET Use Existing IB Tables=-1
Instantaneous Interval=1HOUR
DSS File=dss
Write IC File= 0
IC Time=0
Write Velocity= 0
Write Detailed= 0

--- E101_00_00.p01 (plan) ---

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Plan Title=FEMA Effective Multi-Profile 2013
Short Identifier=Eff+LOMR MP
Geom File=g01
Flow File=f01
Encroach Param=-1 ,0,0, 2

--- E101_00_00.f02 (steady flow) ---

Flow Title=Floodway
Version=Version 3.0.1  Mar 2001
Number of Profiles= 2
Profile Names=1PCT_100yr, 1PCTFloodway_100yrFW
River Rch & RM=E101-00-00,E101-00-00_0003       ,43743.00
    1530    1530
River Rch & RM=E101-00-00,E101-00-00_0003       ,43363.00
    1570    1570
River Rch & RM=E101-00-00,E101-00-00_0003       ,42987.00
    1650    1650
River Rch & RM=E101-00-00,E101-00-00_0003       ,42158.00
    1710    1710
River Rch & RM=E101-00-00,E101-00-00_0003       ,41314.00
    1760    1760
River Rch & RM=E101-00-00,E101-00-00_0003       ,40713.00
    1860    1860
River Rch & RM=E101-00-00,E101-00-00_0003       ,39477.00
    1960    1960
River Rch & RM=E101-00-00,E101-00-00_0003       ,38205.00
    2090    2090
River Rch & RM=E101-00-00,E101-00-00_0003       ,36718.00
    2206    2206
River Rch & RM=E101-00-00,E101-00-00_0003       ,35537.00
    2310    2310
River Rch & RM=E101-00-00,E101-00-00_0003       ,35225.00
    2590    2590
River Rch & RM=E101-00-00,E101-00-00_0003       ,34406.00
    2750    2750
River Rch & RM=E101-00-00,E101-00-00_0003       ,33983.00
    2870    2870
River Rch & RM=E101-00-00,E101-00-00_0003       ,33667.00
    2970    2970
River Rch & RM=E101-00-00,E101-00-00_0003       ,33424.00
    3140    3140
River Rch & RM=E101-00-00,E101-00-00_0003       ,33031.00
    3310    3310
River Rch & RM=E101-00-00,E101-00-00_0003       ,32678.00
    3410    3410
River Rch & RM=E101-00-00,E101-00-00_0003       ,32450.00
    3650    3650
River Rch & RM=E101-00-00,E101-00-00_0003       ,31975.00
    4199    4199
River Rch & RM=E101-00-00,E101-00-00_0003       ,30984.00
    4450    4450
River Rch & RM=E101-00-00,E101-00-00_0003       ,30466.00
    4860    4860
River Rch & RM=E101-00-00,E101-00-00_0003       ,29665.00
    5400    5400
River Rch & RM=E101-00-00,E101-00-00_0003       ,28715.00
    5430    5430
River Rch & RM=E101-00-00,E101-00-00_0003       ,28652.00
    5670    5670
River Rch & RM=E101-00-00,E101-00-00_0003       ,28271.00
    5950    5950
River Rch & RM=E101-00-00,E101-00-00_0003       ,27838.00
    6200    6200
River Rch & RM=E101-00-00,E101-00-00_0003       ,27458.00
    6580    6580
River Rch & RM=E101-00-00,E101-00-00_0003       ,26304.00
    6920    6920
River Rch & RM=E101-00-00,E101-00-00_0003       ,25306.00
    7050    7050
River Rch & RM=E101-00-00,E101-00-00_0003       ,24940.00
    7339    7339
River Rch & RM=E101-00-00,E101-00-00_0003       ,24176.00
    7860    7860
River Rch & RM=E101-00-00,E101-00-00_0003       ,22928.00
    8130    8130
River Rch & RM=E101-00-00,E101-00-00_0003       ,22303.00
    8350    8350
River Rch & RM=E101-00-00,E101-00-00_0003       ,21808.00
    8871    8871
River Rch & RM=E101-00-00,E101-00-00_0003       ,20705.00
    9050    9050
River Rch & RM=E101-00-00,E101-00-00_0003       ,19806.00
    9480    9480
River Rch & RM=E101-00-00,E101-00-00_0003       ,17644.00
    9828    9828
River Rch & RM=E101-00-00,E101-00-00_0003       ,15999.00
   10290   10290
River Rch & RM=E101-00-00,E101-00-00_0003       ,13919.00
   10850   10850
River Rch & RM=E101-00-00,E101-00-00_0003       ,11540.00
   11230   11230
River Rch & RM=E101-00-00,E101-00-00_0003       ,10015.00
   11487   11487
River Rch & RM=E101-00-00,E101-00-00_0003       ,9000.000
   12000   12000
River Rch & RM=E101-00-00,E101-00-00_0003       ,5861.000
   12410   12410
River Rch & RM=E101-00-00,E101-00-00_0003       ,3466.000
   12967   12967
Boundary for River Rch & Prof#=E101-00-00,E101-00-00_0003       , 1
Up Type= 0
Dn Type= 3
Dn Slope=.000039
Boundary for River Rch & Prof#=E101-00-00,E101-00-00_0003       , 2
Up Type= 0
Dn Type= 1
Dn Known WS=35.29
DSS Import GetInterval= 0
DSS Import GetPeak= 0
DSS Import FillOption= 0

--- E101_00_00.f01 (steady flow) ---

Flow Title=FEMA Effective June 2007
Version=Version 3.0.1  Mar 2001
Number of Profiles= 4
Profile Names=10PCT_10yr, 2PCT_50yr, 1PCT_100yr, 0.2PCT_500yr
River Rch & RM=E101-00-00,E101-00-00_0003       ,43743.00
     840    1320    1530    2090
River Rch & RM=E101-00-00,E101-00-00_0003       ,43363.00
     880    1340    1570    2210
River Rch & RM=E101-00-00,E101-00-00_0003       ,42987.00
     970    1400    1650    2500
River Rch & RM=E101-00-00,E101-00-00_0003       ,42158.00
    1000    1450    1710    2570
River Rch & RM=E101-00-00,E101-00-00_0003       ,41314.00
    1030    1490    1760    2630
River Rch & RM=E101-00-00,E101-00-00_0003       ,40713.00
    1080    1580    1860    2740
River Rch & RM=E101-00-00,E101-00-00_0003       ,39477.00
    1130    1670    1960    2860
River Rch & RM=E101-00-00,E101-00-00_0003       ,38205.00
    1200    1790    2090    3010
River Rch & RM=E101-00-00,E101-00-00_0003       ,36718.00
    1258    1886    2206    3137
River Rch & RM=E101-00-00,E101-00-00_0003       ,35537.00
    1320    1980    2310    3260
River Rch & RM=E101-00-00,E101-00-00_0003       ,35225.00
    1520    2250    2590    3620
River Rch & RM=E101-00-00,E101-00-00_0003       ,34406.00
    1630    2400    2750    3820
River Rch & RM=E101-00-00,E101-00-00_0003       ,33983.00
    1720    2520    2870    3970
River Rch & RM=E101-00-00,E101-00-00_0003       ,33667.00
    1790    2620    2970    4090
River Rch & RM=E101-00-00,E101-00-00_0003       ,33424.00
    1910    2780    3140    4300
River Rch & RM=E101-00-00,E101-00-00_0003       ,33031.00
    2020    2940    3310    4500
River Rch & RM=E101-00-00,E101-00-00_0003       ,32678.00
    2100    3050    3410    4630
River Rch & RM=E101-00-00,E101-00-00_0003       ,32450.00
    2270    3280    3650    4910
River Rch & RM=E101-00-00,E101-00-00_0003       ,31975.00
    2680    3827    4199    5565
River Rch & RM=E101-00-00,E101-00-00_0003       ,30984.00
    2860    4020    4450    5950
River Rch & RM=E101-00-00,E101-00-00_0003       ,30466.00
    3150    4340    4860    6610
River Rch & RM=E101-00-00,E101-00-00_0003       ,29665.00
    3540    4750    5400    7480
River Rch & RM=E101-00-00,E101-00-00_0003       ,28715.00
    3570    4770    5430    7530
River Rch & RM=E101-00-00,E101-00-00_0003       ,28652.00
    3740    4950    5670    7920
River Rch & RM=E101-00-00,E101-00-00_0003       ,28271.00
    3950    5160    5950    8380
River Rch & RM=E101-00-00,E101-00-00_0003       ,27838.00
    4138    5349    6200    8806
River Rch & RM=E101-00-00,E101-00-00_0003       ,27458.00
    4470    5720    6580    9280
River Rch & RM=E101-00-00,E101-00-00_0003       ,26304.00
    4770    6060    6920    9700
River Rch & RM=E101-00-00,E101-00-00_0003       ,25306.00
    4890    6190    7050    9860
River Rch & RM=E101-00-00,E101-00-00_0003       ,24940.00
    5150    6475    7339   10210
River Rch & RM=E101-00-00,E101-00-00_0003       ,24176.00
    5570    7020    7860   10800
River Rch & RM=E101-00-00,E101-00-00_0003       ,22928.00
    5800    7310    8130   11110
River Rch & RM=E101-00-00,E101-00-00_0003       ,22303.00
    5980    7540    8350   11370
River Rch & RM=E101-00-00,E101-00-00_0003       ,21808.00
    6413    8098    8871   11947
River Rch & RM=E101-00-00,E101-00-00_0003       ,20705.00
    6530    8250    9050   12210
River Rch & RM=E101-00-00,E101-00-00_0003       ,19806.00
    6800    8620    9480   12860
River Rch & RM=E101-00-00,E101-00-00_0003       ,17644.00
    7026    8912    9828   13380
River Rch & RM=E101-00-00,E101-00-00_0003       ,15999.00
    7290    9330   10290   14040
River Rch & RM=E101-00-00,E101-00-00_0003       ,13919.00
    7600    9820   10850   14830
River Rch & RM=E101-00-00,E101-00-00_0003       ,11540.00
    7800   10160   11230   15370
River Rch & RM=E101-00-00,E101-00-00_0003       ,10015.00
    7940   10385   11487   15730
River Rch & RM=E101-00-00,E101-00-00_0003       ,9000.000
    8180   10820   12000   16470
River Rch & RM=E101-00-00,E101-00-00_0003       ,5861.000
    8360   11160   12410   17060
River Rch & RM=E101-00-00,E101-00-00_0003       ,3466.000
    8616   11630   12967   17865
Boundary for River Rch & Prof#=E101-00-00,E101-00-00_0003       , 1
Up Type= 0
Dn Type= 3
Dn Slope=.000052
Boundary for River Rch & Prof#=E101-00-00,E101-00-00_0003       , 2
Up Type= 0
Dn Type= 3
Dn Slope=.000046
Boundary for River Rch & Prof#=E101-00-00,E101-00-00_0003       , 3
Up Type= 0
Dn Type= 3
Dn Slope=.000039
Boundary for River Rch & Prof#=E101-00-00,E101-00-00_0003       , 4
Up Type= 0
Dn Type= 3
Dn Slope=.000025
DSS Import GetInterval= 0
DSS Import GetPeak= 0
DSS Import FillOption= 0

--- E101_00_00.g01 (geometry) ---

Geom Title=E101-00-00
Version=Version 3.0.1  May 2012

River Reach=E101-00-00      ,E101-00-00_0003
Reach XY= 30
      3104655.85     13881039.86      3104920.02     13875860.92
       3105656.5       13875829.      3107077.25       13874780.
      3109746.22     13873592.29      3109610.44     13872478.66
      3110231.46     13870292.98      3111194.42     13869889.28
       3111409.3      13869474.6        3112976.       13868473.
      3114373.15     13866767.02      3114841.47     13866741.05
       3115670.9     13865425.87      3115684.31     13864084.24
      3116645.45     13863286.09      3117569.61     13860771.27
       3117594.6     13859527.33        3118347.      13858550.5
      3118569.43     13857041.22      3119462.68     13855301.83
       3119567.2     13854244.82      3122305.07     13852673.32
      3121770.91     13851968.41      3121185.84     13852043.93
      3120971.69     13851461.69        3121125.       13850919.
      3120304.18     13850751.92      3120090.16     13849990.29
      3119375.84     13849785.84      3119731.01      13848373.1

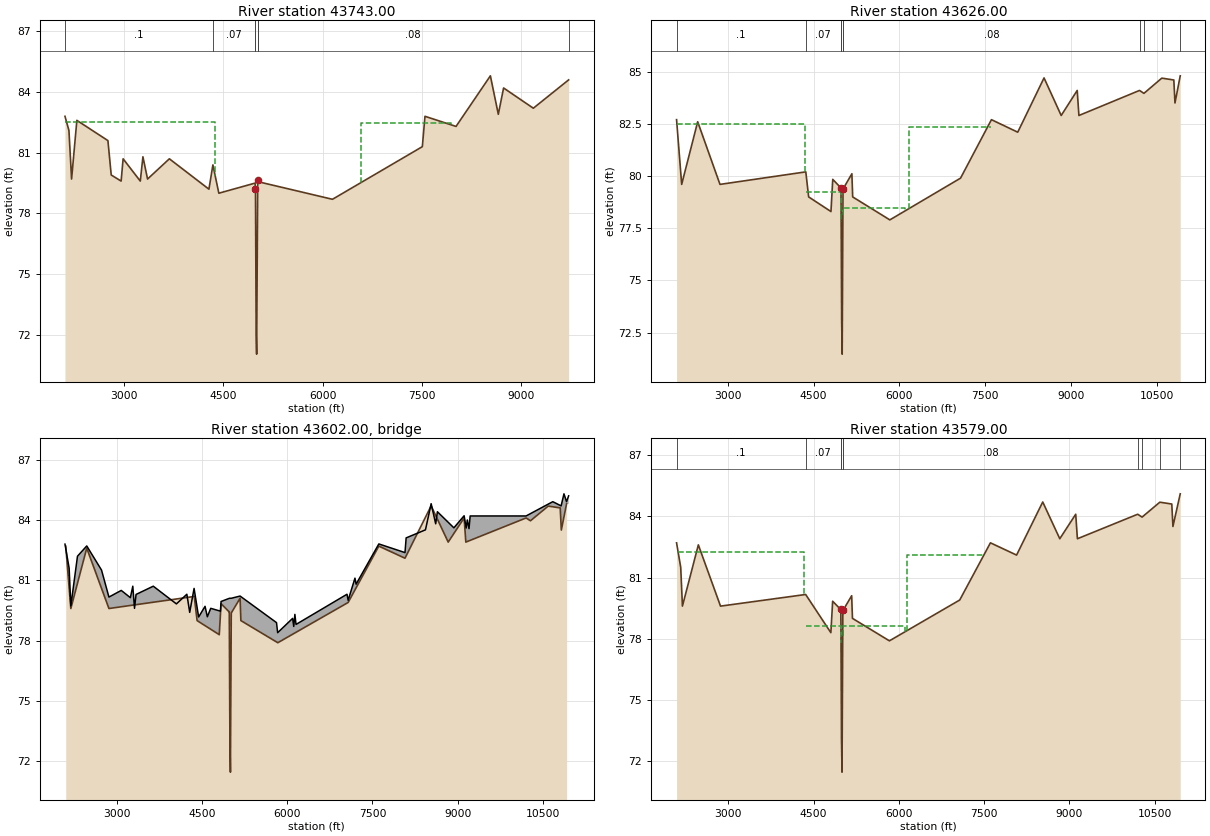
Type RM Length L Ch R = 1 ,43743.00,109.6,117,117.2
BEGIN DESCRIPTION:
Cross Section Xsec 34f
END DESCRIPTION:
XS GIS Cut Line= 4
      3107252.88     13880456.02      3105650.01     13879278.13
      3103261.21     13879199.62      3100347.86     13880627.64
#Sta/Elev= 30
  2100.9    82.8  2160.9    82.1  2200.9    79.7  2280.9    82.6  2750.9    81.6
  2800.9    79.9  2950.9    79.6  2980.9    80.7  3240.9    79.6  3280.9    80.8
  3350.9    79.7  3680.9    80.7    4280    79.2    4340    80.4    4430      79
    4978    79.5  4984.5   79.23    4995   72.02    5002   71.05  5018.5   79.63
  5022.3   79.57    6150    78.7  7510.1    81.3  7550.1    82.8  8020.1    82.3
  8540.1    84.8  8660.1    82.9  8740.1    84.2  9190.1    83.2  9724.6    84.6
#Mann= 7 ,-1 , 0
  2100.9      .1       0    4340     .07       0    4978     .04       0
  4984.5    .045       0  5018.5     .04       0  5022.3     .08       0
  9724.6      .1       0
#XS Ineff= 2 ,-1
  2100.9 4376.67   82.52 6576.83 7944.84   82.48
Permanent Ineff=
       F       F
Bank Sta=4984.5,5018.5
XS Rating Curve= 0
Exp/Cntr=.5,.3

Type RM Length L Ch R = 1 ,43626.00,52.1,47,46.8
BEGIN DESCRIPTION:
RITTENHOUSE u/s
Upstream Section of Bridge/Culvert/Weir
END DESCRIPTION:
XS GIS Cut Line= 4
      3107260.4313880388.0200287      3105664.61     13879239.41
      3103249.63     13879145.95      3099285.61 13881088.764504
#Sta/Elev= 30
    2105    82.7  2194.4    79.6  2474.4    82.6  2864.4    79.6  4365.3    80.2
  4415.3      79  4805.3    78.3  4836.9   79.84  4976.9   79.44  4981.1   79.44
  4992.4   73.09  5001.6   71.47  5016.3   79.39  5021.3    79.4  5171.4   80.11
  5185.3      79  5835.3    77.9  7072.1    79.9  7612.1    82.7  8072.1    82.1
  8532.1    84.7  8832.1    82.9  9112.1    84.1  9142.1    82.9   10202    84.1
 10279.3   83.96 10591.9   84.69 10802.1    84.6 10822.1    83.5   10914    84.8
#Mann= 10 ,-1 , 0
    2105      .1       0  4365.3     .07       0  4976.9     .04       0
  4981.1    .045       0  5016.3     .04       0  5021.3     .08       0
   10202     .08       0 10279.3     .05       0 10591.9     .07       0
   10914      .1       0
#XS Ineff= 4 ,-1
    2105 4356.19    82.5 6168.64 7602.84   82.36 4371.95    4984   79.22
    5014 6105.59   78.48
Permanent Ineff=
       F       F       F       F
Bank Sta=4981.1,5016.3
XS Rating Curve= 0
Exp/Cntr=.5,.3

Type RM Length L Ch R = 3 ,43602.00,,,
BEGIN DESCRIPTION:
RITTENHOUSE
Structure ID: E101-00-00-34
END DESCRIPTION:
Bridge Culvert--1,0,-1,-1, 0
Deck Dist Width WeirC Skew NumUp NumDn MinLoCord MaxHiCord MaxSubmerge Is_Ogee
10,28,2.6,0, 60, 60, , , .95, 0, ,,,
  2091.3  2164.4  2194.4  2311.3  2474.4  2734.4  2864.4  3081.3  3241.3  3284.4
  3314.4  3341.3  3644.4  4051.3  4235.3  4285.3  4362.2  4442.2  4555.3  4595.3
  4655.3    4826  4836.9 4984.91 4985.09  4985.2 5011.89    5012  5012.1  5016.3
  5171.4  5812.2  5832.2  6095.3  6115.3  6135.3  6155.3  7052.1  7072.1  7192.1
  7212.1  7612.1  8072.1  8092.1  8432.1  8532.1  8612.1  8642.1  8932.1  9112.1
  9148.2  9168.2  9198.2  9218.2   10202 10672.1 10818.2 10868.2 10913.8 10950.6
    82.8   81.61   79.73    82.2   82.71   81.51   80.17    80.5   80.14   80.71
   79.61    80.3   80.71   79.83   80.31   79.41    80.6   79.18   79.71   79.19
   79.61   79.47   79.95   80.11   80.11   80.11   80.11   80.11   80.11   80.11
   80.22    78.9    78.4   79.11   78.71   79.31   78.81   80.31   80.01   81.11
   80.81   82.81   82.38   83.11   83.51   84.81   83.81   84.41   83.61   84.21
    83.6      84   83.57    84.2    84.2   84.91    84.7    85.3   84.91    85.2
                                                                                
                                                                                
                                   76.74   78.71   78.69   76.58    76.4
                                                                                
                                                                                
                                                                                
  2091.3  2164.4  2194.4  2311.3  2474.4  2734.4  2864.4  3081.3  3241.3  3284.4
  3314.4  3341.3  3644.4  4051.3  4235.3  4285.3  4362.2  4442.2  4555.3  4595.3
  4655.3    4826  4836.9 4984.91 4985.09  4985.2 5011.89    5012  5012.1  5016.3
  5171.4  5812.2  5832.2  6095.3  6115.3  6135.3  6155.3  7052.1  7072.1  7192.1
  7212.1  7612.1  8072.1  8092.1  8432.1  8532.1  8612.1  8642.1  8932.1  9112.1
  9148.2  9168.2  9198.2  9218.2   10202 10672.1 10818.2 10868.2 10913.8 10950.6
    82.8   81.61   79.73    82.2   82.71   81.51   80.17    80.5   80.14   80.71
   79.61    80.3   80.71   79.83   80.31   79.41    80.6   79.18   79.71   79.19
   79.61   79.47   79.95   80.11   80.11   80.11   80.11   80.11   80.11   80.11
   80.22    78.9    78.4   79.11   78.71   79.31   78.81   80.31   80.01   81.11
   80.81   82.81   82.38   83.11   83.51   84.81   83.81   84.41   83.61   84.21
    83.6      84   83.57    84.2    84.2   84.91    84.7    85.3   84.91    85.2
                                                                                
                                                                                
                                   76.74   78.71   78.69   76.58    76.4
                                                                                
                                                                                
                                                                                
BR Coef= 1 , 1 , 0 ,1.25, 0 ,,,.8,0,2,0,
WSPro=,,,, 1 ,,,, 0 ,,,, 0 ,,,,-1 ,-1 ,-1 , 0 , 0 , 0 , 0 , 0
BC Design=,, 0 ,, 0 ,,,,,,
BC HTab HWMax=85.1

Type RM Length L Ch R = 1 ,43579.00,42.9,32,31.9
BEGIN DESCRIPTION:
RITTENHOUSE
Downstream Section of Bridge/Culvert/Weir
END DESCRIPTION:
XS GIS Cut Line= 4
      3107277.18      13880353.1      3105675.22      13879192.1
      3103246.33      13879098.1      3099276.61     13881059.94
#Sta/Elev= 30
  2091.3    82.7  2164.4    81.5  2194.4    79.6  2474.4    82.6  2864.4    79.6
  4362.2   80.17  4805.3    78.3  4836.9   79.84  4976.9   79.44  4981.1   79.44
  4992.4   73.09  5001.6   71.47  5016.3   79.39  5021.3    79.4  5171.4   80.11
  5185.3      79  5835.3    77.9  7072.1    79.9  7612.1    82.7  8072.1    82.1
  8532.1    84.7  8832.1    82.9  9112.1    84.1  9142.1    82.9   10202    84.1
 10279.3   83.96 10591.9   84.69 10802.1    84.6 10822.1    83.5 10950.6    85.1
#Mann= 10 ,-1 , 0
  2091.3      .1       0  4362.2     .07       0  4976.9     .04       0
  4981.1    .045       0  5016.3     .04       0  5021.3     .08       0
   10202     .08       0 10279.3     .05       0 10591.9     .07       0
 10950.6      .1       0
#XS Ineff= 4 ,-1
 2114.97 4324.67   82.25 6137.12 7500.39   82.12    5014 6113.48   78.64
 4371.95    4984   78.64
Permanent Ineff=
       F       F       F       F
Bank Sta=4981.1,5016.3
XS Rating Curve= 0
Exp/Cntr=.5,.3