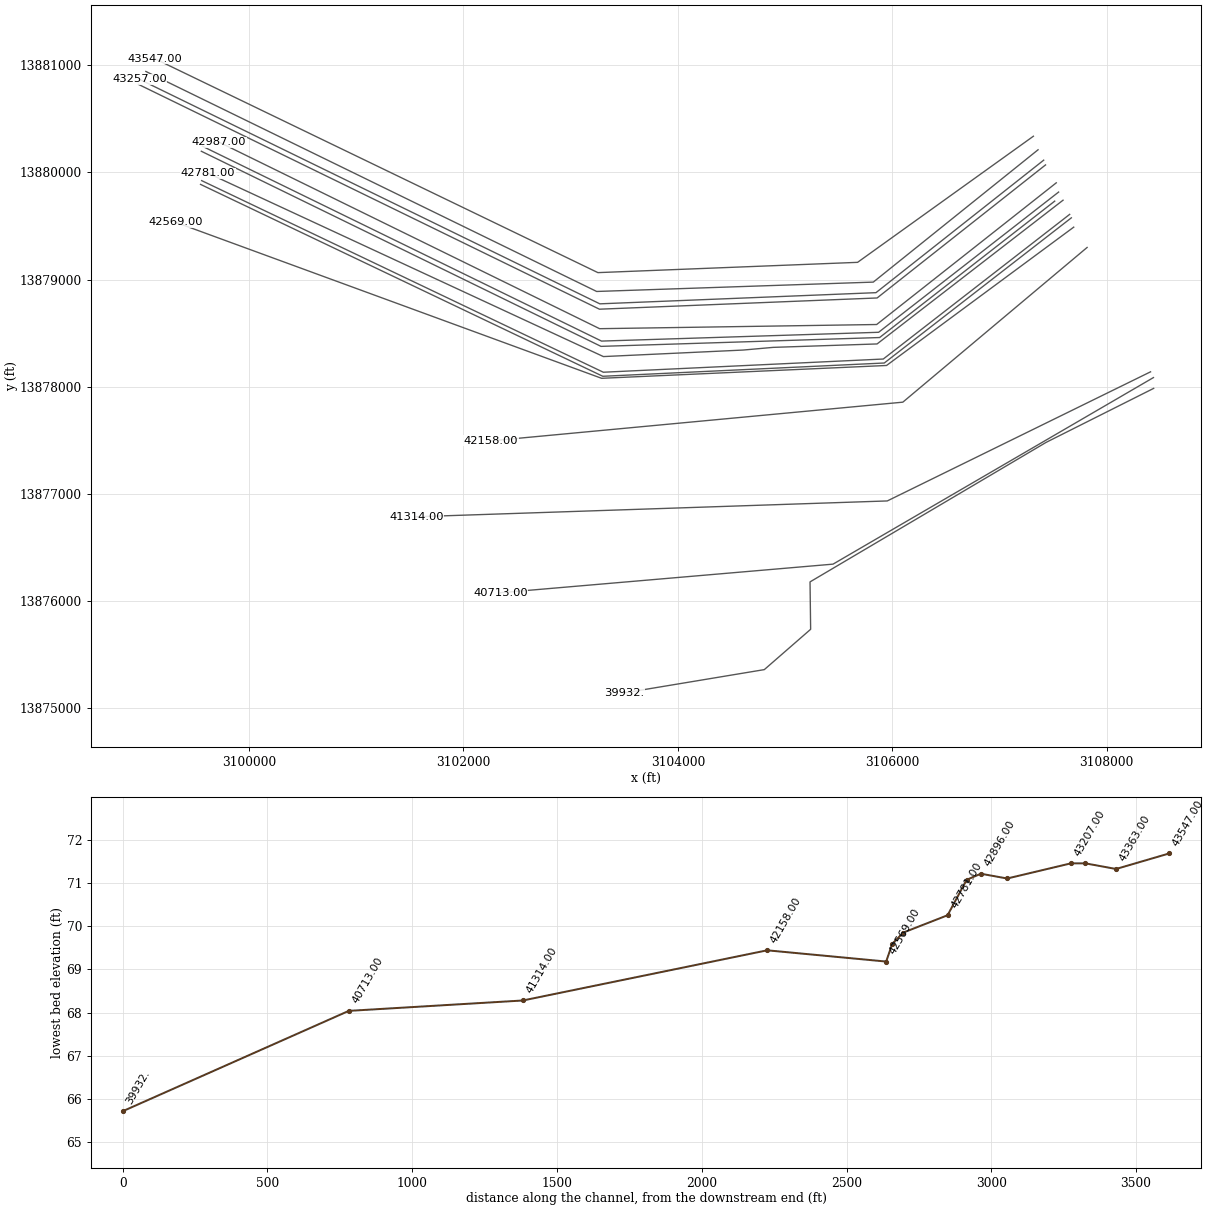
HEC-RAS study E101_00_00.prj: E101-00-00

--- E101_00_00.g01 (geometry) --- (continued)

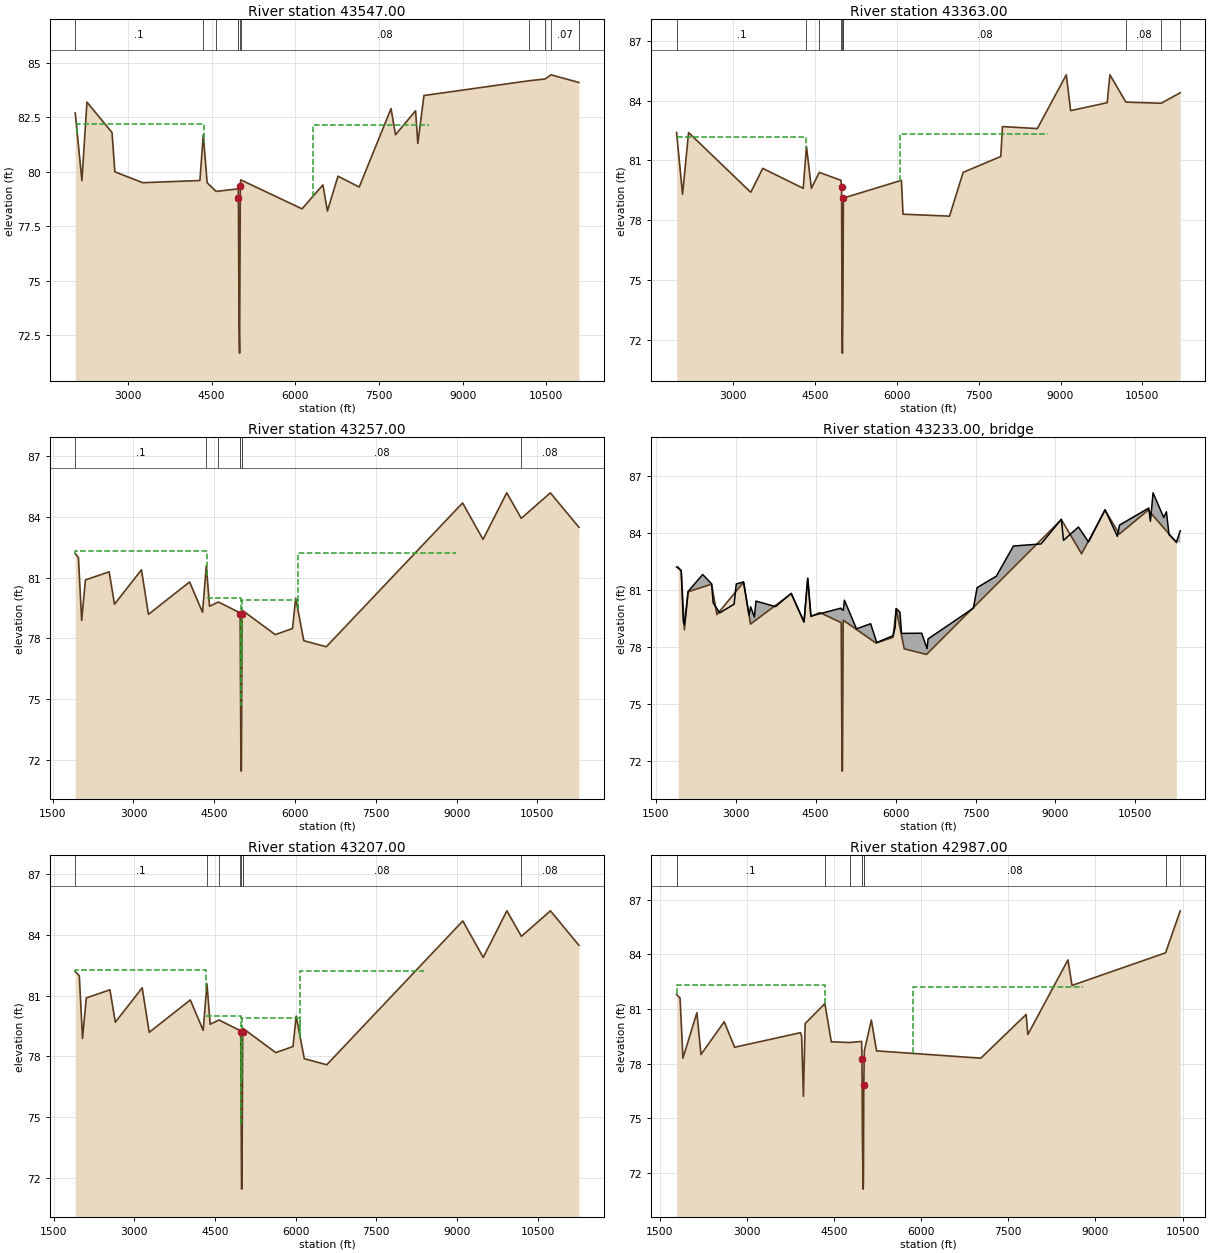
Type RM Length L Ch R = 1 ,43547.00,223.7,184,182.6
BEGIN DESCRIPTION:
Cross Section Xsec 34e
END DESCRIPTION:
XS GIS Cut Line= 4
       3107316.1     13880337.48      3105675.99     13879161.04
      3103253.93     13879065.14      3099123.74     13881059.22
#Sta/Elev= 30
  2057.5    82.7  2177.5    79.6  2267.5    83.2  2717.5    81.8  2767.5      80
  3267.5    79.5  4291.7    79.6  4351.7    81.7  4421.7    79.5  4580.6    79.1
  4979.1   79.22  4981.6   78.82  4992.7   72.87  5002.8   71.68  5015.6   79.37
  5023.7   79.63  6121.7    78.3    6496    79.4    6576    78.2    6766    79.8
    7146    79.3    7716    82.9    7796    81.7    8156    82.8    8196    81.3
    8306    83.5 10192.5   84.18 10479.1   84.26 10581.7   84.45 11082.3    84.1
#Mann= 11 ,-1 , 0
  2057.5      .1       0  4351.7     .08       0  4580.6     .07       0
  4979.1     .04       0  4981.6    .045       0  5015.6     .04       0
  5023.7     .08       0 10192.5     .08       0 10479.1     .05       0
 10581.7     .07       0 11082.3      .1       0
#XS Ineff= 2 ,-1
 2094.56 4364.07    82.2 6310.48 8390.86   82.17
Permanent Ineff=
       F       F
Bank Sta=4981.6,5015.6
XS Rating Curve= 0
Exp/Cntr=.3,.1

Type RM Length L Ch R = 1 ,43363.00,105.9,106,114
BEGIN DESCRIPTION:
Cross Section Xsec 34d
END DESCRIPTION:
XS GIS Cut Line= 4
      3107359.57     13880211.03      3105822.67      13878976.7
      3103242.17     13878889.39      3099037.42     13880941.51
#Sta/Elev= 30
  1961.8    82.4  2071.8    79.3  2181.8    82.4  3321.8    79.4  3541.8    80.6
    4283    79.6    4343    81.7    4433    79.6  4577.9    80.4  4976.1      80
  4986.5   79.66  4995.4   72.23  5001.5   71.32  5011.2   73.73  5019.6    79.1
  5021.3   79.11    6083      80    6113    78.3    6965    78.2    7215    80.4
    7905    81.2    7935    82.7    8575    82.6    9105    85.3    9185    83.5
    9855    83.9    9905    85.3 10197.8   83.93 10843.8   83.87 11193.8    84.4
#Mann= 10 ,-1 , 0
  1961.8      .1       0    4343     .08       0  4577.9     .07       0
  4976.1     .04       0  4986.5    .045       0  5019.6     .04       0
  5021.3     .08       0 10197.8     .08       0 10843.8     .07       0
 11193.8      .1       0
#XS Ineff= 2 ,-1
 6061.47 8765.96   82.33  1961.8 4340.43   82.18
Permanent Ineff=
       F       F
Bank Sta=4986.5,5019.6
XS Rating Curve= 0
Exp/Cntr=.5,.3

Type RM Length L Ch R = 1 ,43257.00,49.8,50,52.9
BEGIN DESCRIPTION:
GRANVILLE u/s
Upstream Section of Bridge/Culvert/Weir
END DESCRIPTION:
XS GIS Cut Line= 4
      3107412.19      13880114.2      3105847.58     13878878.22
      3103271.93     13878774.04      3098976.64      13880868.8
#Sta/Elev= 30
    1919   82.19  1978.6   81.99  2038.6   78.89  2108.6   80.89  2548.6   81.29
  2648.6   79.69  3148.6   81.39  3278.6   79.19  4042.5   80.79  4282.5   79.29
  4352.5   81.59  4412.5   79.59    4577    79.8    4975   79.27  4980.6    79.2
  4996.1   71.45  5003.8   71.47  5017.6   79.23  5020.7   79.39  5632.5   78.19
  5952.5   78.49  6012.5   79.99  6162.5   77.89  6580.3   77.59  9110.3   84.69
  9490.3   82.89  9930.3   85.19 10199.7   83.93 10740.3   85.19 11269.6   83.49
#Mann= 8 ,-1 , 0
    1919      .1       0  4352.5     .08       0    4577     .07       0
    4975     .04       0  4980.6    .045       0  5017.6     .04       0
  5020.7     .08       0 10199.7     .08       0
#XS Ineff= 4 ,-1
    1919 4368.79   82.34 4368.79 4989.69      80  5013.4 6052.01    79.9
 6052.01 8983.45   82.24
Permanent Ineff=
       F       F       F       F
Bank Sta=4980.6,5017.6
XS Rating Curve= 0
Exp/Cntr=.5,.3

Type RM Length L Ch R = 3 ,43233.00,,,
BEGIN DESCRIPTION:
GRANVILLE
Structure ID: E101-00-00-33
END DESCRIPTION:
Bridge Culvert--1,0,-1,-1, 0
Deck Dist Width WeirC Skew NumUp NumDn MinLoCord MaxHiCord MaxSubmerge Is_Ogee
10,28,2.6,0, 60, 60, , , .95, 0, ,,,
  1891.5  1978.6  2018.6  2038.6  2108.6  2381.5  2548.6  2578.6  2701.5  2971.5
  3011.5  3148.6  3251.5  3281.5  3351.5  3381.5  3748.6  4042.5  4282.5  4352.5
  4412.5    4975  4980.6 4986.69  4986.8 5013.29  5013.4  5020.7  5040.2  5267.4
  5532.5  5647.4  5952.5  5992.5  6012.5  6082.5  6112.5  6490.3  6591.4  6610.3
  7460.3  7530.3  7890.3  8211.4  8730.3  9110.3  9151.4  9431.4  9620.3  9930.3
 10161.4 10201.4 10751.4 10781.4 10831.4 11031.4 11081.4 11131.4 11269.2   11341
    82.2   82.01   79.31   79.16   80.91    81.8   81.31   80.31   79.78   80.24
    81.3   81.41   79.67    80.1   79.56    80.4   80.11   80.81   79.31   81.61
   79.61   80.03      80   79.97   79.97   79.93   79.93   79.92   80.45   78.94
   79.21   78.22   78.58   79.01   80.01   79.81    78.7   78.71    77.9   78.41
   80.03   81.11   81.71    83.3   83.41   84.71    83.6    84.3   83.51   85.21
   83.81    84.4    85.3    84.6    86.1    84.8    85.1    83.9   83.51    84.1
                                                                                
                                                                                
                   76.07   76.07   78.62   78.58   76.24   76.24
                                                                                
                                                                                
                                                                                
  1891.5  1978.6  2018.6  2038.6  2108.6  2381.5  2548.6  2578.6  2701.5  2971.5
  3011.5  3148.6  3251.5  3281.5  3351.5  3381.5  3748.6  4042.5  4282.5  4352.5
  4412.5    4975  4980.6 4986.69  4986.8 5013.29  5013.4  5020.7  5040.2  5267.4
  5532.5  5647.4  5952.5  5992.5  6012.5  6082.5  6112.5  6490.3  6591.4  6610.3
  7460.3  7530.3  7890.3  8211.4  8730.3  9110.3  9151.4  9431.4  9620.3  9930.3
 10161.4 10201.4 10751.4 10781.4 10831.4 11031.4 11081.4 11131.4 11269.2   11341
    82.2   82.01   79.31   79.16   80.91    81.8   81.31   80.31   79.78   80.24
    81.3   81.41   79.67    80.1   79.56    80.4   80.11   80.81   79.31   81.61
   79.61   80.03      80   79.97   79.97   79.93   79.93   79.92   80.45   78.94
   79.21   78.22   78.58   79.01   80.01   79.81    78.7   78.71    77.9   78.41
   80.03   81.11   81.71    83.3   83.41   84.71    83.6    84.3   83.51   85.21
   83.81    84.4    85.3    84.6    86.1    84.8    85.1    83.9   83.51    84.1
                                                                                
                                                                                
                   76.07   76.07   78.62   78.58   76.24   76.24
                                                                                
                                                                                
                                                                                
BR Coef= 1 , 1 , 0 ,1.25, 0 ,,,.8,0,2,0,
WSPro=,,,, 1 ,,,, 0 ,,,, 0 ,,,,-1 ,-1 ,-1 , 0 , 0 , 0 , 0 , 0
BC Design=,, 0 ,, 0 ,,,,,,
BC HTab HWMax=85.19

Type RM Length L Ch R = 1 ,43207.00,220.9,220,209.6
BEGIN DESCRIPTION:
GRANVILLE
Downstream Section of Bridge/Culvert/Weir
END DESCRIPTION:
XS GIS Cut Line= 4
      3107429.26      13880069.8      3105858.27     13878828.79
      3103268.21     13878724.02      3098967.25     13880821.55
#Sta/Elev= 30
  1902.9   82.19  1978.6   81.99  2038.6   78.89  2108.6   80.89  2548.6   81.29
  2648.6   79.69  3148.6   81.39  3278.6   79.19  4042.5   80.79  4282.5   79.29
  4352.5   81.59  4412.5   79.59    4577    79.8    4975   79.27  4980.6    79.2
  4996.1   71.45  5003.8   71.47  5017.6   79.23  5020.7   79.39  5632.5   78.19
  5952.5   78.49  6012.5   79.99  6162.5   77.89  6580.3   77.59  9110.3   84.69
  9490.3   82.89  9930.3   85.19 10199.7   83.93 10740.3   85.19 11269.2   83.49
#Mann= 8 ,-1 , 0
  1902.9      .1       0  4352.5     .08       0    4577     .07       0
    4975     .04       0  4980.6    .045       0  5017.6     .04       0
  5020.7     .08       0 10199.7     .08       0
#XS Ineff= 4 ,-1
  1902.9 4340.43   82.25 4340.43 4989.69      80  5013.4 6089.83    79.9
 6089.83 8387.71   82.22
Permanent Ineff=
       F       F       F       F
Bank Sta=4980.6,5017.6
XS Rating Curve= 0
Exp/Cntr=.5,.3

Type RM Length L Ch R = 1 ,42987.00,90.5,91,104.4
BEGIN DESCRIPTION:
Cross Section Xsec 34c
END DESCRIPTION:
XS GIS Cut Line= 4
      3107529.48     13879902.83      3105854.18     13878581.17
      3103269.92     13878542.22       3099720.1     13880282.38
#Sta/Elev= 30
  1788.2    81.8  1848.2    81.6  1898.2    78.3  2138.2    80.8  2208.2    78.5
  2608.2    80.3  2788.2    78.9  3922.1    79.7  3942.1    79.5  3972.1    76.2
  4002.1    80.2  4342.1    81.3  4452.1    79.2  4767.7   79.16  4974.6   79.22
  4981.4   78.24  4988.4    73.8    5001    71.1  5005.1    71.5  5011.9   76.85
  5021.2    78.7  5142.1    80.4  5232.1    78.7  7026.6    78.3  7806.6    80.7
  7836.6    79.6  8526.6    83.7  8596.6    82.3 10207.2   84.09   10460    86.4
#Mann= 9 ,-1 , 0
  1788.2      .1       0  4342.1     .08       0  4767.7     .07       0
  4974.6     .04       0  4981.4    .045       0  5011.9     .04       0
  5021.2     .08       0 10207.2     .08       0   10460      .1       0
#XS Ineff= 2 ,-1
  1788.2 4349.88   82.34 5853.43 8794.33   82.23
Permanent Ineff=
       F       F
Bank Sta=4981.4,5011.9
XS Rating Curve= 0
Exp/Cntr=.5,.3

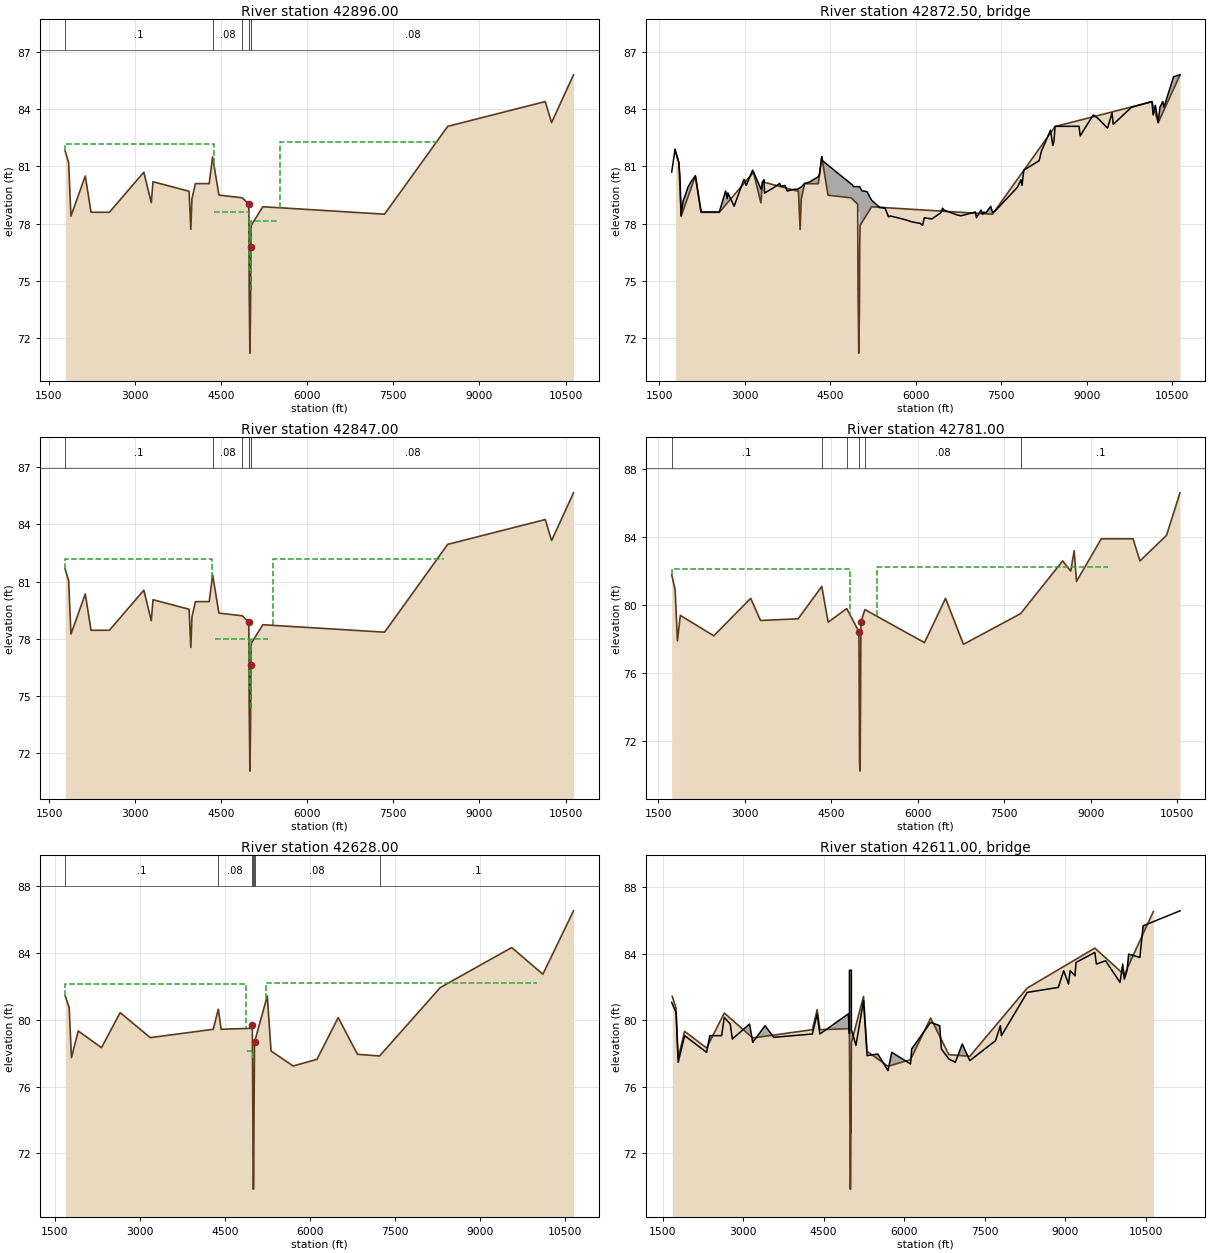
Type RM Length L Ch R = 1 ,42896.00,48.8,49,50.3
BEGIN DESCRIPTION:
DILLARD u/s
Upstream Section of Bridge/Culvert/Weir
END DESCRIPTION:
XS GIS Cut Line= 4
      3107551.43      13879816.7      3105872.23     13878508.62
      3103287.75     13878426.57      3099565.36     13880243.79
#Sta/Elev= 30
  1782.2   81.79    1842   81.19    1882   78.39    2132   80.49    2232   78.59
    2552   78.59    3152   80.69    3282   79.09    3312   80.19  3940.6   79.69
  3970.6   77.69  3990.6   79.29  4050.6   80.09  4290.6   80.09  4350.6   81.49
  4460.6   79.49  4865.7   79.35    4977   79.03  4980.9      79  4988.3   74.34
  5000.1   71.21  5010.9   73.37  5016.7   76.75  5023.9   77.91  5226.2   78.88
  7346.4   78.49  8446.4   83.09 10146.4   84.39 10256.4   83.29 10638.9   85.79
#Mann= 7 ,-1 , 0
  1782.2      .1       0  4350.6     .08       0  4865.7     .07       0
    4977     .04       0  4980.9    .045       0  5016.7     .04       0
  5023.9     .08       0
#XS Ineff= 4 ,-1
 5531.92 8283.69   82.29  1782.2 4378.25   82.16 4378.25  4986.4   78.62
 5012.88 5465.72   78.13
Permanent Ineff=
       F       F       F       F
Bank Sta=4980.9,5016.7
XS Rating Curve= 0
Exp/Cntr=.5,.3

Type RM Length L Ch R = 3 ,42872.50,,,
BEGIN DESCRIPTION:
DILLARD
Structure ID: E101-00-00-32
END DESCRIPTION:
Bridge Culvert--1,0,-1,-1, 0
Deck Dist Width WeirC Skew NumUp NumDn MinLoCord MaxHiCord MaxSubmerge Is_Ogee
10,27,2.6,0, 162, 162, , , .95, 0, ,,,
  1715.7  1775.7    1782  1835.7    1842  1855.7    1862  1875.7    1882    1912
  1915.7    1942    2002  2055.7    2132  2190.1  2225.7    2232    2552  2635.7
    2662  2663.2    2692    2702  2765.7  2805.7    2812    2982  2995.7  3025.7
    3032  3135.7    3152    3272    3282  3285.7    3292    3312  3313.9    3332
  3335.7    3342  3345.7  3525.7    3612    3632  3705.7  3745.7  3865.7  3910.6
  3922.4  3940.6  3952.4  3960.6  3970.6  3990.6  4050.6  4133.2  4135.7  4290.6
  4312.4  4350.6  4362.4  4460.6  4865.7  4886.9  4905.4  4929.3  4948.8    4973
    4977  4980.9  4983.4  4985.8 4985.89    4986 4986.11  4986.2 4986.31  4986.4
 5012.49  5012.6 5012.71  5012.8 5012.89    5013  5013.1  5016.7  5023.9  5026.6
    5055  5071.6  5100.3  5107.5  5145.6  5185.8  5226.2  5372.4  5392.4  5442.4
  5460.6  5472.4  5502.4  5522.4  5552.4  5610.6  5730.6  5822.4  5932.4  5992.4
  6022.4  6080.6  6120.6  6150.6  6280.6  6410.6  6440.6  6470.6  6496.4  6500.8
  6730.8  6796.4  7046.4  7066.4  7146.4  7176.4  7196.4  7216.4  7240.8  7316.4
  7346.4  7390.8  7770.8  7786.4  7810.8    7816  7846.4  7866.4  7896.4  8166.4
  8206.4  8366.4  8406.4  8426.4  8446.4  8866.4  8886.4  9116.4  9206.4  9366.4
  9446.4  9466.4  9786.4 10146.4 10166.4 10206.4 10256.4 10286.4 10336.4 10356.4
 10526.4 10638.7
    80.7    81.9    81.8   81.27   81.21   80.66   80.41   79.04   78.41   79.09
    79.2   79.39   79.91    80.2   80.51   79.41   78.73   78.61   78.61   79.45
   79.71   79.69   79.31   79.61    79.2   78.95   78.91   80.31    80.3      80
   80.05    80.8   80.71   79.89   79.82    79.8   79.86   80.21   80.19   80.26
    80.3   79.86    79.6   79.92   80.11   79.96      80   79.71    79.8    79.8
    79.8   79.83   79.85   79.87   79.89   79.92   80.11   80.18   80.18   80.46
   80.62   81.51    81.3   81.06   80.08   80.03   79.94   79.94   79.94   79.94
   79.94   79.94   79.94   79.94   79.94   79.94   79.94   79.94   79.94   79.94
   79.94   79.94   79.94   79.94   79.94   79.94   79.94   79.92   79.88   79.87
   79.72   79.71    79.7    79.7   79.67   79.44   79.22   78.84   78.84   78.82
   78.81   78.72    78.5   78.36    78.4   78.36   78.27    78.2   78.09   78.06
   78.04   78.01   77.91   78.31   78.24   78.51   78.57   78.81   78.69    78.7
   78.45   78.41   78.61   78.31   78.71   78.49   78.61   78.56    78.6   78.91
    78.6   78.65   79.86   79.91   80.07   80.11    80.3      80    80.8    81.3
    81.8    82.9    82.1    82.3    83.1    83.1    82.6    83.7    83.5      83
    83.8    83.2    84.1    84.4    83.7    84.2    83.3    84.1    84.4    84.1
    85.7    85.8
                                                                                
                                                                                
                                                                                
                                                                                
                                                                                
                                                                                
                                                                                
                                                                           78.65
   78.58   78.58   78.58   78.58
                                                                                
                                                                                
                                                                                
                                                                                
                                                                                
                                                                                
                                                                                
                
  1715.7  1775.7    1782  1835.7    1842  1855.7    1862  1875.7    1882    1912
  1915.7    1942    2002  2055.7    2132  2190.1  2225.7    2232    2552  2635.7
    2662  2663.2    2692    2702  2765.7  2805.7    2812    2982  2995.7  3025.7
    3032  3135.7    3152    3272    3282  3285.7    3292    3312  3313.9    3332
  3335.7    3342  3345.7  3525.7    3612    3632  3705.7  3745.7  3865.7  3910.6
  3922.4  3940.6  3952.4  3960.6  3970.6  3990.6  4050.6  4133.2  4135.7  4290.6
  4312.4  4350.6  4362.4  4460.6  4865.7  4886.9  4905.4  4929.3  4948.8    4973
    4977  4980.9  4983.4  4985.8 4985.89    4986 4986.11  4986.2 4986.31  4986.4
 5012.49  5012.6 5012.71  5012.8 5012.89    5013  5013.1  5016.7  5023.9  5026.6
    5055  5071.6  5100.3  5107.5  5145.6  5185.8  5226.2  5372.4  5392.4  5442.4
  5460.6  5472.4  5502.4  5522.4  5552.4  5610.6  5730.6  5822.4  5932.4  5992.4
  6022.4  6080.6  6120.6  6150.6  6280.6  6410.6  6440.6  6470.6  6496.4  6500.8
  6730.8  6796.4  7046.4  7066.4  7146.4  7176.4  7196.4  7216.4  7240.8  7316.4
  7346.4  7390.8  7770.8  7786.4  7810.8    7816  7846.4  7866.4  7896.4  8166.4
  8206.4  8366.4  8406.4  8426.4  8446.4  8866.4  8886.4  9116.4  9206.4  9366.4
  9446.4  9466.4  9786.4 10146.4 10166.4 10206.4 10256.4 10286.4 10336.4 10356.4
 10526.4 10638.7
    80.7    81.9    81.8   81.27   81.21   80.66   80.41   79.04   78.41   79.09
    79.2   79.39   79.91    80.2   80.51   79.41   78.73   78.61   78.61   79.45
   79.71   79.69   79.31   79.61    79.2   78.95   78.91   80.31    80.3      80
   80.05    80.8   80.71   79.89   79.82    79.8   79.86   80.21   80.19   80.26
    80.3   79.86    79.6   79.92   80.11   79.96      80   79.71    79.8    79.8
    79.8   79.83   79.85   79.87   79.89   79.92   80.11   80.18   80.18   80.46
   80.62   81.51    81.3   81.06   80.08   80.03   79.94   79.94   79.94   79.94
   79.94   79.94   79.94   79.94   79.94   79.94   79.94   79.94   79.94   79.94
   79.94   79.94   79.94   79.94   79.94   79.94   79.94   79.92   79.88   79.87
   79.72   79.71    79.7    79.7   79.67   79.44   79.22   78.84   78.84   78.82
   78.81   78.72    78.5   78.36    78.4   78.36   78.27    78.2   78.09   78.06
   78.04   78.01   77.91   78.31   78.24   78.51   78.57   78.81   78.69    78.7
   78.45   78.41   78.61   78.31   78.71   78.49   78.61   78.56    78.6   78.91
    78.6   78.65   79.86   79.91   80.07   80.11    80.3      80    80.8    81.3
    81.8    82.9    82.1    82.3    83.1    83.1    82.6    83.7    83.5      83
    83.8    83.2    84.1    84.4    83.7    84.2    83.3    84.1    84.4    84.1
    85.7    85.8
                                                                                
                                                                                
                                                                                
                                                                                
                                                                                
                                                                                
                                                                                
                                                                           78.65
   78.58   78.58   78.58   78.58
                                                                                
                                                                                
                                                                                
                                                                                
                                                                                
                                                                                
                                                                                
                
BR Coef= 1 , 1 , 0 ,1.25, 0 ,,,.8,0,2,0,
WSPro=,,,, 1 ,,,, 0 ,,,, 0 ,,,,-1 ,-1 ,-1 , 0 , 0 , 0 , 0 , 0
BC Design=,, 0 ,, 0 ,,,,,,
BC HTab HWMax=85.79

Type RM Length L Ch R = 1 ,42847.00,63.9,66,84.8
BEGIN DESCRIPTION:
DILLARD
Downstream Section of Bridge/Culvert/Weir
END DESCRIPTION:
XS GIS Cut Line= 4
      3107514.93       13879732.      3105881.61     13878459.72
       3103282.8     13878377.22      3099554.84     13880197.16
#Sta/Elev= 30
    1782   81.65    1842   81.05    1882   78.25    2132   80.35    2232   78.45
    2552   78.45    3152   80.55    3282   78.95    3312   80.05  3940.6   79.55
  3970.6   77.55  3990.6   79.15  4050.6   79.95  4290.6   79.95  4350.6   81.35
  4460.6   79.35  4865.7   79.21    4977   78.89  4980.9   78.86  4988.3    74.2
  5000.1   71.07  5010.9   73.23  5016.7   76.61  5023.9   77.77  5226.2   78.74
  7346.4   78.35  8446.4   82.95 10146.4   84.25 10256.4   83.15 10638.7   85.65
#Mann= 7 ,-1 , 0
    1782      .1       0  4350.6     .08       0  4865.7     .07       0
    4977     .04       0  4980.9    .045       0  5016.7     .04       0
  5023.9     .08       0
#XS Ineff= 4 ,-1
    1782 4340.43    82.2 5399.53 8387.71    82.2 5012.88 5314.42      78
 4387.71  4986.4      78
Permanent Ineff=
       F       F       F       F
Bank Sta=4980.9,5016.7
XS Rating Curve= 0
Exp/Cntr=.5,.3

Type RM Length L Ch R = 1 ,42781.00,154.3,153,146.7
BEGIN DESCRIPTION:
Cross Section Xsec 34b
END DESCRIPTION:
XS GIS Cut Line= 6
       3107592.7     13879740.82      3105857.96     13878399.91
      3104887.98     13878367.93      3104609.67     13878343.01
      3103305.31     13878282.06      3099618.09     13879992.04
#Sta/Elev= 30
  1736.7    81.8  1796.7    80.9  1836.7    77.9  1886.7    79.4  2466.7    78.2
  3106.7    80.4  3276.7    79.1  3929.3    79.2  4339.3    81.1  4449.3      79
  4771.2    79.8  4983.9   78.44  4993.6   70.89  5000.1   70.25  5003.9   70.57
  5018.3   79.02    5087   79.74  6119.2    77.8    6485    80.4    6795    77.7
    7785    79.5    8515    82.6    8655      82    8715    83.2    8755    81.4
    9185    83.9    9735    83.9    9855    82.6   10315    84.1 10549.4    86.6
#Mann= 6 ,-1 , 0
  1736.7      .1       0  4339.3     .08       0  4771.2     .07       0
  4983.9    .045       0    5087     .08       0    7785      .1       0
#XS Ineff= 2 ,-1
 5295.51 9304.96   82.27 1736.74 4822.69   82.15
Permanent Ineff=
       F       F
Bank Sta=4983.9,5018.3
XS Rating Curve= 0
Exp/Cntr=.5,.3

Type RM Length L Ch R = 1 ,42628.00,37.6,38,38.1
BEGIN DESCRIPTION:
PRIVATE BRIDGE u/s
Upstream Section of Bridge/Culvert/Weir
END DESCRIPTION:
XS GIS Cut Line= 4
      3107654.48      13879608.6      3105915.78     13878259.23
      3103304.33     13878136.08      3099557.83     13879923.33
#Sta/Elev= 30
  1679.9   81.43  1749.8   80.73  1789.8   77.73  1909.8   79.33  2319.8   78.33
  2649.8   80.43  3179.8   78.93  4290.7   79.43  4380.7   80.63  4430.7   79.43
  4976.6   79.49  4980.6   79.67  4991.5   73.42  4995.5   69.86  5003.4   69.85
  5005.7   70.31  5006.9   72.42  5018.9   78.69  5023.8   78.72  5244.5   81.43
  5310.7   78.13  5700.7   77.23  6120.7   77.63  6495.1   80.13  6835.1   77.93
  7225.1   77.83  8295.1   81.93  9555.1   84.33 10105.1   82.73 10646.1   86.53
#Mann= 7 ,-1 , 0
  1679.9      .1       0  4380.7     .08       0  4976.6     .04       0
  4991.5    .045       0  5006.9     .04       0  5023.8     .08       0
  7225.1      .1       0
#XS Ineff= 4 ,-1
 5229.31 9995.27   82.18 1679.91 4869.98   82.13 4879.43    4984   78.15
    5017 5200.95    77.2
Permanent Ineff=
       F       F       F       F
Bank Sta=4980.6,5018.9
XS Rating Curve= 0
Exp/Cntr=.5,.3

Type RM Length L Ch R = 3 ,42611.00,,,
BEGIN DESCRIPTION:
PRIVATE BRIDGE
Structure ID: E101-00-00-31
Chain link fence rail hieght reduced by 0.5 to
model the likeliness that the fence would fall if
the force of the water was above the halff way
point up the fence.
END DESCRIPTION:
Bridge Culvert--1,0,-1,-1, 0
Deck Dist Width WeirC Skew NumUp NumDn MinLoCord MaxHiCord MaxSubmerge Is_Ogee
10,14,2.6,0, 60, 60, , , .95, 0, ,,,
  1668.8  1749.8  1789.8  1909.8  2319.8  2379.8  2599.8  2649.8  2759.8  2799.8
  3119.8  3179.8  3409.8  3569.8  4290.7  4380.7  4430.7  4960.7 4981.89    4982
 5016.99 5018.19  5018.3 5018.41  5103.1  5244.5  5310.7  5510.7  5700.7  5770.7
  6120.7  6140.7  6495.1  6665.1  6695.1  6835.1  6955.1  7085.1  7225.1  7705.1
  7795.1  7815.1  8295.1  8875.1  8975.1  9065.1  9095.1  9185.1  9205.1  9555.1
  9585.1  9755.1 10025.1 10075.1 10105.1 10155.1 10185.1 10395.1 10455.1 11142.8
   81.07   80.47   77.47   79.07   78.07   79.07   79.07   80.17   79.77   78.87
   79.77   78.67   79.67   78.97   79.17   80.37   79.17   80.38   79.19      83
      83      83      83   79.42   78.49   81.17   77.87   77.97   76.97   78.07
   77.37   78.27   79.87   79.67   78.27   77.67   77.47   78.57   77.57   78.77
   79.67   79.07   81.67   81.97   82.97   82.17   82.97   82.67   83.47   84.07
   83.37   83.57   82.27   83.37   82.47   82.97   83.97   83.77   85.67   86.57
                                                                                
                                                                            77.4
   77.71    77.7
                                                                                
                                                                                
                                                                                
  1668.8  1749.8  1789.8  1909.8  2319.8  2379.8  2599.8  2649.8  2759.8  2799.8
  3119.8  3179.8  3409.8  3569.8  4290.7  4380.7  4430.7  4960.7 4981.89    4982
 5016.99 5018.19  5018.3 5018.41  5103.1  5244.5  5310.7  5510.7  5700.7  5770.7
  6120.7  6140.7  6495.1  6665.1  6695.1  6835.1  6955.1  7085.1  7225.1  7705.1
  7795.1  7815.1  8295.1  8875.1  8975.1  9065.1  9095.1  9185.1  9205.1  9555.1
  9585.1  9755.1 10025.1 10075.1 10105.1 10155.1 10185.1 10395.1 10455.1 11142.8
   81.07   80.47   77.47   79.07   78.07   79.07   79.07   80.17   79.77   78.87
   79.77   78.67   79.67   78.97   79.17   80.37   79.17   80.38   79.19      83
      83      83      83   79.42   78.49   81.17   77.87   77.97   76.97   78.07
   77.37   78.27   79.87   79.67   78.27   77.67   77.47   78.57   77.57   78.77
   79.67   79.07   81.67   81.97   82.97   82.17   82.97   82.67   83.47   84.07
   83.37   83.57   82.27   83.37   82.47   82.97   83.97   83.77   85.67   86.57
                                                                                
                                                                            77.4
   77.71    77.7
                                                                                
                                                                                
                                                                                
Pier Skew, UpSta & Num, DnSta & Num=  ,4990.3, 2 ,4990.3, 2 , 0 , 0 , 0 ,,
      .7      .7
   72.88   78.55
      .7      .7
   72.99   78.66
Pier Skew, UpSta & Num, DnSta & Num=  ,5008.4, 2 ,5008.4, 2 , 0 , 0 , 0 ,,
      .7      .7
   71.87   78.66
      .7      .7
   71.98   78.77
BR Coef= 1 , 1 , 1 ,1.25, 0 ,,,.8,0,2,0,
WSPro=,,,, 1 ,,,, 0 ,,,, 0 ,,,,-1 ,-1 ,-1 , 0 , 0 , 0 , 0 , 0
BC Design=,, 0 ,, 0 ,,,,,,
BC HTab HWMax=86.83

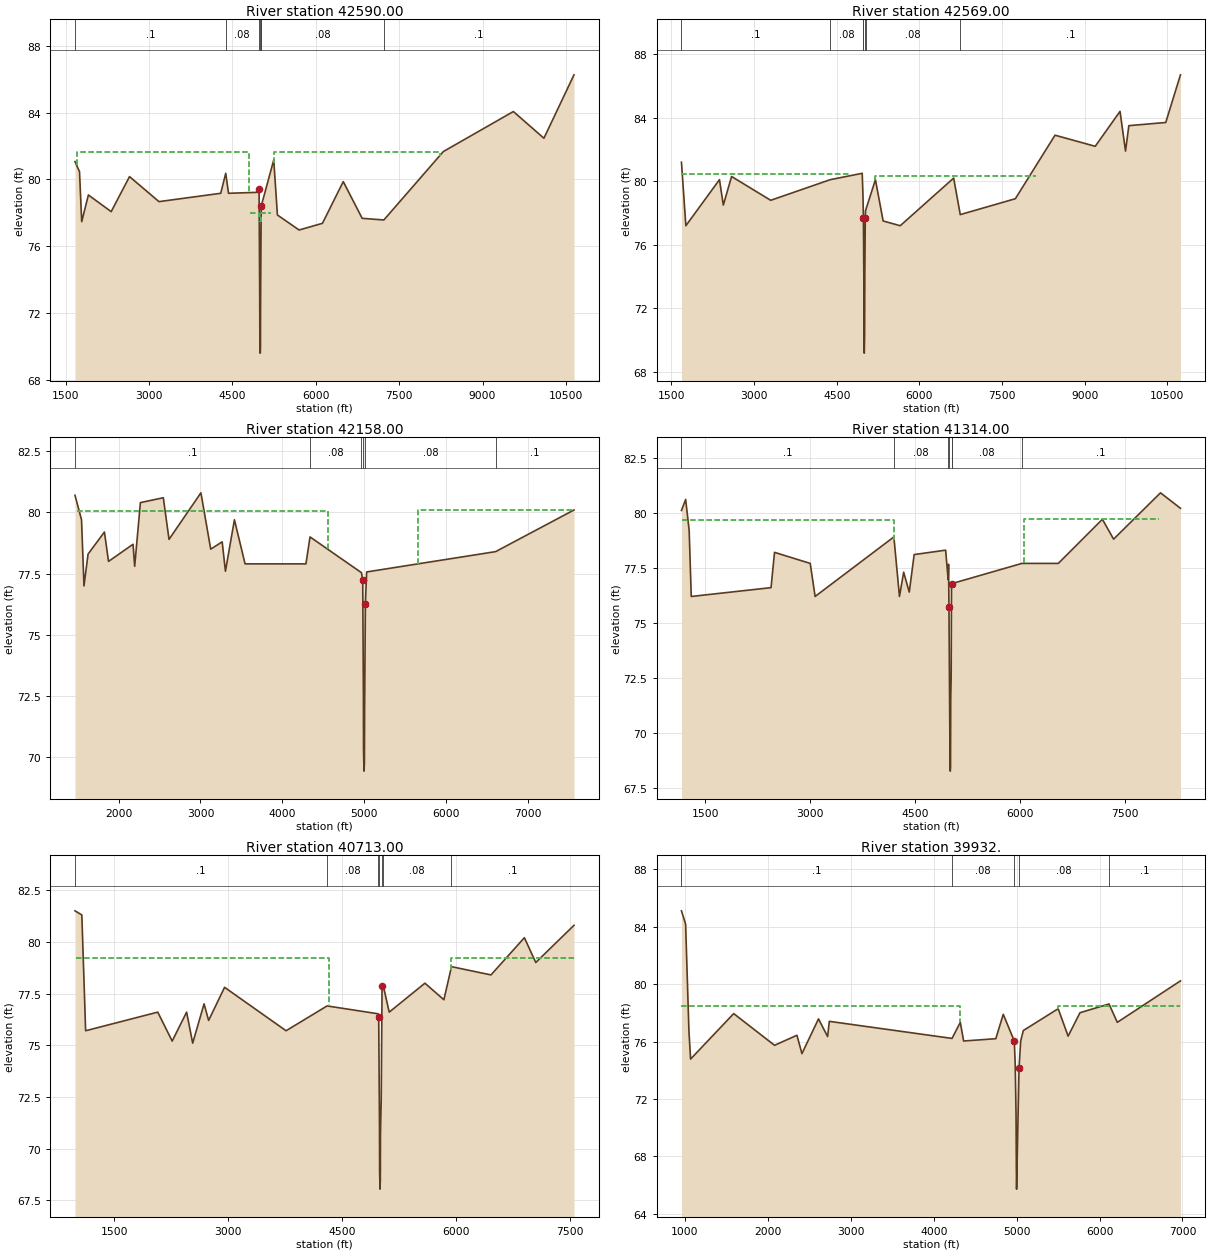
Type RM Length L Ch R = 1 ,42590.00,21.6,21,20.3
BEGIN DESCRIPTION:
PRIVATE BRIDGE
Downstream Section of Bridge/Culvert/Weir
END DESCRIPTION:
XS GIS Cut Line= 4
      3107670.12      13879576.3      3105925.18     13878222.08
      3103299.55     13878098.27      3099547.38     13879888.22
#Sta/Elev= 30
  1668.8   81.07  1749.8   80.47  1789.8   77.47  1909.8   79.07  2319.8   78.07
  2649.8   80.17  3179.8   78.67  4290.7   79.17  4380.7   80.37  4430.7   79.17
  4976.6   79.23  4980.6   79.41  4991.5   73.16  4995.5    69.6  5003.4   69.59
  5005.7   70.05  5006.9   72.16  5018.9   78.43  5023.8   78.46  5244.5   81.17
  5310.7   77.87  5700.7   76.97  6120.7   77.37  6495.1   79.87  6835.1   77.67
  7225.1   77.57  8295.1   81.67  9555.1   84.07 10105.1   82.47   10646   86.27
#Mann= 7 ,-1 , 0
  1668.8      .1       0  4380.7     .08       0  4976.6     .04       0
  4991.5    .045       0  5006.9     .04       0  5023.8     .08       0
  7225.1      .1       0
#XS Ineff= 4 ,-1
 5248.23 8226.95   81.66 1697.21 4794.33   81.64    5017 5200.95      78
 4813.24    4984      78
Permanent Ineff=
       F       F       F       F
Bank Sta=4980.6,5018.9
XS Rating Curve= 0
Exp/Cntr=.5,.3

Type RM Length L Ch R = 1 ,42569.00,465.7,411,440.6
BEGIN DESCRIPTION:
Cross Section Xsec 34a
END DESCRIPTION:
XS GIS Cut Line= 4
      3107692.32     13879489.38      3105946.26     13878199.06
      3103288.34     13878079.41       3099311.7     13879535.94
#Sta/Elev= 30
  1681.4    81.2  1761.4    77.2  2371.4    80.1  2441.4    78.5  2591.4    80.3
  3301.4    78.8  4382.5    80.1  4962.5    80.5    4976   79.17  4984.6   77.66
  4992.2   73.91  4993.8    70.3  4999.6   69.18  5006.2   70.26  5009.9   74.04
    5018   77.71  5023.1   78.15  5202.5    80.1  5342.5    77.5  5652.5    77.2
  6622.6    80.2  6742.6    77.9  7742.6    78.9  8462.6    82.9  9192.6    82.2
  9642.6    84.4  9742.6    81.9  9802.6    83.5 10472.6    83.7 10739.7    86.7
#Mann= 7 ,-1 , 0
  1681.4      .1       0  4382.5     .08       0    4976     .04       0
  4984.6    .045       0    5018     .04       0  5023.1     .08       0
  6742.6      .1       0
#XS Ineff= 2 ,-1
 1681.42 4718.68   80.43 5200.95 8113.48   80.31
Permanent Ineff=
       F       F
Bank Sta=4984.6,5018
XS Rating Curve= 0
Exp/Cntr=.3,.1

Type RM Length L Ch R = 1 ,42158.00,892.4,844,877.1
BEGIN DESCRIPTION:
Cross Section x34
END DESCRIPTION:
XS GIS Cut Line= 3
       3107817.2     13879299.96      3106098.17     13877856.83
      3102256.89     13877496.04
#Sta/Elev= 30
  1465.5    80.7  1545.5    79.7  1575.5      77  1625.5    78.3  1825.5    79.2
  1875.5      78  2175.5    78.7  2195.5    77.8  2265.5    80.4  2545.5    80.6
  2615.5    78.9  3005.5    80.8  3125.5    78.5  3265.5    78.8  3305.5    77.6
  3415.5    79.7  3545.5    77.9    4290    77.9    4340      79    4969   77.54
  4984.3   77.25  4992.8   72.48  4994.2   70.33  4999.9   69.44  5005.1   69.79
  5007.3   71.84    5017   76.26  5032.5   77.57    6610    78.4  7568.2    80.1
#Mann= 6 ,-1 , 0
  1465.5      .1       0    4340     .08       0    4969     .04       0
  4984.3    .045       0    5017     .08       0    6610      .1       0
#XS Ineff= 2 ,-1
 5661.66  7568.2   80.08 1493.09 4563.44   80.07
Permanent Ineff=
       F       F
Bank Sta=4984.3,5017
XS Rating Curve= 0
Exp/Cntr=.3,.1

Type RM Length L Ch R = 1 ,41314.00,605.3,601,659.1
BEGIN DESCRIPTION:
Cross Section x33
END DESCRIPTION:
XS GIS Cut Line= 3
      3108409.03     13878139.94      3105953.26     13876935.46
      3101560.32     13876787.95
#Sta/Elev= 30
  1158.8    80.1  1218.8    80.6  1268.8    79.2  1298.8    76.2  2438.8    76.6
  2488.8    78.2  2998.8    77.7  3068.8    76.2  4194.1    78.9  4274.1    76.2
  4334.1    77.3  4414.1    76.4  4484.1    78.1  4934.1    78.3  4969.6   76.97
  4975.2   77.66  4981.6    75.7  4995.4   69.14  4999.7   68.28  5003.7   68.49
    5007   71.62  5012.7   72.56    5018   76.77    5019   76.78  6024.1    77.7
  6544.1    77.7  7174.1    79.7  7334.1    78.8  8004.1    80.9  8289.5    80.2
#Mann= 7 ,-1 , 0
  1158.8      .1       0  4194.1     .08       0  4969.6     .04       0
  4981.6    .045       0    5018     .04       0    5019     .08       0
  6024.1      .1       0
#XS Ineff= 2 ,-1
 6054.93    7984    79.7 1171.41 4202.52   79.65
Permanent Ineff=
       F       F
Bank Sta=4981.6,5018
XS Rating Curve= 0
Exp/Cntr=.3,.1

Type RM Length L Ch R = 1 ,40713.00,776.6,781,825.3
BEGIN DESCRIPTION:
Cross Section x32
END DESCRIPTION:
XS GIS Cut Line= 3
      3108435.92     13878086.18      3105447.11     13876345.96
      3102345.05     13876079.11
#Sta/Elev= 30
     983    81.5  1073.1    81.3  1123.1    75.7  2073.1    76.6  2263.1    75.2
  2453.1    76.6  2533.1    75.1  2683.1      77  2743.1    76.2  2953.1    77.8
  3763.1    75.7  4303.1    76.9  4975.8   76.52    4983   76.38  4993.1   71.24
    4995   68.91  4999.9   68.04  5004.8   68.52  5006.4   70.76    5016   72.34
  5027.3   77.86  5039.2   77.94  5121.6    76.6  5591.6      78  5841.6    77.2
  5941.6    78.8  6461.6    78.4  6901.6    80.2  7051.6      79  7555.1    80.8
#Mann= 7 ,-1 , 0
     983      .1       0  4303.1     .08       0  4975.8     .04       0
    4983     .04       0  5027.3     .04       0  5039.2     .08       0
  5941.6      .1       0
#XS Ineff= 2 ,-1
 5931.12  7555.1   79.24  989.76 4330.97   79.23
Permanent Ineff=
       F       F
Bank Sta=4983,5027.3
XS Rating Curve= 0
Exp/Cntr=.3,.1

Type RM Length L Ch R = 1 ,39932.  ,100.7,101,101.2
BEGIN DESCRIPTION:
North Shepherd-XS4
END DESCRIPTION:
XS GIS Cut Line= 6
      3108438.13     13877985.56      3107434.79     13877481.75
      3105232.58     13876180.33      3105238.26     13875738.19
      3104806.07     13875362.06      3103502.17     13875145.27
#Sta/Elev= 30
   957.9   85.11  1007.9   84.19  1047.9   76.76  1067.9   74.78  1587.9   77.95
  2080.6   75.74  2350.6   76.44  2410.6   75.16  2610.6   77.58  2720.6   76.35
  2740.6   77.41  4220.6   76.22  4320.6   77.34  4360.6   76.04  4748.6    76.2
  4838.6    77.9  4971.5   76.04  4982.5   74.47  4992.8   70.91  4996.4    67.2
  4999.3   65.72  5028.6   74.13  5048.6   76.04  5080.8   76.77  5500.8   78.29
  5620.8   76.38  5763.8   78.01  6113.8   78.62  6213.8   77.34  6975.5   80.23
#Mann= 5 ,-1 , 0
   957.9      .1       0  4220.6     .08       0  4971.5    .045       0
  5028.6     .08       0  6113.8      .1       0
#XS Ineff= 2 , 0
       0    4320    78.5    5498       0    78.5
Permanent Ineff=
       F       F
Bank Sta=4971.5,5028.6
XS Rating Curve= 0
Exp/Cntr=.5,.3