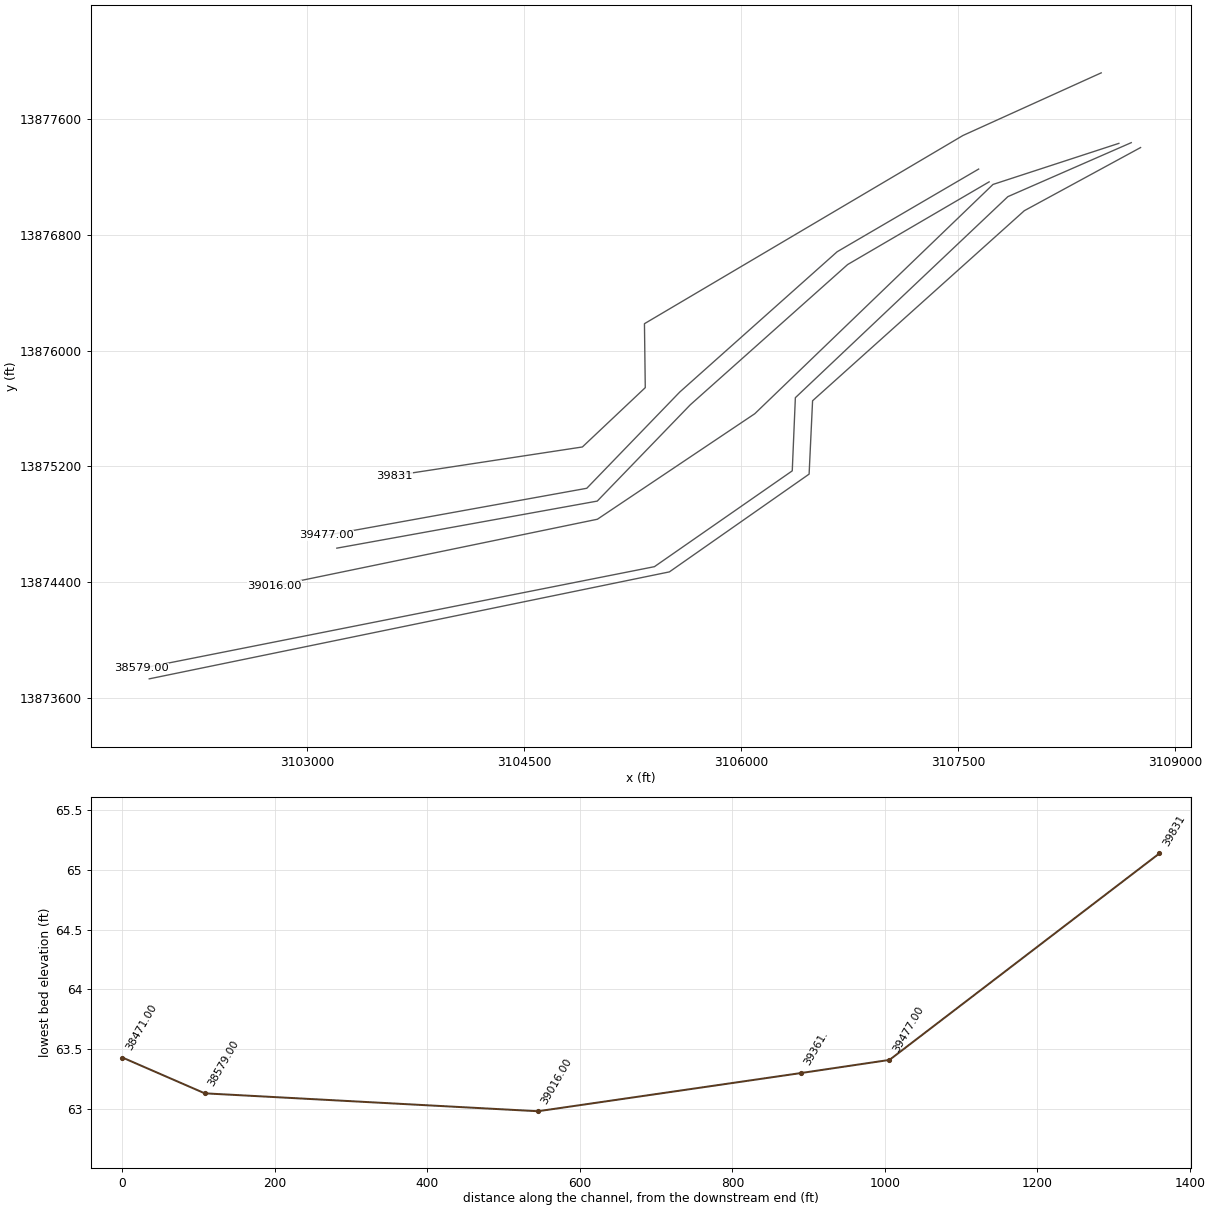
HEC-RAS study E101_00_00.prj: E101-00-00

--- E101_00_00.g01 (geometry) --- (continued)

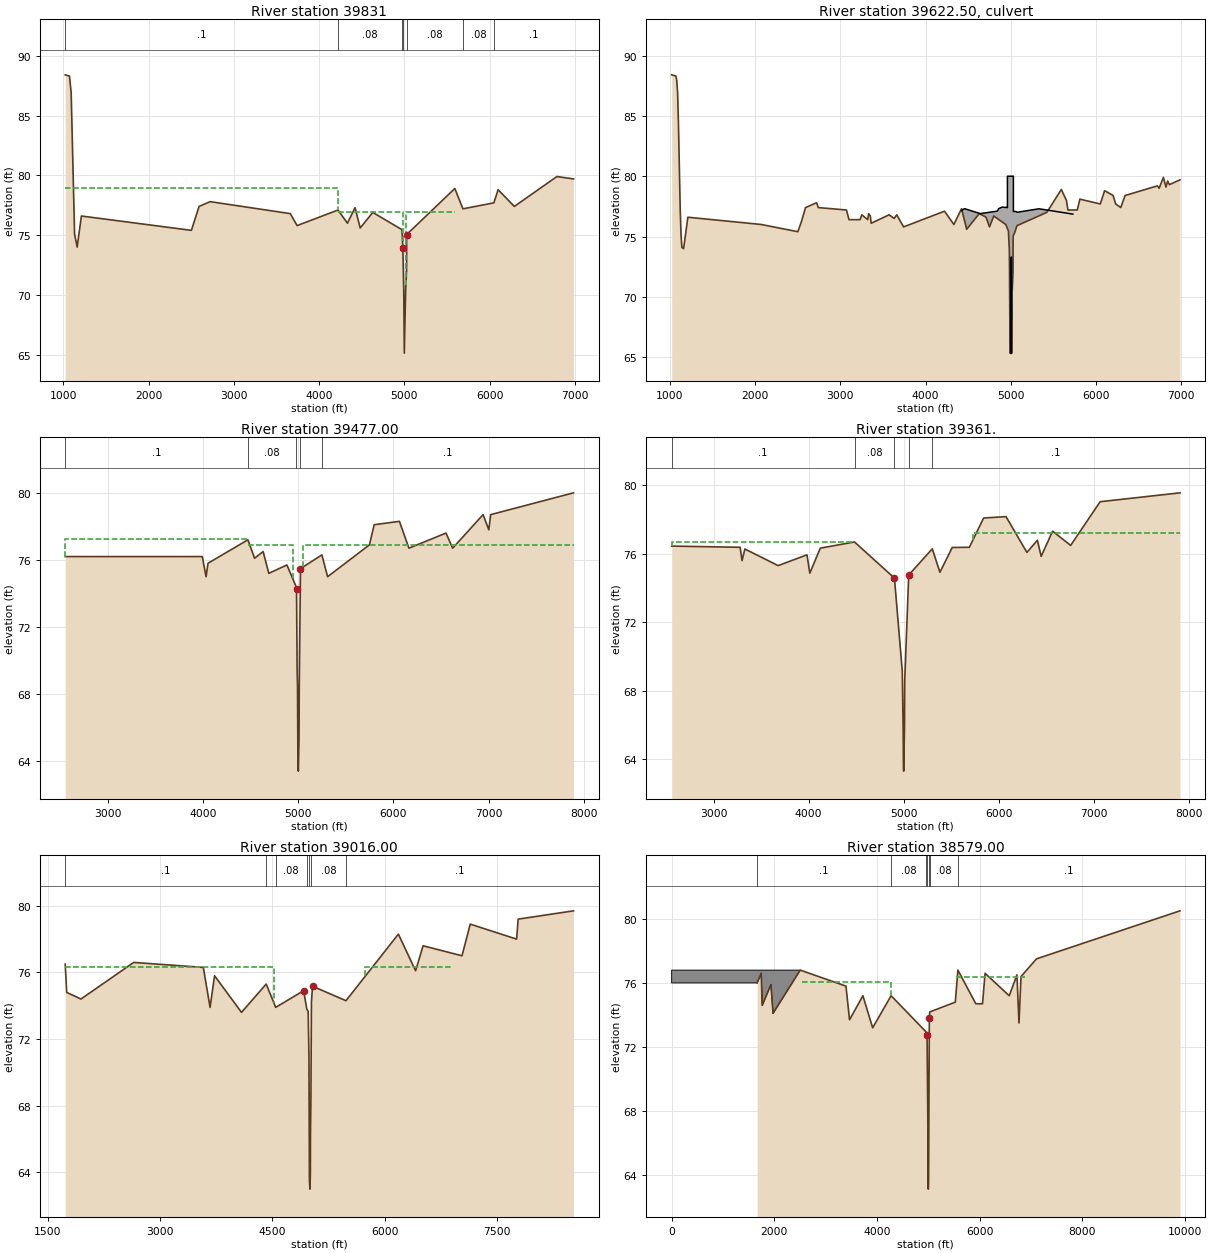
Type RM Length L Ch R = 1 ,39831   ,386.9,354,281.9
BEGIN DESCRIPTION:
Cross Section Xsec 31b
END DESCRIPTION:
XS GIS Cut Line= 6
      3108491.14     13877921.07      3107535.33     13877488.03
      3105333.12     13876186.61       3105338.8     13875744.47
      3104904.05     13875334.26      3103605.98     13875136.44
#Sta/Elev= 30
  1021.7    88.4  1071.7    88.3  1091.7    86.9  1131.7    75.1  1161.7      74
  1211.7    76.6  2501.9    75.4  2591.9    77.4  2721.6    77.8  3661.9    76.8
  3741.9    75.8  4221.9    77.1  4331.9      76  4421.9    77.3  4481.9    75.6
  4629.9    76.9  4971.5   75.46  4982.5   73.89  4992.8   70.33  4999.3   65.14
    5015   70.39  5026.1   72.06  5026.8   75.05  5592.1    78.9  5686.6    77.2
  6049.8    77.7  6099.8    78.8  6289.8    77.4  6789.8    79.9  6984.3    79.7
#Mann= 7 ,-1 , 0
  1021.7      .1       0  4221.9     .08       0  4971.5     .04       0
  4982.5    .045       0  5026.8     .08       0  5686.6     .08       0
  6049.8      .1       0
#XS Ineff= 5 ,-1
  1021.7 4224.81   78.95 5589.15 6976.74   78.87 5017.82 5589.15    76.9
 4224.81 4980.89    76.9 6976.74  6984.3    76.9
Permanent Ineff=
       T       F       F       F       F
Bank Sta=4982.5,5026.8
XS Rating Curve= 0
Exp/Cntr=.5,.3

Type RM Length L Ch R = 2 ,39622.50,,,
BEGIN DESCRIPTION:
N SHEPHERD
Structure ID: E101-00-00-30
Chain link fence rail hieght reduced by 0.5 to
model the likeliness that the fence would fall if
the force of the water was above the halff way
point up the fence.
END DESCRIPTION:
Bridge Culvert--1,0,-1,-1, 0
Deck Dist Width WeirC Skew NumUp NumDn MinLoCord MaxHiCord MaxSubmerge Is_Ogee
109,205,2.6,0, 29, 28, , , .95, 0, ,,,
    4422    4457  4640.8  4836.1  4845.1  4856.1  4899.4    4925  4950.3  4957.4
    4960  4960.1  4976.8  4989.1  4992.9  4998.5  4998.9    5000  5000.8  5001.4
  5006.3  5015.9  5019.8    5030  5030.1  5058.1  5072.9    5330 5727.05
   77.16   77.31    76.9    77.1   77.14   77.31   77.44   77.42   77.41    77.4
    77.4      80      80      80      80      80      80      80      80      80
      80      80      80      80   77.08   77.08   77.01    77.3   76.86
                                                                                
                                                                                
                                                                        
 4469.21  4640.8  4836.1  4845.1  4856.1  4899.4    4925  4950.3  4957.4    4960
  4960.1  4976.8  4989.1  4992.9  4998.5  4998.9    5000  5000.8  5001.4  5006.3
  5015.9  5019.8    5030  5030.1  5058.1  5072.9    5330 5727.05
   77.14    76.9    77.1   77.14   77.31   77.44   77.42   77.41    77.4    77.4
      80      80      80      80      80      80      80      80      80      80
      80      80      80   77.08   77.08   77.01    77.3   76.86
                                                                                
                                                                                
                                                                
BR Coef= 1 , 1 , 1 ,1.25, 0 ,,,.8,0,2,0,
WSPro=,,,, 1 ,,,, 0 ,,,, 0 ,,,,-1 ,-1 ,-1 , 0 , 0 , 0 , 0 , 0
Culvert=2,8,8,205,.015,.5,1,8,2,65.34,4994.9,65.3,4994.9,Culvert #1  , 0 ,109
Culvert Bottom n=.015
Culvert=2,8,8,205,.015,.5,1,8,2,65.36,5003.7,65.36,5003.7,Culvert #2  , 0 ,109
Culvert Bottom n=.015
BR U #Sta/Elev= 69
  1021.7    88.4  1071.7    88.3  1081.7    87.9  1091.7    86.9  1101.7    84.2
  1121.7    77.3  1131.7    75.1  1141.7    74.1  1161.7      74  1211.7    76.6
  2071.9      76  2466.1   75.45  2501.9    75.4  2541.9    76.2  2591.9    77.4
  2721.6    77.8  2721.9    77.8  2741.9    77.4  3071.9    77.2  3101.9    76.4
  3231.9    76.4  3251.9    76.8  3321.9    76.4  3331.9    76.9  3351.9    76.7
  3361.9    76.1  3571.9    76.8  3631.9    76.5  3661.9    76.8  3741.9    75.8
  4221.9    77.1  4331.9      76  4421.9    77.3  4481.9    75.6  4629.9    76.9
  4709.9    76.6  4749.9    75.8  4799.9    76.7  4939.9      76  4971.5   75.46
  4982.5   73.89  4990.9   65.34  5011.7   65.36    5015   70.39  5026.1   72.06
  5026.8   75.05  5031.2   75.09  5049.9    75.4  5072.1    75.9  5422.1      77
  5592.1    78.9  5652.1      78  5669.8    77.2  5686.6    77.2  5779.8    77.2
  5809.8    78.1  6049.8    77.7  6099.8    78.8  6199.8    78.4  6229.8    77.7
  6289.8    77.4  6339.8    78.4  6719.8    79.2  6739.8      79  6789.8    79.9
  6819.8    79.1  6839.8    79.6  6859.8    79.3  6984.3    79.7
BR U #Mann= 7
  1021.7      .1  4221.9     .08  4971.5     .04  4982.5    .045  5026.8     .08
  5686.6     .08  6049.8      .1
BR D #Sta/Elev= 65
  2547.6    76.2  2850.1   76.42  2910.6   76.47  2956.2    76.5  3016.1    76.5
  3176.2    76.5  3216.2    76.1  3266.2    76.5  3286.2    75.8  3316.2    76.2
  3336.2    76.1  3386.2    76.4  3416.2    75.6  3679.2    76.3  3959.2    75.5
  3989.2    76.2  4029.2      75  4049.2    75.8  4149.2    76.2  4169.2      76
  4469.2    77.2  4539.2    76.1  4629.2    76.5  4679.2    75.7  4689.2    75.2
  4699.2    75.2  4879.2    75.7  4978.2   74.38  4980.5   74.26  4986.9   69.41
  4990.8   65.34  5011.7   65.36  5014.5   71.37  5022.1   75.48  5046.9   76.16
  5074.4   76.37  5089.2      76  5137.2      76  5247.2    76.3  5307.2      75
  5727.2      77  5747.2    76.9  5797.2    78.1  6062.5    78.3  6128.8   77.24
  6162.5    76.7  6342.5    77.3  6372.5    76.6  6552.5    77.6  6622.5    76.7
  6662.5    77.3  6722.5    76.9  6842.5    78.4  6942.5    78.7  6972.5    78.3
  6982.5    78.5  7002.5    77.8  7022.5    78.7  7112.5    78.9  7132.5    78.8
  7232.5    79.2  7252.5    78.8  7452.5    79.3  7882.5    79.8  7893.7      80
BR D #Mann= 5
  2547.6      .1  4469.2     .08  4978.2    .045  5022.1     .08  5247.2      .1
BC Design=,, 0 ,, 0 ,,,,,,
BC HTab HWMax=88.4

Type RM Length L Ch R = 1 ,39477.00,124.2,116,115.8
BEGIN DESCRIPTION:
N SHEPHERD
Cross Section Xsec 31a
END DESCRIPTION:
XS GIS Cut Line= 5
      3107643.75      13877255.8      3106665.51     13876684.16
      3105577.17     13875713.96      3104934.34     13875048.54
      3103133.67     13874723.09
#Sta/Elev= 30
  2547.6    76.2  3989.2    76.2  4029.2      75  4049.2    75.8  4469.2    77.2
  4539.2    76.1  4629.2    76.5  4689.2    75.2  4879.2    75.7  4978.2   74.38
  4980.5   74.26  4986.9   69.41  4990.8   68.52    4995   63.94  4999.5   63.41
  5006.8   65.35  5008.7   68.23  5022.1   75.48  5247.2    76.3  5307.2      75
  5747.2    76.9  5797.2    78.1  6062.5    78.3  6162.5    76.7  6552.5    77.6
  6622.5    76.7  6942.5    78.7  7002.5    77.8  7022.5    78.7  7893.7      80
#Mann= 5 ,-1 , 0
  2547.6      .1       0  4469.2     .08       0  4978.2    .045       0
  5022.1     .08       0  5247.2      .1       0
#XS Ineff= 3 ,-1
  2547.6 4472.87   77.26 4472.87 4947.88    76.9 5050.74  7893.7    76.9
Permanent Ineff=
       T       F       F
Bank Sta=4980.5,5022.1
XS Rating Curve= 0
Exp/Cntr=.5,.3

Type RM Length L Ch R = 1 ,39361.  ,374.6,345,344.8
BEGIN DESCRIPTION:
North Shepherd-XS1
END DESCRIPTION:
XS GIS Cut Line= 5
       3107716.2     13877167.25      3106737.96     13876595.61
      3105649.62     13875625.41      3105006.79     13874959.99
      3103206.12     13874634.54
#Sta/Elev= 30
  2559.3   76.44  3279.3   76.37  3299.3   75.59  3329.3   76.27  3679.3    75.3
  3982.3   75.93  4012.3   74.86  4122.3   76.32  4482.3   76.68  4902.3   74.57
 4984.94   69.11  4994.3   65.55  4996.9   63.57 4999.88    63.3 5008.12   65.96
 5010.27   68.56  5052.3   74.75  5300.3   76.28  5380.3   74.91  5510.3   76.36
  5690.3   76.37  5840.3   78.08  6075.5   78.16  6295.5   76.07  6405.5   76.78
  6445.5   75.84  6565.5   77.31  6755.5   76.48  7065.5   79.03  7905.4   79.55
#Mann= 5 ,-1 , 0
  2559.3      .1       0  4482.3     .08       0  4902.3    .045       0
  5052.3     .08       0  5300.3      .1       0
#XS Ineff= 2 , 0
       0    4479    76.7    5727       0   77.23
Permanent Ineff=
       F       F
Bank Sta=4902.3,5052.3
XS Rating Curve= 0
Exp/Cntr=.3,.1

Type RM Length L Ch R = 1 ,39016.00,214.5,437,488.4
BEGIN DESCRIPTION:
Cross Section x31
END DESCRIPTION:
XS GIS Cut Line= 5
      3108613.37      13877433.6      3107743.07     13877149.54
      3106095.98     13875564.12      3105007.79     13874834.52
      3102774.88     13874373.07
#Sta/Elev= 30
  1730.8    76.5  1750.8    74.8  1940.8    74.4  2646.3    76.6  3576.3    76.3
  3666.3    73.9  3726.3    75.8  4086.3    73.6  4416.3    75.3  4543.3    73.9
  4916.3    74.9  4959.6   73.79  4977.3   73.66  4987.7   70.88  4993.9    63.5
    5001   62.98  5006.6   63.94  5007.6   66.17  5013.3   68.24  5020.7    74.2
  5035.2   75.17  5482.4    74.3  6182.4    78.3  6412.6    76.1  6512.6    77.6
  7032.6      77  7142.6    78.9  7762.6      78  7782.6    79.2  8522.7    79.7
#Mann= 7 ,-1 , 0
  1730.8      .1       0  4416.3     .08       0  4543.3     .08       0
  4959.6     .04       0  4987.7     .04       0  5020.7     .08       0
  5482.4      .1       0
#XS Ineff= 2 ,-1
  1730.8 4517.73   76.33 5742.24 6908.49   76.33
Permanent Ineff=
       F       F
Bank Sta=4916.3,5035.2
XS Rating Curve= 0
Exp/Cntr=.3,.1

Type RM Length L Ch R = 1 ,38579.00,115.6,108,102.2
BEGIN DESCRIPTION:
Cross Section Xsec 30c
END DESCRIPTION:
XS GIS Cut Line= 6
      3108698.93     13877438.41       3107845.9     13877065.21
      3106376.56     13875674.96      3106355.08     13875169.13
      3105402.09     13874506.53      3101853.96     13873802.98
#Sta/Elev= 30
  1664.8      76  1744.8    76.6  1764.8    74.6  1934.8    75.9  1974.8    74.1
  2504.8    76.8  3395.9    75.8  3465.9    73.7  3725.9    75.2  3915.9    73.2
  4275.9    75.2  4958.6   72.94  4976.2   72.74    4992   67.08  4994.5   63.34
  5000.1   63.13  5005.6   63.49  5020.4   73.79  5029.3   74.19  5526.5    74.8
  5576.5    76.8  5926.5    74.7  6056.5    74.7  6106.5    76.6  6577.2    75.2
  6727.2    76.5  6767.2    73.5  6807.2    76.4  7107.2    77.5  9904.4    80.5
#Mann= 7 ,-1 , 0
  1664.8      .1       0  4275.9     .08       0  4958.6     .04       0
  4976.2     .04       0  5020.4     .04       0  5029.3     .08       0
  5576.5      .1       0
#XS Ineff= 2 ,-1
 5563.44 6887.31   76.37 2537.43 4271.08   76.08
Permanent Ineff=
       F       F
#Block Obstruct= 2 , 0
       0 2505.44    76.8               0
Bank Sta=4976.2,5020.4
XS Rating Curve= 0
Exp/Cntr=.5,.3

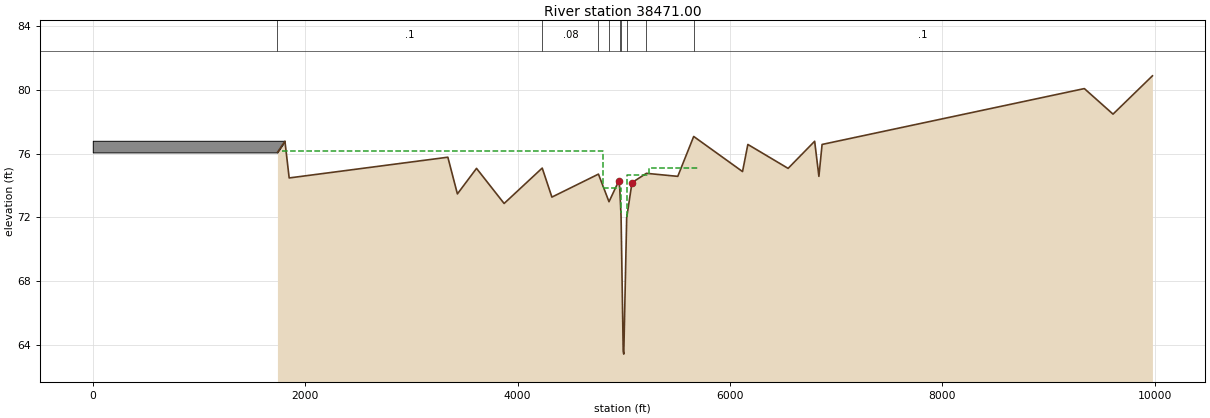
Type RM Length L Ch R = 1 ,38471.00,77.1,77,72.8
BEGIN DESCRIPTION:
STUEBNER AIRLINE u/s
Upstream Section of Bridge/Culvert/Weir
END DESCRIPTION:
XS GIS Cut Line= 6
       3108763.3      13877404.5      3107959.86     13876968.08
      3106495.61     13875653.78      3106471.62     13875146.53
      3105505.64     13874470.48      3101909.08     13873730.83
#Sta/Elev= 30
    1739   76.07  1809.7   76.77  1849.7   74.47    3344   75.77    3434   73.47
    3614   75.07    3874   72.87  4232.8   75.09    4324   73.27  4762.4   74.71
  4861.7   72.98  4955.9   74.31  4963.5   73.74  4975.5   72.05  4995.5   63.61
  5000.9   63.43  5028.2   71.97  5078.4   74.18  5214.1   74.76  5509.4   74.57
  5659.4   77.07  6119.4   74.87  6169.4   76.57  6548.5   75.07  6798.5   76.77
  6838.5   74.57  6868.5   76.57  9338.5   80.07  9608.5   78.47  9979.6   80.87
#Mann= 9 ,-1 , 0
    1739      .1       0  4232.8     .08       0  4762.4     .05       0
  4861.7     .08       0  4963.5     .04       0  4975.5     .04       0
  5028.2     .08       0  5214.1     .08       0  5659.4      .1       0
#XS Ineff= 5 ,-1
 1778.41 4806.93   76.18 5760.44 7375.89   75.95 5240.35 5705.28    75.1
    5030 5240.35   74.65 4806.93    4974   73.84
Permanent Ineff=
       F       F       F       F       F
#Block Obstruct= 2 , 0
       0 1809.47    76.8               0
Bank Sta=4955.9,5078.4
XS Rating Curve= 0
Exp/Cntr=.5,.3