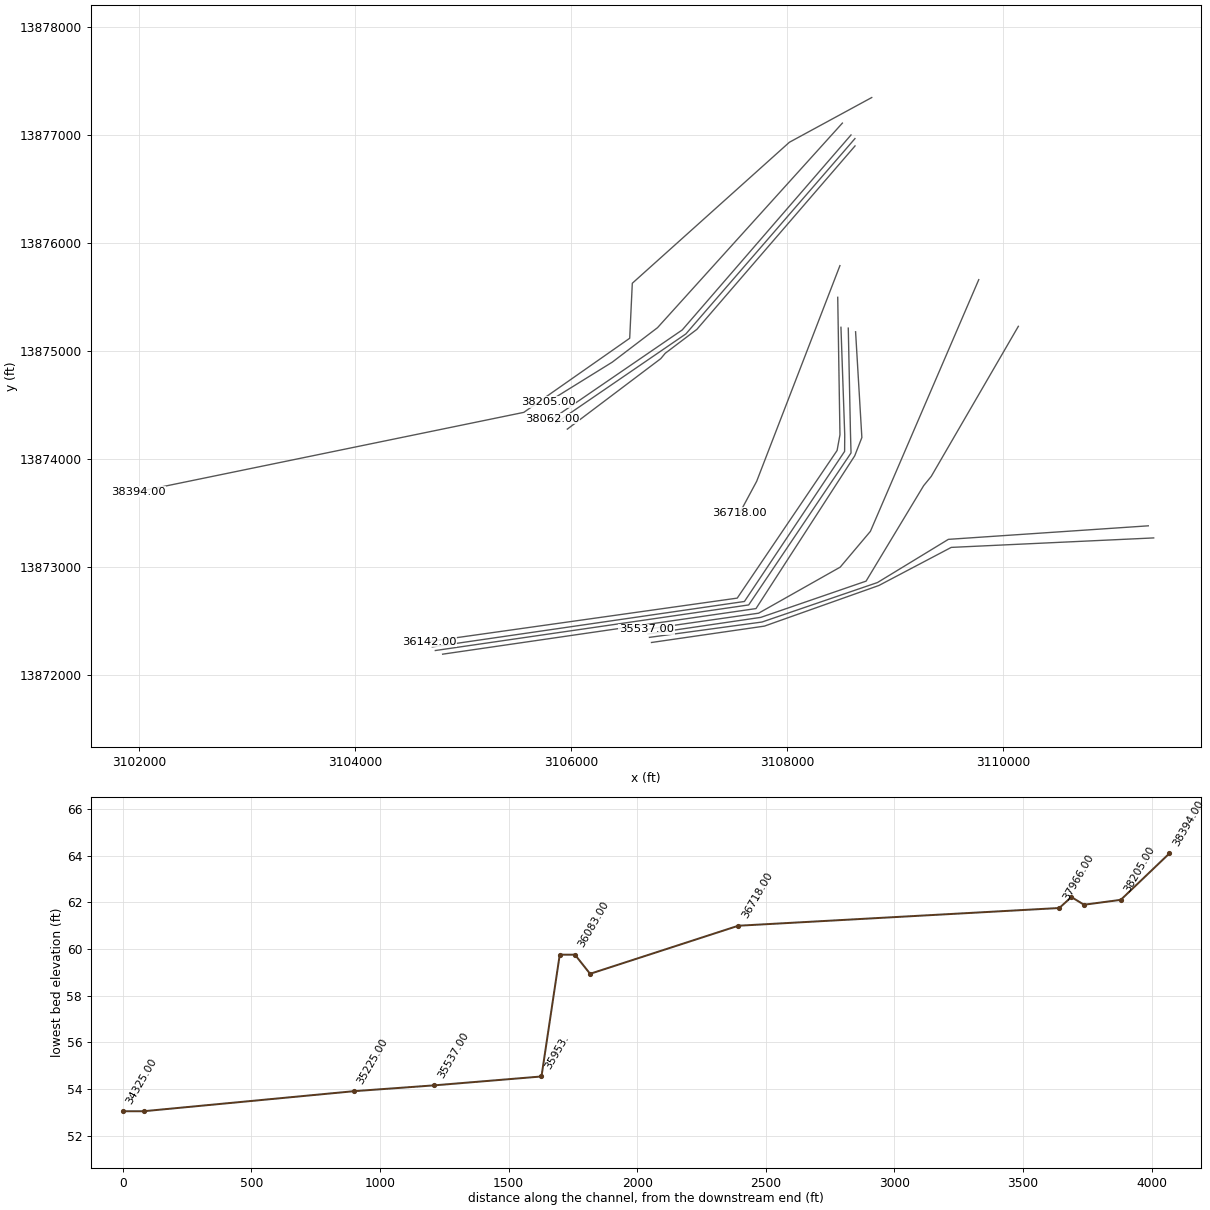
HEC-RAS study E101_00_00.prj: E101-00-00

--- E101_00_00.g01 (geometry) --- (continued)

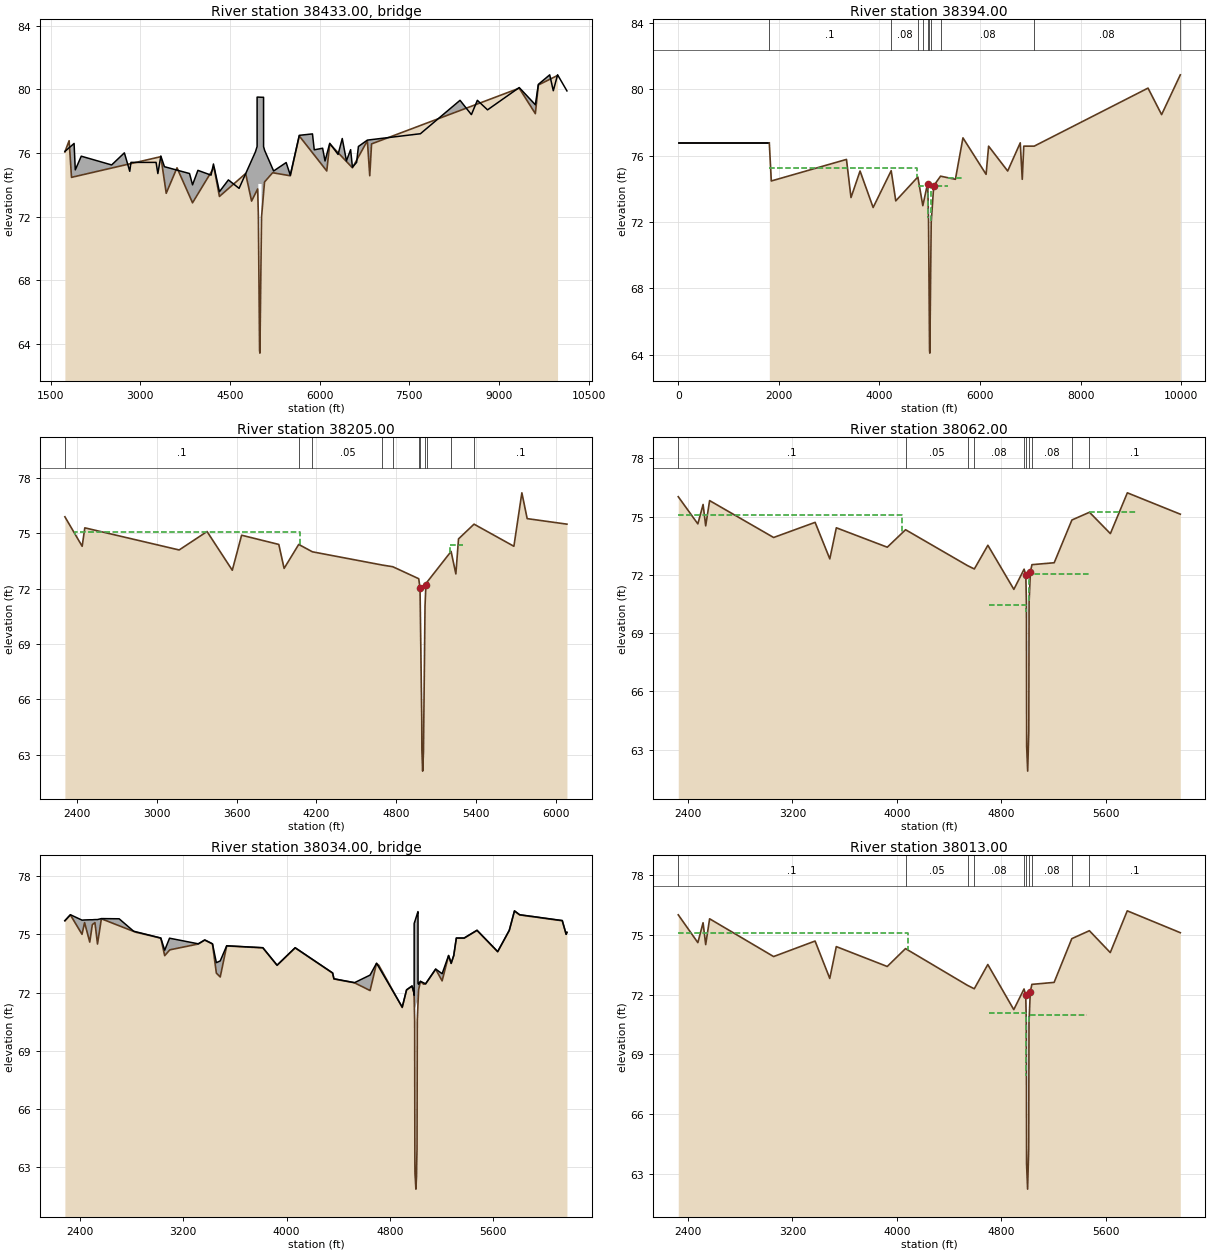
Type RM Length L Ch R = 3 ,38433.00,,,
BEGIN DESCRIPTION:
STUEBNER AIRLINE
Structure ID: E101-00-00-29
END DESCRIPTION:
Bridge Culvert--1,0,-1,-1, 0
Deck Dist Width WeirC Skew NumUp NumDn MinLoCord MaxHiCord MaxSubmerge Is_Ogee
10,56,2.6,0, 60, 60, , , .95, 0, ,,,
  1739.7  1892.8  1912.8  2012.8  2520.9    2734    2824    2844    3264    3294
    3344    3404    3824    3874    3964    4184    4224    4324    4474  4652.8
  4925.8 4953.99  4954.1  4970.2 4974.71  4974.8 5029.29  5029.4  5062.2 5062.31
  5080.5  5230.3  5440.2  5509.4  5659.4  5880.2  5910.2  6050.2  6090.2  6169.4
  6308.5  6378.5  6448.5  6518.5  6548.5  6618.5  6648.5  6798.5  7685.5  8348.5
  8538.5  8638.5  8808.5  9338.5  9608.5  9658.5  9848.5  9908.5  9980.3 10136.8
    76.1    76.6   74.94    75.8   75.25   76.01   74.85   75.41   75.41   74.71
   75.81   75.14   74.71      74   74.91   74.61   75.31   73.57   74.31   73.78
   76.07   76.41   79.51   79.51   79.51   79.51    79.5    79.5    79.5    76.4
   76.16   74.87    75.4   74.61   77.11    77.2    76.2    76.3    75.5   76.61
   75.91   76.91   75.51   76.21   75.11   75.41   76.41   76.81   77.21   79.31
   78.41   79.31   78.71   80.11   79.03   80.31   80.91   79.91   80.91    79.9
                                                                                
                                                                                
                                   72.26   74.06   74.05
                                                                                
                                                                                
                                                                                
  1739.7  1892.8  1912.8  2012.8  2520.9    2734    2824    2844    3264    3294
    3344    3404    3824    3874    3964    4184    4224    4324    4474  4652.8
  4925.8 4953.99  4954.1  4970.2 4974.71  4974.8 5029.29  5029.4  5062.2 5062.31
  5080.5  5230.3  5440.2  5509.4  5659.4  5880.2  5910.2  6050.2  6090.2  6169.4
  6308.5  6378.5  6448.5  6518.5  6548.5  6618.5  6648.5  6798.5  7685.5  8348.5
  8538.5  8638.5  8808.5  9338.5  9608.5  9658.5  9848.5  9908.5  9980.3 10136.8
    76.1    76.6   74.94    75.8   75.25   76.01   74.85   75.41   75.41   74.71
   75.81   75.14   74.71      74   74.91   74.61   75.31   73.57   74.31   73.78
   76.07   76.41   79.51   79.51   79.51   79.51    79.5    79.5    79.5    76.4
   76.16   74.87    75.4   74.61   77.11    77.2    76.2    76.3    75.5   76.61
   75.91   76.91   75.51   76.21   75.11   75.41   76.41   76.81   77.21   79.31
   78.41   79.31   78.71   80.11   79.03   80.31   80.91   79.91   80.91    79.9
                                                                                
                                                                                
                                   72.26   74.06   74.05
                                                                                
                                                                                
                                                                                
Abutment Skew #Up #Dn= , 2 , 2
  4974.6  4975.6
   74.06   72.06
  4974.6  4975.6
   74.06   72.06
Abutment Skew #Up #Dn= , 2 , 2
  5028.2 5029.49
      72   74.05
  5028.2 5029.49
      72   74.05
BR Coef= 1 , 1 , 0 ,1.25, 0 ,,,.8,0,2,0,
WSPro=,,,, 1 ,,,, 0 ,,,, 0 ,,,,-1 ,-1 ,-1 , 0 , 0 , 0 , 0 , 0
BR U #Sta/Elev= 30
    1739   76.07  1809.7   76.77  1849.7   74.47    3344   75.77    3434   73.47
    3614   75.07    3874   72.87  4232.8   75.09    4324   73.27  4762.4   74.71
  4861.7   72.98  4963.5   73.74  4975.5   72.05  4995.5   63.61  5000.9   63.43
  5028.2   71.97  5078.4   74.18  5214.1   74.76  5509.4   74.57  5659.4   77.07
  6119.4   74.87  6169.4   76.57  6548.5   75.07  6798.5   76.77  6838.5   74.57
  6868.5   76.57  9338.5   80.07  9608.5   78.47  9658.5   80.27  9979.6   80.87
BR U #Mann= 9
    1739      .1  4232.8     .08  4762.4     .05  4861.7     .08  4963.5     .04
  4975.5    .015  5028.2     .08  5214.1     .08  5659.4      .1
BR D #Sta/Elev= 30
  1809.7   76.77  1849.7   74.47    3344   75.77    3434   73.47    3614   75.07
    3874   72.87  4232.8   75.09    4324   73.27  4762.4   74.71  4861.7   72.98
  4963.5   73.74  4975.5   72.05  4995.5   64.27  5000.9   64.09  5028.2   71.97
  5078.4   74.18  5214.1   74.76  5509.4   74.57  5659.4   77.07  6119.4   74.87
  6169.4   76.57  6548.5   75.07  6798.5   76.77  6838.5   74.57  6868.5   76.57
  7075.7   76.57  9338.5   80.07  9608.5   78.47  9658.5   80.27  9980.3   80.87
BR D #Mann= 9
  1809.7      .1  4232.8     .08  4762.4     .05  4861.7     .08  4963.5     .04
  4975.5    .015  5028.2     .08  5214.1     .08  7075.7     .08
BC Design=,, 0 ,, 0 ,,,,,,
BC HTab HWMax=80.87

Type RM Length L Ch R = 1 ,38394.00,401,189,84.8
BEGIN DESCRIPTION:
STUEBNER AIRLINE
Downstream Section of Bridge/Culvert/Weir
END DESCRIPTION:
XS GIS Cut Line= 6
 3108785.141875813877349.9931141      3108022.77     13876935.87
      3106568.48     13875630.51      3106544.41     13875121.43
      3105564.13     13874435.38 3101996.106695313873701.5993175
#Sta/Elev= 30
  1809.7   76.77  1849.7   74.47    3344   75.77    3434   73.47    3614   75.07
    3874   72.87  4232.8   75.09    4324   73.27  4762.4   74.71  4861.7   72.98
  4955.9   74.31  4963.5   73.74  4975.5   72.05  4995.5   64.27  5000.9   64.09
  5028.2   71.97  5078.4   74.18  5214.1   74.76  5509.4   74.57  5659.4   77.07
  6119.4   74.87  6169.4   76.57  6548.5   75.07  6798.5   76.77  6838.5   74.57
  6868.5   76.57  7075.7   76.57  9338.5   80.07  9608.5   78.47  9980.3   80.87
#Mann= 10 ,-1 , 0
  1809.7      .1       0  4232.8     .08       0  4762.4     .05       0
  4861.7     .08       0  4963.5     .04       0  4975.5     .04       0
  5028.2     .08       0  5214.1     .08       0  7075.7     .08       0
  9980.3      .1       0
#XS Ineff= 5 ,-1
 5791.96  7249.8   75.59  1809.7 4754.93   75.28 5369.78  5641.4   74.66
    5030 5369.78   74.18 4762.84    4974   74.18
Permanent Ineff=
       F       F       F       F       F
#Block Obstruct= 2 , 0
       0 1809.47    76.8               0
Bank Sta=4955.9,5078.4
XS Rating Curve= 0
Exp/Cntr=.5,.3

Type RM Length L Ch R = 1 ,38205.00,184.1,143,137.2
BEGIN DESCRIPTION:
Cross Section Xsec 30b
END DESCRIPTION:
XS GIS Cut Line= 4
      3108513.33      13877113.3      3106801.92     13875219.34
       3106382.8     13874900.06      3105788.28     13874531.84
#Sta/Elev= 30
  2307.1    75.9  2437.1    74.3  2457.1    75.3  3167.1    74.1  3377.1    75.1
  3567.1      73  3637.1    74.9  3917.1    74.4  3957.1    73.1  4067.1    74.4
    4170      74  4697.1   73.28  4775.2   73.19  4970.3   72.54  4980.1   72.03
  4993.3   64.85    4994   63.26  4999.9    62.1    5006   63.15  5017.8   71.09
  5024.5    72.2  5030.1   72.33  5213.9   74.02  5249.8    72.8  5269.8    74.7
  5386.6    75.5  5686.6    74.3  5746.6    77.2  5786.6    75.8  6085.9    75.5
#Mann= 11 ,-1 , 0
  2307.1      .1       0  4067.1     .08       0    4170     .05       0
  4697.1     .04       0  4775.2     .08       0  4970.3     .04       0
  4980.1     .04       0  5017.8     .04       0  5030.1     .08       0
  5213.9     .08       0  5386.6      .1       0
#XS Ineff= 3 ,-1
 5392.44 5821.91   75.37 2386.13 4080.38   75.08 5207.25 5301.81   74.35
Permanent Ineff=
       F       F       F
Bank Sta=4980.1,5024.5
XS Rating Curve= 0
Exp/Cntr=.5,.3

Type RM Length L Ch R = 1 ,38062.00,48.9,49,49.9
BEGIN DESCRIPTION:
SURRATT u/s
Upstream Section of Bridge/Culvert/Weir
END DESCRIPTION:
XS GIS Cut Line= 3
 3108593.170920413877003.4293761      3107031.17     13875198.69
      3105829.64     13874376.09
#Sta/Elev= 30
  2326.3   76.02  2476.3   74.62  2516.3   75.62  2536.3   74.52  2566.3   75.82
  3056.3   73.92  3373.8    74.7  3486.3   72.82  3536.3   74.42  3926.3   73.42
  4066.3   74.32    4541   72.47  4592.8    72.3  4696.3   73.52  4895.2   71.25
  4973.6   72.29  4986.8   71.97  4991.4   70.51  4993.2   63.15    5001   61.89
  5009.6   63.95  5011.7   70.58  5021.7   72.15  5033.7   72.52    5204   72.62
  5339.4   74.82    5474   75.22    5634   74.12    5764   76.22  6169.3   75.12
#Mann= 10 ,-1 , 0
  2326.3      .1       0  4066.3     .05       0    4541     .04       0
  4592.8     .08       0  4973.6     .04       0  4991.4     .04       0
  5011.7     .04       0  5033.7     .08       0  5339.4     .08       0
    5474      .1       0
#XS Ineff= 5 ,-1
 5471.24 5829.79   75.22  2326.3 4037.04   75.06
    5012 5471.24   72.04 4702.92 4991.51   70.44
Permanent Ineff=
       F       F       F       F       F
#Block Obstruct= 2 , 0
                         5757.76           76.23
Bank Sta=4986.8,5021.7
XS Rating Curve= 0
Exp/Cntr=.5,.3

Type RM Length L Ch R = 3 ,38034.00,,,
BEGIN DESCRIPTION:
SURRATT
Structure ID: E101-00-00-28
END DESCRIPTION:
Bridge Culvert--1,0,-1,-1, 0
Deck Dist Width WeirC Skew NumUp NumDn MinLoCord MaxHiCord MaxSubmerge Is_Ogee
10,36,2.6,0, 60, 60, , , .95, 0, ,,,
  2283.8  2326.3  2416.3  2436.3  2476.3  2496.3  2516.3  2536.3  2566.3  2703.8
  2815.7  3026.3  3056.3  3093.8  3316.3  3366.3  3426.3  3456.3  3486.3  3536.3
  3816.3  3926.3  4066.3  4356.3  4366.3  4526.3  4646.3  4696.3  4895.2  4928.7
  4971.2  4986.8 4987.39  4987.5  4991.4 4991.51  4991.6 5012.19  5012.3 5017.19
  5017.3 5017.41  5021.7  5035.8  5075.9    5154    5204    5254    5274    5294
    5314    5374    5474    5634    5724    5764    5804    6134    6164  6170.2
    75.7   76.01   75.73   75.74   75.75   75.75   75.76   75.76   75.81    75.8
   75.16   74.81   74.18    74.8   74.51   74.71   74.51   73.54   73.63   74.41
   74.31   73.41   74.31   73.01   72.71   72.51    72.9   73.51   71.25   72.14
   72.34   71.96   71.86   75.56   75.64   75.64   75.64   76.07   76.07   76.17
   76.17   72.47   72.42   72.58   72.45   73.21   72.97   73.91   73.51   73.91
   74.81   74.81   75.21   74.11   75.21   76.21   76.01   75.71      75    75.1
    75.7      76      75    75.6    74.6    75.5    75.6    74.5    75.8   75.44
   75.15    74.8    73.9   74.18    74.5    74.7    74.5      73    72.8    74.4
    74.3    73.4    74.3      73    72.7    72.5    72.1    73.5   71.23   72.13
   72.33   71.95   71.76   71.73   70.49   70.04   71.14   71.57   70.65   71.42
   71.44   71.46   72.13   72.57   72.44    73.2    72.6    73.9    73.5    73.9
    74.8    74.8    75.2    74.1    75.2    76.2      76    75.7      75    75.1
  2283.8  2326.3  2416.3  2436.3  2476.3  2496.3  2516.3  2536.3  2566.3  2703.8
  2815.7  3026.3  3056.3  3093.8  3316.3  3366.3  3426.3  3456.3  3486.3  3536.3
  3816.3  3926.3  4066.3  4356.3  4366.3  4526.3  4646.3  4696.3  4895.2  4928.7
  4971.2  4986.8 4987.39  4987.5  4991.4 4991.51  4991.6 5012.19  5012.3 5017.19
  5017.3 5017.41  5021.7  5035.8  5075.9    5154    5204    5254    5274    5294
    5314    5374    5474    5634    5724    5764    5804    6134    6164  6170.2
    75.7   76.01   75.73   75.74   75.75   75.75   75.76   75.76   75.81    75.8
   75.16   74.81   74.18    74.8   74.51   74.71   74.51   73.54   73.63   74.41
   74.31   73.41   74.31   73.01   72.71   72.51    72.9   73.51   71.25   72.14
   72.34   71.96   71.86   75.56   75.64   75.64   75.64   76.07   76.07   76.17
   76.17   72.47   72.42   72.58   72.45   73.21   72.97   73.91   73.51   73.91
   74.81   74.81   75.21   74.11   75.21   76.21   76.01   75.71      75    75.1
    75.7      76      75    75.6    74.6    75.5    75.6    74.5    75.8   75.44
   75.15    74.8    73.9   74.18    74.5    74.7    74.5      73    72.8    74.4
    74.3    73.4    74.3      73    72.7    72.5    72.1    73.5   71.23   72.13
   72.33   71.95   71.76   71.73   70.49   70.04   71.14   71.57   70.65   71.42
   71.44   71.46   72.13   72.57   72.44    73.2    72.6    73.9    73.5    73.9
    74.8    74.8    75.2    74.1    75.2    76.2      76    75.7      75    75.1
BR Coef= 1 , 1 , 0 ,1.25, 0 ,,,.8,0,2,0,
WSPro=,,,, 1 ,,,, 0 ,,,, 0 ,,,,-1 ,-1 ,-1 , 0 , 0 , 0 , 0 , 0
BR U #Sta/Elev= 112
  2283.8    75.7  2326.3      76  2416.3      75  2436.3    75.6  2476.3    74.6
  2496.3    75.5  2516.3    75.6  2536.3    74.5  2566.3    75.8  2703.8   75.44
  2815.7   75.15  2836.3    75.1  2863.8   75.06  2983.8   74.87  3013.8   74.82
  3026.3    74.8  3033.8   74.58  3056.3    73.9  3093.8   74.18  3096.3    74.2
  3316.3    74.5  3366.3    74.7  3373.8   74.68  3403.8   74.58  3426.3    74.5
  3456.3      73  3486.3    72.8  3536.3    74.4  3733.8   74.33  3793.8   74.31
  3816.3    74.3  3926.3    73.4  3985.3   73.78  4066.3    74.3  4356.3      73
  4366.3    72.7  4443.8    72.6  4453.8   72.59  4526.3    72.5    4541   72.45
  4592.8   72.28  4646.3    72.1  4647.4   72.13  4696.3    73.5    4714    73.4
  4727.4   73.24  4827.4   72.04  4895.2   71.23  4928.7   72.13  4955.9   72.26
  4971.2   72.33  4973.6   72.27  4986.8   71.95 4987.39   71.76  4987.5   71.73
 4987.61   71.69  4991.4   70.49 4991.51   70.04  4991.6   69.67  4991.7   69.26
  4993.2   63.13    4994   62.68    5001   61.87  5005.8   62.55  5006.9    63.1
  5009.6   63.93  5011.7   70.56  5012.1   70.62 5012.19   70.64  5012.3   70.65
 5017.19   71.42  5017.3   71.44 5017.41   71.46  5021.7   72.13  5033.7    72.5
  5035.8   72.57  5039.9   72.55  5060.6   72.43  5075.9   72.44    5154    73.2
    5204    72.6    5254    73.9    5274    73.5  5277.4   73.57    5294    73.9
  5307.4    74.5    5314    74.8  5337.4    74.8  5339.4    74.8  5357.4    74.8
    5374    74.8  5377.4   74.81    5474    75.2  5497.4   75.04  5539.9   74.75
  5557.4   74.63    5634    74.1    5724    75.2    5764    76.2  5767.5   76.18
  5777.4   76.13  5797.4   76.03    5804      76  5887.4   75.92  5907.4   75.91
  5987.4   75.83  6097.4   75.73    6134    75.7  6161.8   75.05  6161.9   75.05
    6164      75  6170.2    75.1
BR U #Mann= 10
  2283.8     .99  4066.3     .05    4541     .04  4592.8     .08  4973.6     .04
  4991.4     .04  5011.7     .04  5033.7     .08  5339.4     .08    5474     .99
BR U Banks=4991.4,5011.7
BR D #Sta/Elev= 112
  2283.8   75.72  2326.3   76.02  2416.3   75.02  2436.3   75.62  2476.3   74.62
  2496.3   75.52  2516.3   75.62  2536.3   74.52  2566.3   75.82  2703.8   75.46
  2815.7   75.17  2836.3   75.12  2863.8   75.08  2983.8   74.89  3013.8   74.84
  3026.3   74.82  3033.8    74.6  3056.3   73.92  3093.8    74.2  3096.3   74.22
  3316.3   74.52  3366.3   74.72  3373.8    74.7  3403.8    74.6  3426.3   74.52
  3456.3   73.02  3486.3   72.82  3536.3   74.42  3733.8   74.35  3793.8   74.33
  3816.3   74.32  3926.3   73.42  3985.3    73.8  4066.3   74.32  4356.3   73.02
  4366.3   72.72  4443.8   72.62  4453.8   72.61  4526.3   72.52    4541   72.47
  4592.8    72.3  4646.3   72.12  4647.4   72.15  4696.3   73.52    4714   73.42
  4727.4   73.26  4827.4   72.06  4895.2   71.25  4928.7   72.15  4955.9   72.28
  4971.2   72.35  4973.6   72.29  4986.8   71.97 4987.39   71.78  4987.5   71.75
 4987.61   71.71  4991.4   70.51 4991.51   70.39  4991.6   70.02  4991.7   69.61
  4993.2   63.48    4994   63.03    5001   62.22  5005.8    62.9  5006.9   63.45
  5009.6   64.28  5011.7   70.58  5012.1   70.64 5012.19   70.66  5012.3   70.67
 5017.19   71.44  5017.3   71.46 5017.41   71.48  5021.7   72.15  5033.7   72.52
  5035.8   72.59  5039.9   72.57  5060.6   72.45  5075.9   72.46    5154   73.22
    5204   72.62    5254   73.92    5274   73.52  5277.4   73.59    5294   73.92
  5307.4   74.52    5314   74.82  5337.4   74.82  5339.4   74.82  5357.4   74.82
    5374   74.82  5377.4   74.83    5474   75.22  5497.4   75.06  5539.9   74.77
  5557.4   74.65    5634   74.12    5724   75.22    5764   76.22  5767.5    76.2
  5777.4   76.15  5797.4   76.05    5804   76.02  5887.4   75.94  5907.4   75.93
  5987.4   75.85  6097.4   75.75    6134   75.72  6161.8   75.07  6161.9   75.07
    6164   75.02  6170.2   75.12
BR D #Mann= 10
  2283.8     .99  4066.3     .05    4541     .04  4592.8     .08  4973.6     .04
  4991.4     .04  5011.7     .04  5033.7     .08  5339.4     .08    5474     .99
BR D Banks=4991.4,5011.7
BC Design=,, 0 ,, 0 ,,,,,,
BC HTab HWMax=76.22

Type RM Length L Ch R = 1 ,38013.00,42.6,47,62.6
BEGIN DESCRIPTION:
SURRATT
Downstream Section of Bridge/Culvert/Weir
END DESCRIPTION:
XS GIS Cut Line= 3
      3108629.69      13876969.8      3107064.98     13875162.01
      3105860.79     13874337.59
#Sta/Elev= 30
  2326.3   76.02  2476.3   74.62  2516.3   75.62  2536.3   74.52  2566.3   75.82
  3056.3   73.92  3373.8    74.7  3486.3   72.82  3536.3   74.42  3926.3   73.42
  4066.3   74.32    4541   72.47  4592.8    72.3  4696.3   73.52  4895.2   71.25
  4973.6   72.29  4986.8   71.97  4991.4   70.51  4993.2   63.48    5001   62.22
  5009.6   64.28  5011.7   70.58  5021.7   72.15  5033.7   72.52    5204   72.62
  5339.4   74.82    5474   75.22    5634   74.12    5764   76.22  6170.2   75.12
#Mann= 10 ,-1 , 0
  2326.3      .1       0  4066.3     .05       0    4541     .04       0
  4592.8     .08       0  4973.6     .04       0  4991.4     .04       0
  5011.7     .04       0  5033.7     .08       0  5339.4     .08       0
    5474      .1       0
#XS Ineff= 4 ,-1
  2326.3 4088.26   75.08 5455.48 5857.37   75.04 4702.92 4992.06   71.08
    5012 5455.48      71
Permanent Ineff=
       F       F       F       F
Bank Sta=4986.8,5021.7
XS Rating Curve= 0
Exp/Cntr=.5,.3

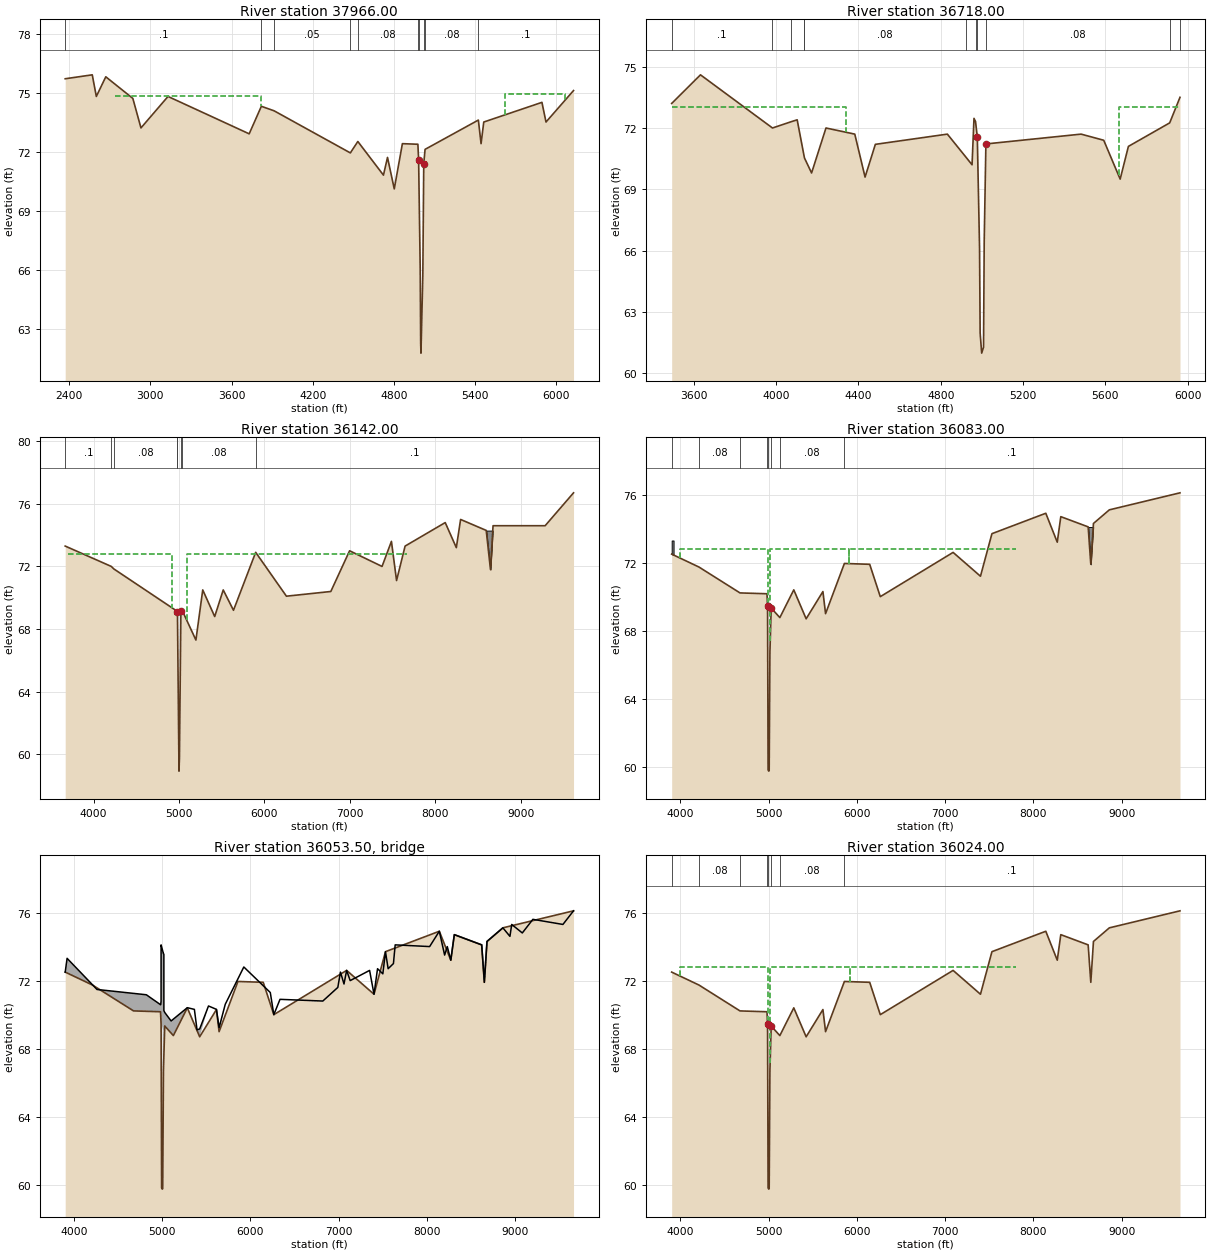
Type RM Length L Ch R = 1 ,37966.00,1052.6,1248,1321.2
BEGIN DESCRIPTION:
Cross Section Xsec 30a
END DESCRIPTION:
XS GIS Cut Line= 5
 3108630.4812676 13876901.936785      3107166.11     13875203.58
      3106873.52     13874982.53      3106831.99     13874932.68
      3105966.97     13874280.21
#Sta/Elev= 30
  2370.3    75.7  2570.3    75.9  2600.3    74.8  2670.3    75.8  2870.3    74.7
  2930.3    73.2  3130.3    74.8  3730.3    72.9  3820.3    74.3  3914.6   74.07
    4478   71.93  4533.5   72.51  4722.8    70.8  4752.8    71.7  4802.8    70.1
  4862.8    72.4  4977.4   72.37  4982.8   71.57  4994.5   66.04  4997.9   62.26
  5000.1   61.75  5013.9   65.73  5020.7   71.37  5030.4   72.11  5424.4    73.6
  5444.4    72.4  5464.4    73.5  5894.4    74.5  5924.4    73.5  6127.9    75.1
#Mann= 10 ,-1 , 0
  2370.3      .1       0  3820.3     .08       0  3914.6     .05       0
    4478     .04       0  4533.5     .08       0  4977.4     .04       0
  4982.8    .045       0  5020.7     .04       0  5030.4     .08       0
  5424.4      .1       0
#XS Ineff= 2 ,-1
  5624.9 6066.19   74.92  2736.8  3820.3    74.8
Permanent Ineff=
       F       F
Bank Sta=4982.8,5020.7
XS Rating Curve= 0
Exp/Cntr=.3,.1

Type RM Length L Ch R = 1 ,36718.00,645.7,576.03,637.3
BEGIN DESCRIPTION:
Cross Section XS30
END DESCRIPTION:
XS GIS Cut Line= 3
       3108490.6     13875793.66        3107720.     13873797.29
      3107563.59     13873505.89
#Sta/Elev= 30
  3492.2    73.2  3632.2    74.6  3982.2      72    4074   72.31  4102.2    72.4
  4137.1   70.56  4137.4   70.54  4172.2    69.8  4242.2      72  4382.2    71.7
  4432.2    69.6  4482.2    71.2  4832.2    71.7    4922   70.58  4952.2    70.2
  4961.6   72.47    4969   72.32  4977.7   71.57  4988.6   66.15  4991.5   61.97
    4999   60.99    5008   61.28  5011.3   66.47  5019.5   71.22  5482.2    71.7
  5592.2    71.4  5672.1    69.5  5712.1    71.1  5912.8   72.25  5962.9    73.5
#Mann= 11 ,-1 , 0
  3492.2      .1       0  3982.2     .05       0    4074     .08       0
  4137.1     .05       0  4137.4     .08       0    4922     .08       0
    4969     .04       0  4977.7     .04       0  5019.5     .08       0
  5912.8      .1       0  5962.9      .1       0
#XS Ineff= 2 , 0
       0 4341.36   73.04 5664.36       0   73.04
Permanent Ineff=
       F       F
Bank Sta=4977.7,5019.5
XS Rating Curve= 0
Exp/Cntr=.3,.1

Type RM Length L Ch R = 1 ,36142.00,57.9,59,88.4
BEGIN DESCRIPTION:
Cross Section Xsec 29b
END DESCRIPTION:
XS GIS Cut Line= 5
      3108470.29     13875500.56      3108490.98     13874227.58
      3108464.29     13874082.32      3107539.93      13872715.7
      3104685.52     13872313.45
#Sta/Elev= 30
  3666.5    73.3  4206.5      72  4236.3   71.84  4980.2   69.13  4981.1    69.1
  4999.2   58.93  5004.4   59.78  5021.5   69.15  5029.1   69.28  5197.3    67.3
  5277.3    70.5  5417.3    68.8  5517.3    70.5  5637.3    69.2  5897.3    72.9
  6257.3    70.1  6777.2    70.4  6997.2      73  7377.2      72  7487.2    73.6
  7547.2    71.1  7647.2    73.3  8117.2    74.8  8247.2    73.2  8297.2      75
  8597.2    74.3  8647.2    71.8  8677.2    74.6  9287.2    74.6  9619.8    76.7
#Mann= 8 ,-1 , 0
  3666.5      .1       0  4206.5     .05       0  4236.3     .08       0
  4980.2     .04       0  4981.1    .045       0  5021.5     .04       0
  5029.1     .08       0  5897.3      .1       0
#XS Ineff= 2 ,-1
    3700 4917.36    72.8 5088.36    7675    72.8
Permanent Ineff=
       F       F
#Block Obstruct= 1 ,-1
 8596.94 8695.65   74.29
Bank Sta=4981.1,5021.5
XS Rating Curve= 0
Exp/Cntr=.5,.3

Type RM Length L Ch R = 1 ,36083.00,58.3,59,59.1
BEGIN DESCRIPTION:
YALE u/s
Upstream Section of Bridge/Culvert/Weir
END DESCRIPTION:
XS GIS Cut Line= 5
      3108500.19     13875222.99      3108535.13     13874227.25
      3108534.04      13874074.2      3107606.62     13872684.63
      3104716.66     13872264.12
#Sta/Elev= 30
  3901.5    72.5  4210.6   71.74  4675.6   70.22  4981.4   70.17  4987.8   69.43
  4993.8   59.82  5001.3   59.75  5006.1   59.78  5014.5   66.72  5029.1   69.34
  5029.5   69.33  5126.9   68.77  5284.9    70.4  5424.9    68.7  5614.9    70.3
  5644.9      69  5858.4   71.95  6144.9    71.9  6264.9      70  7089.8    72.6
  7399.8    71.2  7529.8    73.7  8139.8    74.9  8269.8    73.2  8309.8    74.7
  8619.8    74.1  8649.8    71.9  8679.8    74.3  8859.8    75.1  9660.2    76.1
#Mann= 8 ,-1 , 0
  3901.5     .05       0  4210.6     .08       0  4675.6     .08       0
  4981.4     .04       0  4987.8    .015       0  5029.5     .08       0
  5126.9     .08       0  5858.4      .1       0
#XS Ineff= 3 ,-1
    4000 4987.36    72.8 5018.36    5910    72.8    5910    7800    72.8
Permanent Ineff=
       F       F       F
#Block Obstruct= 2 ,-1
  3901.5 3922.77    73.3  8618.8 8684.19   74.09
Bank Sta=4987.8,5029.1
XS Rating Curve= 0
Exp/Cntr=.5,.3

Type RM Length L Ch R = 3 ,36053.50,,,
BEGIN DESCRIPTION:
YALE and Pipeline 7 ft downstream
Structure ID: E101-00-00-27
END DESCRIPTION:
Bridge Culvert--1,0,-1,-1, 0
Deck Dist Width WeirC Skew NumUp NumDn MinLoCord MaxHiCord MaxSubmerge Is_Ogee
10,39,2.6,0, 60, 60, , , .95, 0, ,,,
  3901.5  3922.8  4261.5  4819.3  4825.9    4983 4987.39  4987.5  4987.8 4992.31
  4992.4 5012.49  5012.6  5014.5  5019.3 5019.41  5029.1  5101.2  5284.9  5364.9
  5394.9  5424.9  5524.9  5614.9  5644.9  5714.7  5924.9  6224.9  6264.9  6334.9
  6819.8  6989.8  7019.8  7059.8  7089.8  7129.8  7349.8  7399.8  7439.8  7499.8
  7529.8  7559.8  7619.8  7639.8  8029.8  8139.8  8199.8  8229.8  8269.8  8309.8
  8619.8  8649.8  8679.8  8859.8  8939.8  8959.8  9079.8  9199.8  9539.8  9660.2
    72.5   73.31   71.48   71.17   71.15   70.58   70.79   74.09    74.1   74.01
   74.01   73.62   73.62   73.59   73.54   70.24   70.13   69.63   70.41   70.31
   69.11   69.16   70.51   70.31   69.24   70.61    72.8    71.3      70    70.9
    70.8    71.6    72.5    71.8    72.6      72    72.6    71.2    72.7    72.4
    73.7    72.7      73    74.1      74    74.9    73.5      74    73.2    74.7
    74.1    71.9    74.3    75.1    74.6    75.3    74.8    75.6    75.3    76.1
                                   69.86    70.2    69.5   69.48   69.43   62.08
   69.46   69.07   65.26   66.72   67.58    67.6   69.34   68.56    70.4    70.3
    69.1    68.7    70.5    70.3      69    70.6    72.8    71.3      70    70.9
    70.8    71.6    72.5    71.8    72.6      72    72.6    71.2    72.7    72.4
    73.7    72.7      73    74.1      74    74.9    73.5      74    73.2    74.7
    74.1    71.9    74.3    75.1    74.6    75.3    74.8    75.6    75.3    76.1
  3901.5  3922.8  4261.5  4819.3  4825.9    4983 4987.39  4987.5  4987.8 4992.31
  4992.4 5012.49  5012.6  5014.5  5019.3 5019.41  5029.1  5101.2  5284.9  5364.9
  5394.9  5424.9  5524.9  5614.9  5644.9  5714.7  5924.9  6224.9  6264.9  6334.9
  6819.8  6989.8  7019.8  7059.8  7089.8  7129.8  7349.8  7399.8  7439.8  7499.8
  7529.8  7559.8  7619.8  7639.8  8029.8  8139.8  8199.8  8229.8  8269.8  8309.8
  8619.8  8649.8  8679.8  8859.8  8939.8  8959.8  9079.8  9199.8  9539.8  9660.2
    72.5   73.31   71.48   71.17   71.15   70.58   70.79   74.09    74.1   74.01
   74.01   73.62   73.62   73.59   73.54   70.24   70.13   69.63   70.41   70.31
   69.11   69.16   70.51   70.31   69.24   70.61    72.8    71.3      70    70.9
    70.8    71.6    72.5    71.8    72.6      72    72.6    71.2    72.7    72.4
    73.7    72.7      73    74.1      74    74.9    73.5      74    73.2    74.7
    74.1    71.9    74.3    75.1    74.6    75.3    74.8    75.6    75.3    76.1
                                   69.86    70.2    69.5   69.48   69.43   62.08
   69.46   69.07   65.26   66.72   67.58    67.6   69.34   68.56    70.4    70.3
    69.1    68.7    70.5    70.3      69    70.6    72.8    71.3      70    70.9
    70.8    71.6    72.5    71.8    72.6      72    72.6    71.2    72.7    72.4
    73.7    72.7      73    74.1      74    74.9    73.5      74    73.2    74.7
    74.1    71.9    74.3    75.1    74.6    75.3    74.8    75.6    75.3    76.1
BR Coef= 1 , 1 , 0 ,1.25, 0 ,,,.8,-1,2,0,
WSPro=,,,, 1 ,,,, 0 ,,,, 0 ,,,,-1 ,-1 ,-1 , 0 , 0 , 0 , 0 , 0
BC Design=,, 0 ,, 0 ,,,,,,
BC HTab HWMax=76.1

Type RM Length L Ch R = 1 ,36024.00,80.4,71,58.7
BEGIN DESCRIPTION:
YALE
Downstream Section of Bridge/Culvert/Weir
END DESCRIPTION:
XS GIS Cut Line= 5
      3108567.96     13875215.17      3108587.91      13874259.3
      3108593.43      13874059.7      3107645.94     13872652.63
       3104744.9     13872230.51
#Sta/Elev= 30
  3901.5    72.5  4210.6   71.74  4675.6   70.22  4981.4   70.17  4987.8   69.43
  4993.8   59.82  5001.3   59.75  5006.1   59.78  5014.5   66.72  5029.1   69.34
  5029.5   69.33  5126.9   68.77  5284.9    70.4  5424.9    68.7  5614.9    70.3
  5644.9      69  5858.4   71.95  6144.9    71.9  6264.9      70  7089.8    72.6
  7399.8    71.2  7529.8    73.7  8139.8    74.9  8269.8    73.2  8309.8    74.7
  8619.8    74.1  8649.8    71.9  8679.8    74.3  8859.8    75.1  9660.2    76.1
#Mann= 8 ,-1 , 0
  3901.5     .05       0  4210.6     .08       0  4675.6     .08       0
  4981.4     .04       0  4987.8    .015       0  5029.5     .08       0
  5126.9     .08       0  5858.4      .1       0
#XS Ineff= 3 ,-1
  5924.9    7800    72.8    4000 4987.13    72.8  5017.1  5924.9    72.8
Permanent Ineff=
       F       F       F
#Block Obstruct= 2 , 0
          3922.8    73.3 8619.51            74.1
Bank Sta=4987.8,5029.1
XS Rating Curve= 0
Exp/Cntr=.5,.3

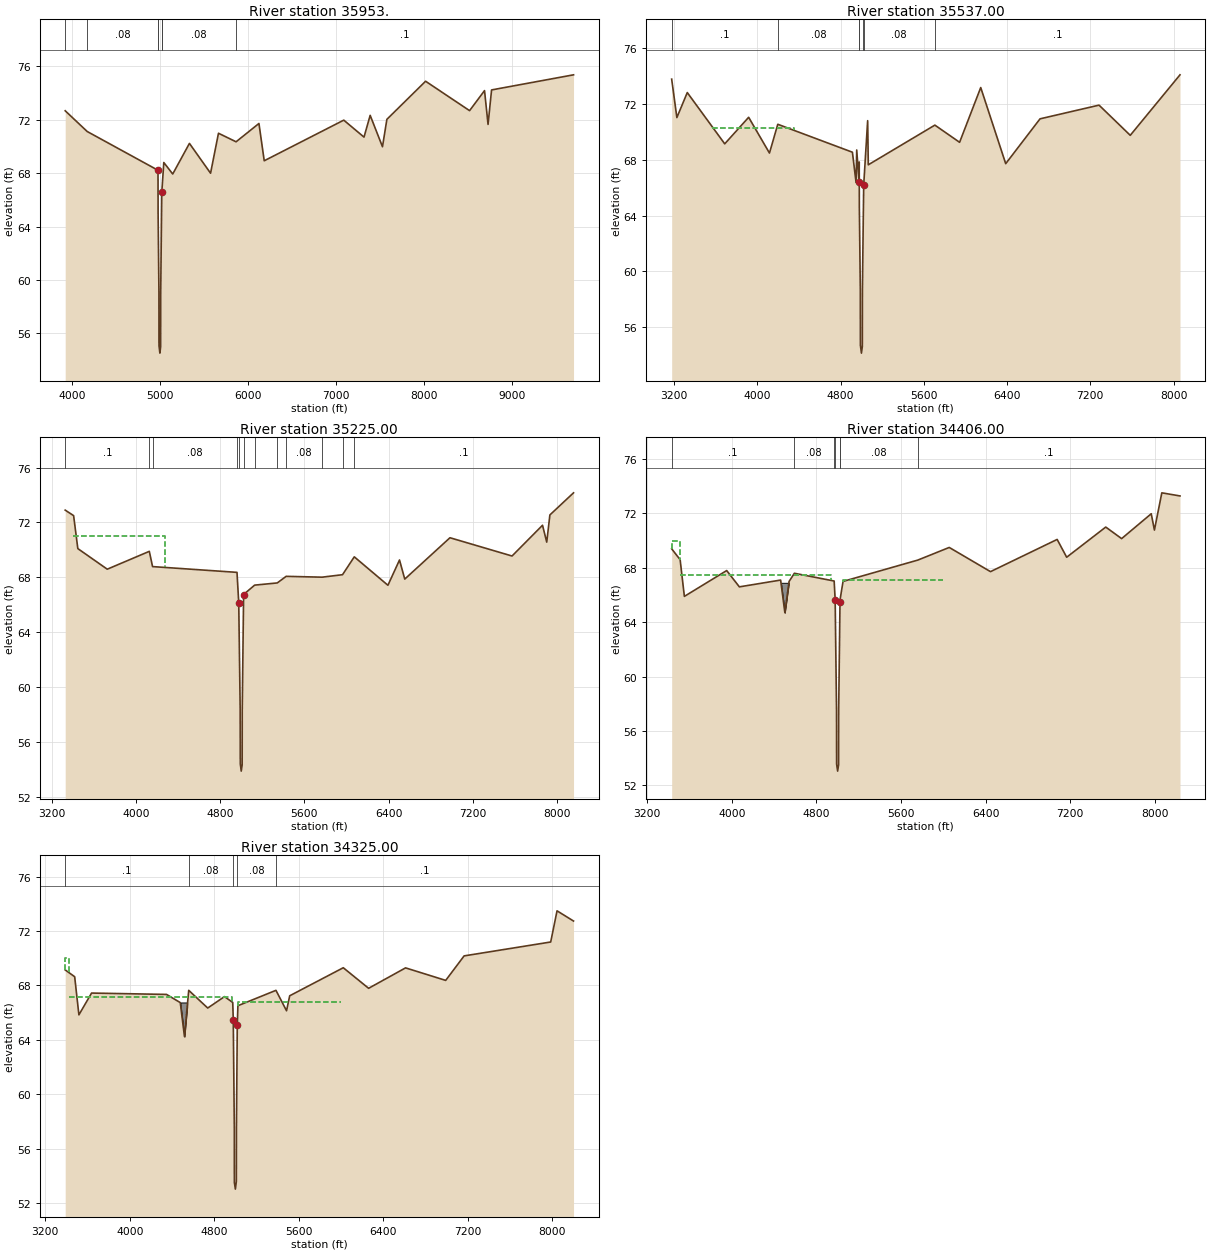
Type RM Length L Ch R = 1 ,35953.  ,418.2,416,415.6
BEGIN DESCRIPTION:
struct 27 d/s of Yale rd-XS1
END DESCRIPTION:
XS GIS Cut Line= 5
      3108635.58     13875181.36      3108693.75     13874202.35
      3108627.74     13874033.31      3107713.56     13872618.82
      3104812.52      13872196.7
#Sta/Elev= 30
  3924.2   72.66  4174.2   71.11    4979   68.21  4980.2   65.01  4989.6   59.08
  4990.3    55.1  5000.4   54.53    5009   55.01  5009.7   59.01  5019.1   64.84
  5022.2   66.57  5044.9   68.79  5146.4   67.93  5336.4   70.22  5576.4   67.99
  5666.4   70.98  5866.4   70.34  6126.4   71.71  6186.4   68.92  7090.6   71.96
  7320.6   70.69  7390.6   72.32  7530.6   69.97  7580.6   72.02  8020.6   74.87
  8520.6   72.67  8690.6   74.17  8730.6   71.64  8770.6   74.22  9702.2   75.35
#Mann= 7 ,-1 , 0
  3924.2     .05       0  4174.2     .08       0    4979     .04       0
  4980.2    .015       0  5019.1     .04       0  5022.2     .08       0
  5866.4      .1       0
Bank Sta=4979,5022.2
XS Rating Curve= 0
Exp/Cntr=.3,.1

Type RM Length L Ch R = 1 ,35537.00,317.4,312,300.2
BEGIN DESCRIPTION:
Cross Section Xsec 29a
END DESCRIPTION:
XS GIS Cut Line= 5
      3109775.98       13875664.      3108772.58      13873333.6
      3108493.22     13873002.52      3107738.01     13872576.19
      3106700.49     13872427.62
#Sta/Elev= 30
  3176.3   73.76  3226.3   71.01  3326.3    72.8  3686.3   69.13  3916.3   71.03
  4116.3   68.47  4196.3   70.53  4913.7   68.53  4948.6   66.37    4955   68.69
  4977.1   66.43    4979   67.83  4980.2   64.63  4989.6    58.7  4990.3   54.72
  5000.4   54.15    5009   54.63  5009.7   58.63  5019.1   64.46  5022.2   66.19
  5060.1   70.79  5066.3   67.63  5706.3   70.47  5943.9   69.24    6147   73.16
  6387.1   67.71  6717.1   70.92  7284.3    71.9  7584.3   69.74  8062.4   74.07
#Mann= 7 ,-1 , 0
  3176.3      .1       0  4196.3     .08       0  4977.1     .04       0
  4980.2    .015       0  5019.1     .04       0  5022.2     .08       0
  5706.3      .1       0
#XS Ineff= 1 ,-1
 3562.65    4350   70.24
Permanent Ineff=
       F
Bank Sta=4977.1,5022.2
XS Rating Curve= 0
Exp/Cntr=.3,.1

Type RM Length L Ch R = 1 ,35225.00,864.9,819,711
BEGIN DESCRIPTION:
Cross Section x29
END DESCRIPTION:
XS GIS Cut Line= 6
       3110142.5       13875232.       3109336.4     13873843.19
      3109265.65     13873756.54      3108732.72     13872872.92
      3107758.39     13872537.46      3106714.76     13872383.89
#Sta/Elev= 30
  3324.9    72.9  3404.9    72.5  3444.9    70.1  3724.9    68.6  4124.9    69.9
  4155.7   68.79  4958.9   68.37  4975.5   66.15  4989.1   58.46  4990.2   54.44
  4999.1    53.9    5008   54.35  5008.8   58.36  5021.7   66.72    5025   66.78
  5126.6   67.44  5342.1    67.6  5426.4   68.08  5768.9   68.02  5962.6    68.2
  6074.5    69.5  6394.5   67.43  6504.5   69.27  6554.5   67.88  6984.5   70.89
  7574.9   69.56  7864.9    71.8  7904.9   70.57  7934.9   72.55  8159.8   74.16
#Mann= 12 ,-1 , 0
  3324.9      .1       0  4124.9     .07       0  4155.7     .08       0
  4958.9     .04       0  4975.5    .015       0    5025     .08       0
  5126.6     .08       0  5342.1     .12       0  5426.4     .08       0
  5768.9     .05       0  5962.6      .1       0  6074.5      .1       0
#XS Ineff= 1 ,-1
 3394.41    4274      71
Permanent Ineff=
       F
Bank Sta=4975.5,5021.7
XS Rating Curve= 0
Exp/Cntr=.3,.1

Type RM Length L Ch R = 1 ,34406.00,83.4,81,79.3
BEGIN DESCRIPTION:
Cross Section Xsec 28b
END DESCRIPTION:
XS GIS Cut Line= 5
       3111345.5       13873385.      3109494.59      13873259.7
      3108838.13      13872859.9      3107769.55     13872494.42
       3106727.4     13872352.31
#Sta/Elev= 30
  3432.2    69.4  3512.2    68.6  3552.2    65.9  3952.2    67.8  4072.2    66.6
  4462.2    67.1  4502.2    64.7  4542.2      67  4592.2    67.6  4968.1   67.03
  4977.6   65.65  4990.6   57.54  4991.3   53.56    5001   53.04  5009.8    53.5
  5010.8   57.51  5023.4   65.47  5024.2   65.67  5052.2      67  5758.7   68.57
  6056.1    69.5    6446   67.72    7076   70.09    7166   68.78  7535.4      71
  7685.4   70.15  7965.4   71.98  7995.4   70.78  8065.4   73.52  8237.2   73.29
#Mann= 7 ,-1 , 0
  3432.2      .1       0  4592.2     .08       0  4968.1     .04       0
  4977.6    .015       0  5023.4     .04       0  5024.2     .08       0
  5758.7      .1       0
#XS Ineff= 3 ,-1
  3432.2  3512.2      70  3512.2    4939    67.5    5051    6000   67.12
Permanent Ineff=
       F       F       F
#Block Obstruct= 1 ,-1
 4455.02 4577.29    66.9
Bank Sta=4977.6,5023.4
XS Rating Curve= 0
Exp/Cntr=.5,.3

Type RM Length L Ch R = 1 ,34325.00,58.9,59,59.5
BEGIN DESCRIPTION:
E HAMILTON u/s
Upstream Section of Bridge/Culvert/Weir
END DESCRIPTION:
XS GIS Cut Line= 5
      3111395.44       13873273.      3109521.21     13873185.23
      3108851.33      13872832.6      3107791.66     13872456.52
      3106746.35     13872304.94
#Sta/Elev= 30
  3388.4   69.14  3478.1   68.64  3518.1   65.84  3638.1   67.44  4348.1   67.34
  4478.1   66.74  4518.1   64.24  4558.1   67.64  4738.1   66.34  4896.9   67.18
  4975.1   66.75    4980   65.48  4989.9   57.58  4990.4   53.53    5000   53.04
  5009.2   53.61    5010   57.59    5018   65.07    5024   66.51  5384.4   67.64
  5484.4   66.14  5514.4   67.24  6021.8    69.3  6261.8   67.79  6611.8   69.29
  6991.8   68.37  7166.2   70.17  7986.2   71.19  8046.2   73.48  8202.4   72.73
#Mann= 5 ,-1 , 0
  3388.4      .1       0  4558.1     .08       0    4980    .015       0
    5018     .08       0  5384.4      .1       0
#XS Ineff= 3 ,-1
  3388.4  3424.6      70  3426.6    4970   67.14    5028    6000    66.8
Permanent Ineff=
       F       F       F
#Block Obstruct= 1 ,-1
  4478.1  4543.5   66.75
Bank Sta=4980,5018
XS Rating Curve= 0
Exp/Cntr=.5,.3