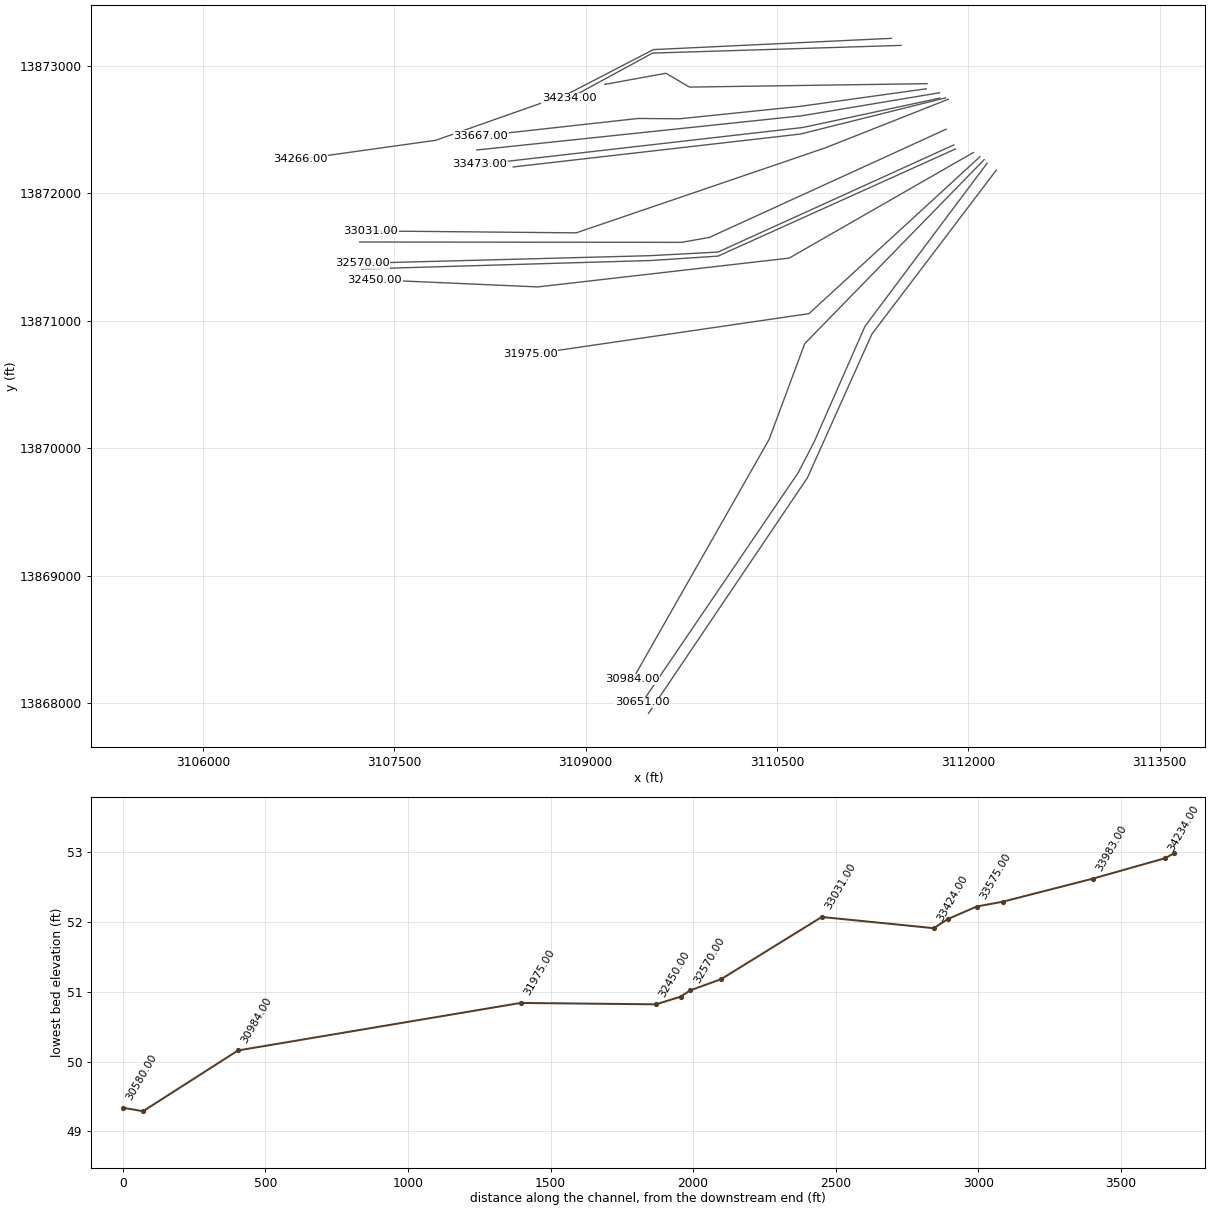
HEC-RAS study E101_00_00.prj: E101-00-00

--- E101_00_00.g01 (geometry) --- (continued)

Type RM Length L Ch R = 3 ,34297.50,,,
BEGIN DESCRIPTION:
E HAMILTON
Structure ID: E101-00-00-26
Deck extended 7' to account for the pipeline downstream.-KHH
END DESCRIPTION:
Bridge Culvert--1,0,-1,-1, 0
Deck Dist Width WeirC Skew NumUp NumDn MinLoCord MaxHiCord MaxSubmerge Is_Ogee
10,35,2.6,0, 93, 93, , , .95, 0, ,,,
  3364.6  3388.1  3424.6  3444.6  3464.6  3478.1  3638.1  3694.6  3698.1  3808.1
  4048.1  4068.1  4083.2  4088.1  4118.1  4314.6  4334.6  4348.1  4368.1  4458.1
  4478.1  4494.6  4558.1  4598.1  4628.1  4658.1  4738.1  4758.1  4778.1  4791.8
  4853.6  4884.6  4887.8  4888.2  4896.9  4909.7  4930.3  4941.1 4960.41  4960.5
  4968.6  4973.4  4975.1    4979 4979.09  4979.2 4979.31    4980  4989.9  4990.4
  4993.5    5000  5000.2  5006.4  5009.2    5010  5010.1 5017.29  5017.4 5017.51
 5017.59  5017.7  5017.8    5018  5023.5    5024  5043.9  5060.6  5067.9  5078.9
  5105.3  5128.9  5218.1  5224.6  5228.1  5254.6  5264.4  5271.5  5281.5  5321.5
  5361.5  5384.4  5474.4  5484.4  5514.4  5594.4  5624.4  5754.4  5756.9  5761.5
  5781.5  6009.7  6034.5
   69.04   69.14   68.94   68.83   68.71   68.64   67.44    67.4    67.4   67.54
   67.54    67.4    67.4   67.54    67.4    67.4   67.33   67.34   67.14   67.25
   67.28    67.3   67.64   67.44   67.06   67.04   66.78   66.84   66.67   66.64
   67.24   66.77   67.12   67.12   67.18   67.04   66.96   66.96   66.95   66.95
   66.94   66.94   66.94   66.94   66.95   70.35   70.35   70.35   70.34   70.34
   70.34   70.33   70.33   70.32   70.32   70.32   70.32   70.31   70.31   66.91
   66.91    66.9    66.9    66.9   66.84   66.84   66.64   66.48    66.5   66.52
   66.58   66.58   66.94   67.07   67.14   67.07   67.04   67.08   67.13   67.33
   67.53   67.64   67.04   67.07   67.24   67.44   67.49   67.88   67.89    67.9
   67.71   69.18   69.34
                                                                                
                                                                                
                                                                                
                                                                                
                                           65.75   65.75   65.75   65.74   65.74
   65.74   65.73   65.73   65.72   65.72   65.72   65.72   65.71   65.71
                                                                                
                                                                                
                                                                                
                        
  3364.6  3388.1  3424.6  3444.6  3464.6  3478.1  3638.1  3694.6  3698.1  3808.1
  4048.1  4068.1  4083.2  4088.1  4118.1  4314.6  4334.6  4348.1  4368.1  4458.1
  4478.1  4494.6  4558.1  4598.1  4628.1  4658.1  4738.1  4758.1  4778.1  4791.8
  4853.6  4884.6  4887.8  4888.2  4896.9  4909.7  4930.3  4941.1 4960.41  4960.5
  4968.6  4973.4  4975.1    4979 4979.09  4979.2 4979.31    4980  4989.9  4990.4
  4993.5    5000  5000.2  5006.4  5009.2    5010  5010.1 5017.29  5017.4 5017.51
 5017.59  5017.7  5017.8    5018  5023.5    5024  5043.9  5060.6  5067.9  5078.9
  5105.3  5128.9  5218.1  5224.6  5228.1  5254.6  5264.4  5271.5  5281.5  5321.5
  5361.5  5384.4  5474.4  5484.4  5514.4  5594.4  5624.4  5754.4  5756.9  5761.5
  5781.5  6009.7  6034.5
   69.04   69.14   68.94   68.83   68.71   68.64   67.44    67.4    67.4   67.54
   67.54    67.4    67.4   67.54    67.4    67.4   67.33   67.34   67.14   67.25
   67.28    67.3   67.64   67.44   67.06   67.04   66.78   66.84   66.67   66.64
   67.24   66.77   67.12   67.12   67.18   67.04   66.96   66.96   66.95   66.95
   66.94   66.94   66.94   66.94   66.95   70.35   70.35   70.35   70.34   70.34
   70.34   70.33   70.33   70.32   70.32   70.32   70.32   70.31   70.31   66.91
   66.91    66.9    66.9    66.9   66.84   66.84   66.64   66.48    66.5   66.52
   66.58   66.58   66.94   67.07   67.14   67.07   67.04   67.08   67.13   67.33
   67.53   67.64   67.04   67.07   67.24   67.44   67.49   67.88   67.89    67.9
   67.71   69.18   69.34
                                                                                
                                                                                
                                                                                
                                                                                
                                           65.75   65.75   65.75   65.74   65.74
   65.74   65.73   65.73   65.72   65.72   65.72   65.72   65.71   65.71
                                                                                
                                                                                
                                                                                
                        
Pier Skew, UpSta & Num, DnSta & Num=  ,4992.2, 2 ,4992.2, 2 , 0 , 0 , 0 ,,
       1       1
   52.37   66.74
       1       1
   52.33    66.7
Pier Skew, UpSta & Num, DnSta & Num=  ,5006.4, 2 ,5006.4, 2 , 0 , 0 , 0 ,,
       1       1
   52.31   66.72
       1       1
   52.27   66.68
BR Coef= 1 , 1 , 1 ,.9, 0 ,,,.8,-1,1.2,0,
WSPro=,,,, 1 ,,,, 0 ,,,, 0 ,,,,-1 ,-1 ,-1 , 0 , 0 , 0 , 0 , 0
BC Design=,, 0 ,, 0 ,,,,,,
BC HTab HWMax=69.34

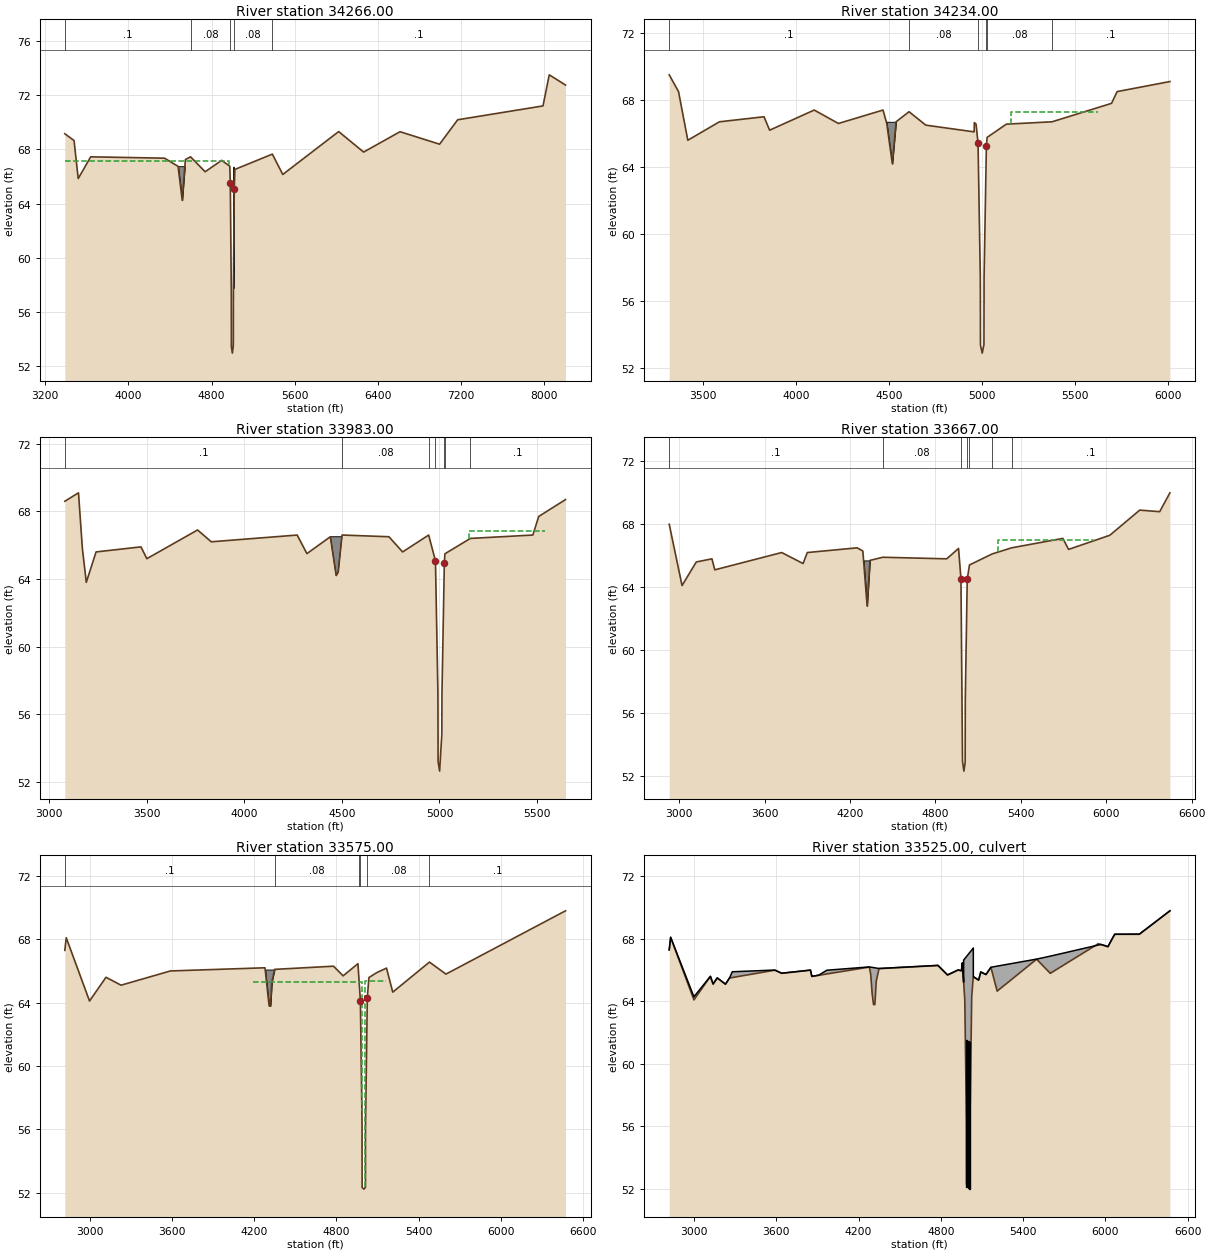
Type RM Length L Ch R = 1 ,34266.00,32.7,32,29.1
BEGIN DESCRIPTION:
E HAMILTON
Downstream Section of Bridge/Culvert/Weir
END DESCRIPTION:
XS GIS Cut Line= 5
        3111398.      13873215.1      3109530.18     13873126.69
      3108865.88     13872782.49      3107823.24      13872415.4
      3106762.13       13872267.
#Sta/Elev= 30
  3389.3   69.14  3478.1   68.64  3518.1   65.84  3638.1   67.44  4348.1   67.34
  4478.1   66.74  4518.1   64.24  4548.1   67.24  4598.1   67.44  4738.1   66.34
  4896.9   67.18  4975.1   66.75    4980   65.48  4989.9   57.52  4990.4   53.47
    5000   52.98  5009.2   53.55    5010   57.53    5018   65.07    5024   66.51
  5384.4   67.64  5484.4   66.14  6021.8    69.3  6261.8   67.79  6611.8   69.29
  6991.8   68.37  7166.2   70.17  7986.2   71.19  8046.2   73.48  8202.4   72.73
#Mann= 5 ,-1 , 0
  3389.3      .1       0  4598.1     .08       0    4980    .015       0
    5018     .08       0  5384.4      .1       0
#XS Ineff= 2 , 0
       0    4970   67.14    5028       0   66.44
Permanent Ineff=
       F       F
#Block Obstruct= 2 ,-1
  4478.1  4543.5   66.75 5010.25 5011.75   66.72
Bank Sta=4980,5018
XS Rating Curve= 0
Exp/Cntr=.5,.3

Type RM Length L Ch R = 1 ,34234.00,281.7,251,174.8
BEGIN DESCRIPTION:
Cross Section Xsec 28a
END DESCRIPTION:
XS GIS Cut Line= 4
      3111472.46     13873159.58      3109936.55      13873112.2
      3109524.25     13873099.48      3108870.81     13872744.06
#Sta/Elev= 30
  3317.4    69.5  3367.4    68.5  3417.4    65.6  3587.4    66.7  3827.4      67
  3857.4    66.2  4097.4    67.4  4227.4    66.6  4467.4    67.4  4487.4    66.6
  4517.4    64.2  4537.4    66.7  4607.4    67.3  4697.4    66.5  4957.4    66.1
  4958.5   66.65  4967.8   66.56  4978.5   65.42  4990.7   57.42  4991.5   53.38
    5001   52.91  5010.2   53.42  5010.9   57.43  5023.3   65.26  5027.2   65.77
  5130.8   66.56  5376.5    66.7  5696.5    67.8  5726.5    68.5  6010.4    69.1
#Mann= 6 ,-1 , 0
  3317.4      .1       0  4607.4     .08       0  4978.5    .015       0
  5023.3     .04       0  5027.2     .08       0  5376.5      .1       0
#XS Ineff= 1 ,-1
 5156.82 5622.93    67.3
Permanent Ineff=
       F
#Block Obstruct= 1 ,-1
 4470.31 4565.07    66.7
Bank Sta=4978.5,5023.3
XS Rating Curve= 0
Exp/Cntr=.3,.1

Type RM Length L Ch R = 1 ,33983.00,294.4,316,366.2
BEGIN DESCRIPTION:
Cross Section x28
END DESCRIPTION:
XS GIS Cut Line= 4
      3111676.56     13872859.67      3109813.27     13872832.75
       3109629.3     13872941.25      3109149.99     13872853.96
#Sta/Elev= 30
  3081.2    68.6  3151.2    69.1  3171.2    65.8  3191.2    63.8  3241.2    65.6
  3471.2    65.9  3501.2    65.2  3761.2    66.9  3831.2    66.2  4271.2    66.6
  4321.2    65.5  4441.2    66.5  4471.2    64.2  4481.2    64.4  4501.2    66.6
  4741.2    66.5  4811.2    65.6  4944.7    66.6  4979.5   65.07  4992.1   57.25
    4993   53.19  5000.8   52.62    5012    54.8  5012.7   57.16    5025   64.95
  5027.9   65.49  5158.3    66.4  5478.3    66.6  5508.3    67.7  5645.5    68.7
#Mann= 7 ,-1 , 0
  3081.2      .1       0  4501.2     .08       0  4944.7     .04       0
  4979.5    .015       0    5025     .04       0  5027.9     .08       0
  5158.3      .1       0
#XS Ineff= 1 ,-1
 5153.66 5539.01   66.82
Permanent Ineff=
       F
#Block Obstruct= 1 ,-1
 4441.05 4524.89    66.5
Bank Sta=4979.5,5025
XS Rating Curve= 0
Exp/Cntr=.3,.1

Type RM Length L Ch R = 1 ,33667.00,130.4,92,108
BEGIN DESCRIPTION:
Cross Section Xsec 27b
END DESCRIPTION:
XS GIS Cut Line= 5
 3111670.5315659 13872819.331433      3110674.65     13872680.74
      3109736.13     13872584.23      3109410.11     13872586.61
      3108175.81     13872450.03
#Sta/Elev= 30
  2930.4      68  3020.4    64.1  3120.4    65.6  3230.4    65.8  3250.4    65.1
  3720.4    66.2  3870.4    65.5  3900.4    66.2  4250.4    66.5  4290.4    66.3
  4320.4    62.8  4340.4    65.7  4430.4    65.9  4879.4    65.8  4962.6   66.46
  4979.5   64.53  4990.5   52.91  5000.3   52.29  5009.1   52.85    5010   56.85
  5023.6    64.5  5039.4   65.41  5198.6   66.11  5335.4    66.5  5695.4    67.1
  5735.4    66.4  6025.4    67.3  6235.4    68.9  6375.4    68.8  6447.2      70
#Mann= 7 ,-1 , 0
  2930.4      .1       0  4430.4     .08       0  4979.5    .015       0
  5023.6     .04       0  5039.4     .08       0  5198.6     .05       0
  5335.4      .1       0
#XS Ineff= 1 ,-1
 5239.16 5907.41   66.99
Permanent Ineff=
       F
#Block Obstruct= 1 ,-1
 4281.66 4375.98    65.7
Bank Sta=4979.5,5023.6
XS Rating Curve= 0
Exp/Cntr=.5,.3

Type RM Length L Ch R = 1 ,33575.00,170.1,102,113
BEGIN DESCRIPTION:
TIDWELL u/s
Upstream Section of Bridge/Culvert/Weir
END DESCRIPTION:
XS GIS Cut Line= 3
      3111774.42     13872788.33       3110693.2     13872607.52
      3108146.11     13872339.54
#Sta/Elev= 30
  2818.9   67.31  2829.2   68.11  2999.2   64.11  3119.2   65.61  3229.2   65.11
  3589.2   66.01  4279.2   66.21  4309.2   63.81  4319.2   63.81  4329.2   65.31
  4349.2   66.11  4779.2   66.31  4849.2    65.7  4957.3   66.47  4965.4    65.4
  4975.1   64.12  4987.3    56.3  4987.7   52.32  5000.8   52.22  5012.1   52.33
  5012.3   52.51  5012.5   56.16  5025.6   64.31  5037.1   65.59  5091.7   65.89
  5165.8   66.19  5211.2   64.67  5478.9   66.57  5599.2   65.81  6471.4   69.81
#Mann= 6 ,-1 , 0
  2818.9      .1       0  4349.2     .08       0  4965.4     .04       0
  4975.1    .015       0  5025.6     .08       0  5478.9      .1       0
#XS Ineff= 3 ,-1
 5163.51 5856.97   66.13    5012 5163.51    65.4 4192.67    4986    65.3
Permanent Ineff=
       F       F       F
#Block Obstruct= 1 ,-1
    4279    4349    66.1
Bank Sta=4975.1,5025.6
XS Rating Curve= 0
Exp/Cntr=.5,.3

Type RM Length L Ch R = 2 ,33525.00,,,
BEGIN DESCRIPTION:
TIDWELL
Structure ID: E101-00-00-25
Chain link fence rail hieght reduced by 0.5 to
model the likeliness that the fence would fall if
the force of the water was above the halff way
point up the fence.
END DESCRIPTION:
Bridge Culvert--1,0,-1,-1, 0
Deck Dist Width WeirC Skew NumUp NumDn MinLoCord MaxHiCord MaxSubmerge Is_Ogee
10,80,2.6,0, 70, 70, , , .95, 0, ,,,
  2818.9  2829.2  2998.9  2999.2  3119.2  3139.2  3168.9  3169.2  3229.2  3258.9
  3259.2  3278.9  3589.2  3639.2  3828.9  3849.2  3858.9  3859.2  3888.9  3898.9
  3908.9  3968.9  4279.2  4349.2  4778.9  4779.2  4849.2    4871  4909.7  4926.6
  4939.6    4940  4950.5  4957.3  4958.9  4965.4 4966.59  4966.7 4966.81  4975.1
  4987.3  4987.7  5000.8  5012.1  5012.3  5012.5  5025.6  5037.1 5037.19  5037.3
 5037.41    5076  5078.1  5091.7  5124.2  5129.7  5165.8  5499.2  5598.9  5599.2
  5968.9  6008.9  6019.2  6058.9  6068.9  6069.2  6249.2  6258.9  6306.9  6471.4
    67.3   68.11    64.3    64.3   65.61   65.13   65.51   65.51   65.11   65.51
   65.51    65.9   66.01   65.81   65.99   66.01   65.62   65.61   65.65   65.67
   65.68      66   66.21   66.11   66.31   66.31    65.7   65.79   65.95   66.02
   65.99   65.99   65.97   66.47   66.26    65.4   65.24   66.65   66.65   66.74
   66.87   66.88   67.02   67.15   67.15   67.15   67.29   67.42   67.42   67.42
   65.59   65.37   65.44   65.89   65.75   65.73   66.19   66.71    66.9    66.9
   67.65   67.54   67.51   68.15    68.3    68.3   68.31   68.38    68.7    69.8
                                                                                
                                                                                
                                                                                
                                                                                
                                                                                
                                                                                
                                                                                
  2818.9  2829.2  2998.9  2999.2  3119.2  3139.2  3168.9  3169.2  3229.2  3258.9
  3259.2  3278.9  3589.2  3639.2  3828.9  3849.2  3858.9  3859.2  3888.9  3898.9
  3908.9  3968.9  4279.2  4349.2  4778.9  4779.2  4849.2    4871  4909.7  4926.6
  4939.6    4940  4950.5  4957.3  4958.9  4965.4 4966.59  4966.7 4966.81  4975.1
  4987.3  4987.7  5000.8  5012.1  5012.3  5012.5  5025.6  5037.1 5037.19  5037.3
 5037.41    5076  5078.1  5091.7  5124.2  5129.7  5165.8  5499.2  5598.9  5599.2
  5968.9  6008.9  6019.2  6058.9  6068.9  6069.2  6249.2  6258.9  6306.9  6471.4
    67.3   68.11    64.3    64.3   65.61   65.13   65.51   65.51   65.11   65.51
   65.51    65.9   66.01   65.81   65.99   66.01   65.62   65.61   65.65   65.67
   65.68      66   66.21   66.11   66.31   66.31    65.7   65.79   65.95   66.02
   65.99   65.99   65.97   66.47   66.26    65.4   65.24   66.65   66.65   66.74
   66.87   66.88   67.02   67.15   67.15   67.15   67.29   67.42   67.42   67.42
   65.59   65.37   65.44   65.89   65.75   65.73   66.19   66.71    66.9    66.9
   67.65   67.54   67.51   68.15    68.3    68.3   68.31   68.38    68.7    69.8
                                                                                
                                                                                
                                                                                
                                                                                
                                                                                
                                                                                
                                                                                
BR Coef= 1 , 1 , 1 ,1.25, 0 ,,,.8,0,2,0,
WSPro=,,,, 1 ,,,, 0 ,,,, 0 ,,,,-1 ,-1 ,-1 , 0 , 0 , 0 , 0 , 0
Culvert=2,9.4,8,80,.015,.5,1,8,2,52.13,4990.7,52.05,4990.7,Culvert #1  , 0 ,10
Culvert Bottom n=.015
Culvert=2,9.4,8,80,.015,.5,1,8,2,52.04,4999.5,52.09,4999.5,Culvert #2  , 0 ,10
Culvert Bottom n=.015
Culvert=2,9.4,8,80,.015,.5,1,8,2,51.99,5008.4,52.04,5008.4,Culvert #3  , 0 ,10
Culvert Bottom n=.015
BR U #Sta/Elev= 90
  2818.9    67.3  2829.2    68.1  2998.9   64.11  2999.2    64.1  3119.2    65.6
  3139.2    65.1  3168.9    65.5  3169.2    65.5  3229.2    65.1  3258.9    65.5
  3259.2    65.5  3278.9   65.53  3589.2      66  3639.2    65.8  3828.9   65.98
  3849.2      66  3858.9   65.61  3859.2    65.6  3888.9   65.64  3898.9   65.66
  3908.9   65.67  3968.9   65.76  4279.2    66.2  4288.9   65.72  4289.2    65.7
  4298.9   64.54  4299.2    64.5  4308.9   63.82  4309.2    63.8  4318.9    63.8
  4319.2    63.8  4328.9   65.26  4329.2    65.3  4338.9   65.69  4349.2    66.1
  4778.9    66.3  4779.2    66.3  4849.2   65.69    4871   65.78  4909.7   65.94
  4926.6   66.01  4939.6   65.98    4940   65.98  4950.5   65.96  4957.3   66.46
  4958.9   66.25  4965.4   65.39 4966.59   65.23  4966.7   65.22 4966.81    65.2
  4975.1   64.11  4987.3   56.29  4987.7   52.31  5000.8   52.21  5012.1   52.32
  5012.3    52.5  5012.5   56.15  5025.6    64.3  5037.1   65.58 5037.19   65.58
  5037.3   65.58 5037.41   65.58    5076   65.36  5078.1   65.43  5091.7   65.88
  5124.2   65.74  5129.7   65.72  5165.8   66.18  5171.4   65.99  5211.2   64.66
  5478.9   66.56  5499.2    66.7  5598.9    65.8  5599.2    65.8  5628.9   65.96
  5648.9   66.07  5938.9   67.64  5949.2    67.7  5968.9   67.64  5998.9   67.56
  6008.9   67.53  6019.2    67.5  6058.9   68.14  6068.9    68.3  6069.2    68.3
  6218.9    68.3  6249.2    68.3  6258.9   68.37  6306.9   68.69  6471.4    69.8
BR U #Mann= 6
  2818.9      .1  4279.2     .08  4965.4     .04  4975.1    .015  5025.6     .08
  5499.2      .1
BR U Banks=4975.1,5025.6
BR D #Sta/Elev= 85
  2818.9    67.3  2829.2    68.1  2998.9   64.11  2999.2    64.1  3119.2    65.6
  3139.2    65.1  3168.9    65.5  3169.2    65.5  3229.2    65.1  3258.9    65.5
  3259.2    65.5  3278.9   65.53  3589.2      66  3639.2    65.8  3828.9   65.98
  3849.2      66  3858.9   65.61  3859.2    65.6  3888.9   65.64  3898.9   65.66
  3908.9   65.67  3968.9   65.76  4279.2    66.2  4288.9   65.72  4289.2    65.7
  4298.9   64.54  4299.2    64.5  4308.9   63.82  4309.2    63.8  4318.9    63.8
  4319.2    63.8  4328.9   65.26  4329.2    65.3  4338.9   65.69  4349.2    66.1
  4778.9    66.3  4779.2    66.3  4849.2   65.69    4871   65.78  4909.7   65.94
  4926.6   66.01  4939.6   65.98    4940   65.98  4950.5   65.96  4957.3   66.46
  4958.9   66.25  4965.4   65.39 4966.59   65.23  4966.7   65.22 4966.81    65.2
  4975.1   64.11  4987.3   56.14  4987.7   52.16  5000.8   52.06  5012.1   52.17
  5012.3   52.35  5012.5      56  5025.6    64.3  5037.1   65.58 5037.19   65.58
  5037.3   65.58 5037.41   65.58    5076   65.36  5078.1   65.43  5091.7   65.88
  5124.2   65.74  5129.7   65.72  5165.8   66.18  5171.4   65.99  5478.9   66.56
  5499.2    66.7  5938.9   67.64  5949.2    67.7  5968.9   67.64  5998.9   67.56
  6008.9   67.53  6019.2    67.5  6058.9   68.14  6068.9    68.3  6069.2    68.3
  6218.9    68.3  6249.2    68.3  6258.9   68.37  6306.9   68.69  6471.4    69.8
BR D #Mann= 6
  2818.9      .1  4279.2     .08  4965.4     .04  4975.1    .015  5025.6     .08
  5499.2      .1
BR D Banks=4975.1,5025.6
BC Design=,, 0 ,, 0 ,,,,,,
BC HTab HWMax=69.81

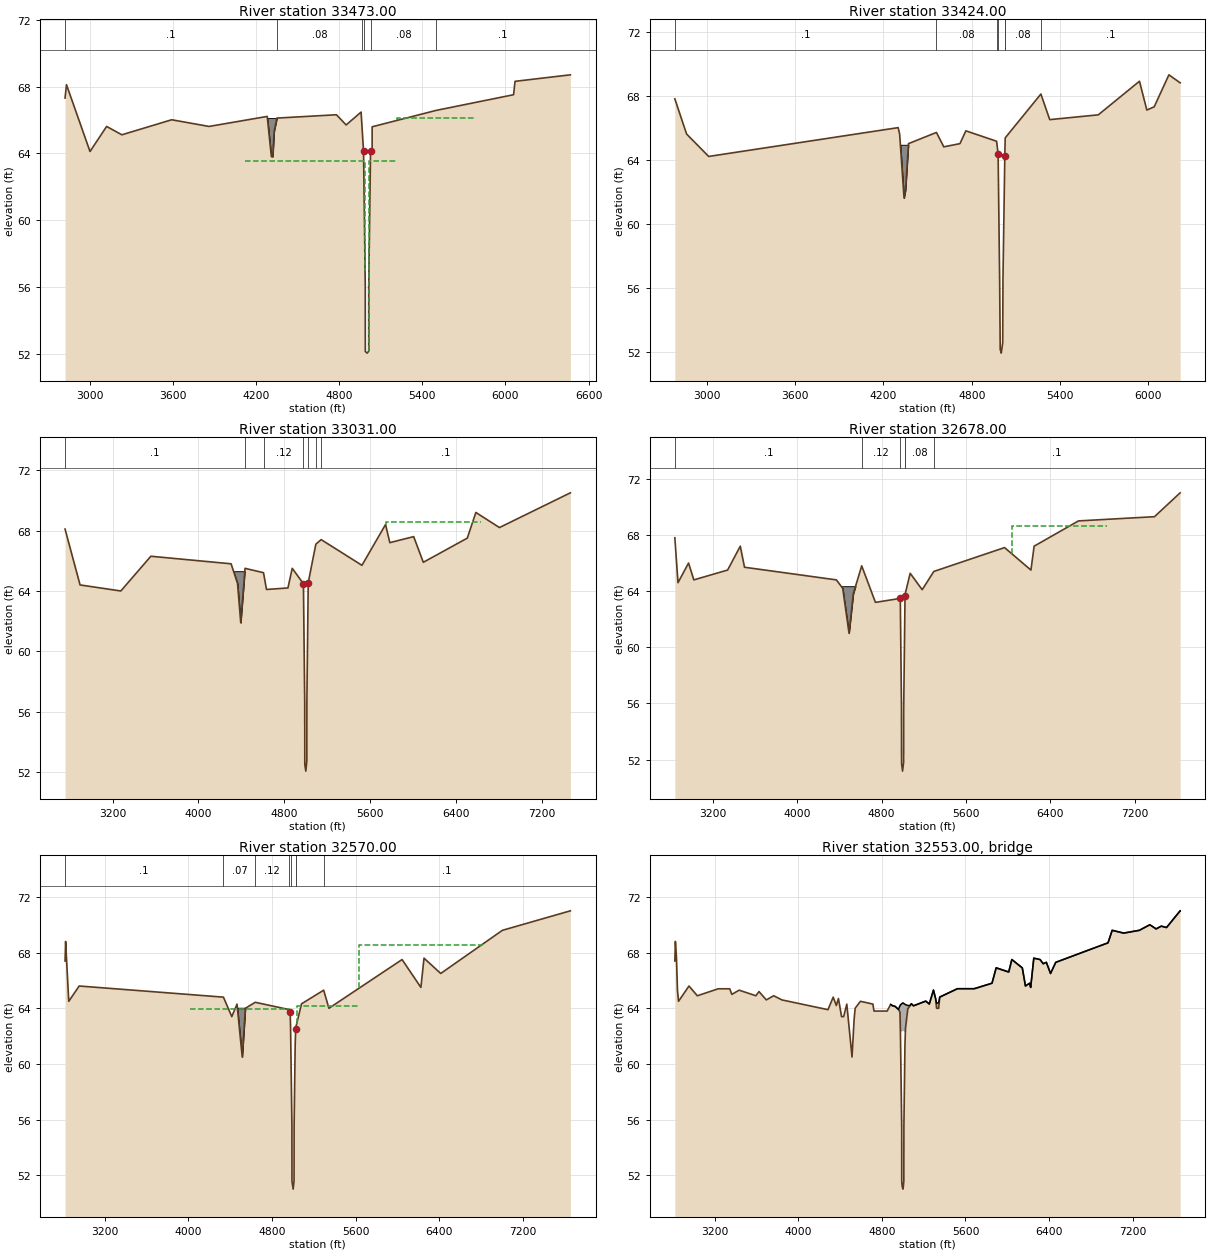
Type RM Length L Ch R = 1 ,33473.00,73.5,49,53.9
BEGIN DESCRIPTION:
TIDWELL
Downstream Section of Bridge/Culvert/Weir
END DESCRIPTION:
XS GIS Cut Line= 3
  3111778.48056713872746.6171416       3110703.4     13872516.05
      3108169.36     13872226.13
#Sta/Elev= 30
  2818.9   67.31  2829.2   68.11  2999.2   64.11  3119.2   65.61  3229.2   65.11
  3589.2   66.01  3859.2   65.61  4279.2   66.21  4309.2   63.81  4319.2   63.81
  4329.2   65.31  4349.2   66.11  4779.2   66.31  4849.2    65.7  4957.3   66.47
  4965.4    65.4  4975.1   64.12  4987.3   56.12  4987.7   52.14  5000.8   52.04
  5012.1   52.15  5012.3   52.33  5012.5   55.98  5025.6   64.13  5037.1   64.31
 5037.19   65.59  5499.2   66.57  6058.9   67.51  6069.2   68.31    6469    68.7
#Mann= 6 ,-1 , 0
  2818.9      .1       0  4349.2     .08       0  4965.4     .04       0
  4975.1    .015       0  5025.6     .08       0  5499.2      .1       0
#XS Ineff= 3 ,-1
  5217.1 5784.48   66.13    5012  5217.1   63.52 4120.17    4986   63.52
Permanent Ineff=
       F       F       F
#Block Obstruct= 1 ,-1
    4279    4349   66.11
Bank Sta=4975.1,5025.6
XS Rating Curve= 0
Exp/Cntr=.5,.3

Type RM Length L Ch R = 1 ,33424.00,231.4,393,403.4
BEGIN DESCRIPTION:
Cross Section Xsec 27a
END DESCRIPTION:
XS GIS Cut Line= 3
      3111821.27     13872748.17       3110682.9      13872464.4
      3108431.24     13872206.48
#Sta/Elev= 30
  2782.1    67.8  2862.1    65.6  3012.1    64.2    4300      66    4310    65.6
    4340    61.6    4350    62.1    4370      65    4560    65.7    4610    64.8
    4720      65    4760    65.8  4968.8   65.15  4979.3   64.35  4989.6   56.49
  4993.5   52.14  5000.5   51.91  5010.5   52.56  5012.2   56.53  5024.8   64.25
  5026.3   64.89  5027.4   65.36    5270    68.1    5330    66.5    5660    66.8
    5940    68.9    5990    67.1    6040    67.3    6140    69.3  6216.4    68.8
#Mann= 7 ,-1 , 0
  2782.1      .1       0    4560     .08       0  4968.8     .04       0
  4979.3    .015       0  5024.8     .04       0  5026.3     .08       0
    5270      .1       0
#XS Ineff= 1 ,-1
 5220.25 6143.81    67.5
Permanent Ineff=
       F
#Block Obstruct= 1 ,-1
 4292.14 4396.94   64.93
Bank Sta=4979.3,5024.8
XS Rating Curve= 0
Exp/Cntr=.3,.1

Type RM Length L Ch R = 1 ,33031.00,302.8,353,347.4
BEGIN DESCRIPTION:
Cross Section x27
END DESCRIPTION:
XS GIS Cut Line= 4
      3111842.78      13872737.2      3110877.25     13872355.55
      3108925.54     13871689.67      3107314.53     13871704.63
#Sta/Elev= 30
    2756    68.1    2896    64.4    3276      64    3556    66.3  4304.2    65.8
  4364.2    64.5  4394.2    61.9  4434.2    65.5  4606.5   65.21  4634.2    64.1
  4834.2    64.2  4874.2    65.5  4978.7   64.48  4990.6   56.64  4991.4   52.51
  5000.9   52.07  5010.3   52.74  5010.8   56.69  5023.2   64.54  5094.2    67.1
  5144.2    67.4  5524.2    65.7  5744.2    68.4  5784.2    67.2  6006.4    67.6
  6096.4    65.9  6506.4    67.5  6586.4    69.2  6806.4    68.2  7467.5    70.5
#Mann= 7 ,-1 , 0
    2756      .1       0  4434.2     .08       0  4606.5     .12       0
  4978.7    .015       0  5023.2     .04       0  5094.2     .08       0
  5144.2      .1       0
#XS Ineff= 1 ,-1
 5744.68  6638.3   68.57
Permanent Ineff=
       F
#Block Obstruct= 1 ,-1
 4305.68 4468.12   65.31
Bank Sta=4978.7,5023.2
XS Rating Curve= 0
Exp/Cntr=.3,.1

Type RM Length L Ch R = 1 ,32678.00,153.1,108,107.5
BEGIN DESCRIPTION:
Cross Section Xsec 26b
END DESCRIPTION:
XS GIS Cut Line= 4
      3111825.83     13872502.19      3109969.33     13871653.79
      3109750.88     13871615.12      3107227.72     13871617.83
#Sta/Elev= 30
    2842    67.8    2872    64.6    2972      66    3022    64.8    3342    65.5
    3462    67.2    3502    65.7    4372    64.8    4432    64.2    4492      61
    4532    63.8    4612    65.8    4742    63.2  4977.5   63.48  4988.8   55.68
  4989.5   51.72    4999   51.18  5009.1   51.82  5009.8    55.7  5022.3   63.62
    5026   63.87  5071.1   65.27    5185    64.1    5295    65.4    5965    67.1
    6215    65.5    6245    67.2    6665      69    7385    69.3  7628.2      71
#Mann= 6 ,-1 , 0
    2842      .1       0    4612     .12       0  4977.5    .015       0
  5022.3     .04       0    5026     .08       0    5295      .1       0
#XS Ineff= 1 ,-1
 6037.83 6936.17   68.66
Permanent Ineff=
       F
#Block Obstruct= 1 ,-1
  4373.8 4599.13   64.35
Bank Sta=4977.5,5022.3
XS Rating Curve= 0
Exp/Cntr=.5,.3

Type RM Length L Ch R = 1 ,32570.00,33.9,34,39.4
BEGIN DESCRIPTION:
LEAGO DRIVE u/s
Upstream Section of Bridge/Culvert/Weir
END DESCRIPTION:
XS GIS Cut Line= 4
      3111885.69     13872378.66      3110037.41     13871539.01
        3109504.     13871510.61      3107245.34     13871451.21
#Sta/Elev= 30
  2819.5   67.41  2824.8   68.81  2854.8   64.51  2954.8   65.61  4334.8   64.81
  4414.8   63.41  4464.8   64.31  4514.8   60.51  4544.8   64.01  4639.5   64.44
  4960.1   63.92  4973.6   63.72  4977.2   62.62  4990.1   55.57  4990.5    51.6
  5001.8   51.02  5010.5   51.61  5011.1    55.5  5021.1   61.36  5026.3   62.54
  5028.3   62.67    5082   64.33    5294   65.31    5344   64.01    6044   67.51
    6224   65.51    6254   67.61    6414   66.51    7004   69.61  7654.2   71.01
#Mann= 8 ,-1 , 0
  2819.5      .1       0  4334.8     .07       0  4639.5     .12       0
  4960.1     .04       0  4977.2    .015       0  5026.3     .04       0
  5028.3     .08       0    5294      .1       0
#XS Ineff= 3 ,-1
 5631.21 6817.97   68.56    5034 5631.21   64.16 4014.18    4966   63.97
Permanent Ineff=
       F       F       F
#Block Obstruct= 1 ,-1
 4461.83 4545.81   64.05
Bank Sta=4973.6,5026.3
XS Rating Curve= 0
Exp/Cntr=.5,.3

Type RM Length L Ch R = 3 ,32553.00,,,
BEGIN DESCRIPTION:
LEAGO DRIVE
Structure ID: E101-00-00-24
END DESCRIPTION:
Bridge Culvert--1,0,-1,-1, 0
Deck Dist Width WeirC Skew NumUp NumDn MinLoCord MaxHiCord MaxSubmerge Is_Ogee
10,14,30,0, 72, 72, , , .95, 0, ,,,
  4884.5  4903.5  4923.6  4926.8  4958.4  4960.1  4961.3  4973.6  4977.2  4977.5
 4977.91 4977.95  4990.1  4990.5  4994.4  5001.6  5001.8  5005.5  5010.5  5011.1
  5021.1  5024.3 5024.79 5024.82  5026.3  5028.3  5048.2  5070.6    5082  5103.1
  5119.1  5172.8  5186.1    5220    5254    5294    5314    5324    5344    5354
  5506.1    5524    5684    5854    5894    6014  6043.4    6044    6144    6174
  6194.5    6214    6224    6254    6314    6344    6374    6414    6464    6784
    6964    7004    7114    7136    7264    7364    7424    7474  7516.7    7524
    7654  7654.2
   64.28   64.18   64.15   64.14   63.92   63.95   63.97   64.18   64.24   64.25
   64.25   64.25   64.32   64.33   64.35   64.39   64.39   64.37   64.34   64.34
   64.29   64.27   64.27   64.27   64.26   64.26    64.2    64.2   64.33   64.18
   64.23   64.38   64.42   64.52   64.31   65.31   64.71   64.36    64.4   64.81
   65.35   65.41   65.41    65.8   66.91   66.61   67.49    67.5    66.9    65.6
    65.7    65.8    65.5    67.6    67.5    67.2    67.3    66.5    67.3    68.2
    68.7    69.6    69.4   69.43    69.6      70    69.7    69.9   69.81    69.8
      71      71
                                                                                
           62.25   62.32   62.33   62.35   62.39   62.39   62.37   62.34   62.34
   62.29   62.27   62.27
                                                                                
                                                                                
                                                                                
                                                                                
                
  4884.5  4903.5  4923.6  4926.8  4958.4  4960.1  4961.3  4973.6  4977.2  4977.5
 4977.91 4977.95  4990.1  4990.5  4994.4  5001.6  5001.8  5005.5  5010.5  5011.1
  5021.1  5024.3 5024.79 5024.82  5026.3  5028.3  5048.2  5070.6    5082  5103.1
  5119.1  5172.8  5186.1    5220    5254    5294    5314    5324    5344    5354
  5506.1    5524    5684    5854    5894    6014  6043.4    6044    6144    6174
  6194.5    6214    6224    6254    6314    6344    6374    6414    6464    6784
    6964    7004    7114    7136    7264    7364    7424    7474  7516.7    7524
    7654  7654.2
   64.28   64.18   64.15   64.14   63.92   63.95   63.97   64.18   64.24   64.25
   64.25   64.25   64.32   64.33   64.35   64.39   64.39   64.37   64.34   64.34
   64.29   64.27   64.27   64.27   64.26   64.26    64.2    64.2   64.33   64.18
   64.23   64.38   64.42   64.52   64.31   65.31   64.71   64.36    64.4   64.81
   65.35   65.41   65.41    65.8   66.91   66.61   67.49    67.5    66.9    65.6
    65.7    65.8    65.5    67.6    67.5    67.2    67.3    66.5    67.3    68.2
    68.7    69.6    69.4   69.43    69.6      70    69.7    69.9   69.81    69.8
      71      71
                                                                                
           62.25   62.32   62.33   62.35   62.39   62.39   62.37   62.34   62.34
   62.29   62.27   62.27
                                                                                
                                                                                
                                                                                
                                                                                
                
BR Coef= 1 , 1 , 0 ,1.25, 0 ,,,.8,-1,2,0,
WSPro=,,,, 1 ,,,, 0 ,,,, 0 ,,,,-1 ,-1 ,-1 , 0 , 0 , 0 , 0 , 0
BR U #Sta/Elev= 128
  2819.5    67.4  2824.8    68.8  2829.5   68.28  2834.8    67.7  2839.5   66.57
  2844.8    65.3  2854.8    64.5  2954.8    65.6  3034.8    64.9  3234.8    65.4
  3329.5    65.4  3344.8    65.4  3349.5   65.31  3359.5   65.11  3364.8      65
  3434.8    65.3  3470.2   65.21  3539.5   65.04  3569.5   64.96  3594.8    64.9
  3624.8    65.2  3694.8    64.6  3764.8    64.9  3844.8    64.6  4069.5   64.24
  4129.5   64.15  4209.5   64.02  4239.5   63.97  4259.5   63.94  4284.8    63.9
  4299.5   64.16  4329.5    64.7  4334.8    64.8  4364.8    64.2  4384.8    64.7
  4409.5   63.63  4414.8    63.4  4434.8    63.4  4464.8    64.3  4489.5   62.42
  4499.5   61.66  4511.5   60.75  4514.8    60.5  4519.5   61.13  4529.5   62.48
  4534.8    63.2  4539.5   63.58  4544.8      64  4549.5   64.05  4559.5   64.15
  4594.8    64.5  4639.5   64.43  4714.8    64.3  4724.8    63.8  4850.6    63.8
  4876.1   64.15  4884.5   64.27  4903.5   64.17  4923.6   64.14  4926.8   64.13
  4958.4   63.92  4960.1   63.91  4961.3    63.9  4973.6   63.71  4977.2   62.61
  4977.5   62.45 4977.91   62.22    4978   62.17  4990.1   55.56  4990.5   51.59
  4994.4   51.22  5001.6   51.02  5001.8   51.01  5005.5    51.2  5010.5    51.6
  5011.1   55.49  5021.1   61.35  5024.3   62.08 5024.79   62.19  5024.9   62.21
  5026.3   62.53  5028.3   62.66  5048.2   63.94  5070.6   64.19    5082   64.32
  5103.1   64.17  5119.1   64.22  5172.8   64.37  5186.1   64.41    5220   64.51
    5254    64.3    5294    65.3    5314    64.7    5324      64    5344      64
    5354    64.8  5506.1   65.34    5524    65.4    5684    65.4    5854    65.8
    5894    66.9    6014    66.6  6043.4   67.48    6044    67.5    6144    66.9
    6174    65.6  6194.5    65.7    6214    65.8    6224    65.5    6254    67.6
    6314    67.5    6344    67.2    6374    67.3    6414    66.5    6464    67.3
    6784    68.2    6964    68.7    7004    69.6    7114    69.4    7136   69.43
    7264    69.6    7364      70    7424    69.7    7474    69.9  7516.7   69.81
    7524    69.8    7654      71  7654.2      71
BR U #Mann= 7
  2819.5      .1  4639.5     .12  4960.1     .04  4977.2    .015  5026.3     .04
  5028.3     .08  5119.1      .1
BR D #Sta/Elev= 128
  2819.5   67.33  2824.8   68.73  2829.5   68.21  2834.8   67.63  2839.5    66.5
  2844.8   65.23  2854.8   64.43  2954.8   65.53  3034.8   64.83  3234.8   65.33
  3329.5   65.33  3344.8   65.33  3349.5   65.24  3359.5   65.04  3364.8   64.93
  3434.8   65.23  3470.2   65.14  3539.5   64.97  3569.5   64.89  3594.8   64.83
  3624.8   65.13  3694.8   64.53  3764.8   64.83  3844.8   64.53  4069.5   64.17
  4129.5   64.08  4209.5   63.95  4239.5    63.9  4259.5   63.87  4284.8   63.83
  4299.5   64.09  4329.5   64.63  4334.8   64.73  4364.8   64.13  4384.8   64.63
  4409.5   63.56  4414.8   63.33  4434.8   63.33  4464.8   64.23  4489.5   62.35
  4499.5   61.59  4511.5   60.68  4514.8   60.43  4519.5   61.06  4529.5   62.41
  4534.8   63.13  4539.5   63.51  4544.8   63.93  4549.5   63.98  4559.5   64.08
  4594.8   64.43  4639.5   64.36  4714.8   64.23  4724.8   63.73  4850.6   63.73
  4876.1   64.08  4884.5    64.2  4903.5    64.1  4923.6   64.07  4926.8   64.06
  4958.4   63.85  4960.1   63.84  4961.3   63.83  4973.6   63.64  4977.2   62.54
  4977.5   62.38 4977.91   62.15    4978    62.1  4990.1   55.49  4990.5   51.52
  4994.4   51.15  5001.6   50.95  5001.8   50.94  5005.5   51.13  5010.5   51.53
  5011.1   55.42  5021.1   61.28  5024.3   62.01 5024.79   62.12  5024.9   62.14
  5026.3   62.46  5028.3   62.59  5048.2   63.87  5070.6   64.12    5082   64.25
  5103.1    64.1  5119.1   64.15  5172.8    64.3  5186.1   64.34    5220   64.44
    5254   64.23    5294   65.23    5314   64.63    5324   63.93    5344   63.93
    5354   64.73  5506.1   65.27    5524   65.33    5684   65.33    5854   65.73
    5894   66.83    6014   66.53  6043.4   67.41    6044   67.43    6144   66.83
    6174   65.53  6194.5   65.63    6214   65.73    6224   65.43    6254   67.53
    6314   67.43    6344   67.13    6374   67.23    6414   66.43    6464   67.23
    6784   68.13    6964   68.63    7004   69.53    7114   69.33    7136   69.36
    7264   69.53    7364   69.93    7424   69.63    7474   69.83  7516.7   69.74
    7524   69.73    7654   70.93  7654.2   70.93
BR D #Mann= 7
  2819.5      .1  4639.5     .12  4960.1     .04  4977.2    .015  5026.3     .04
  5028.3     .08  5119.1      .1
BR D Banks=,5026.3
BC Design=,, 0 ,, 0 ,,,,,,
BC HTab HWMax=71.01

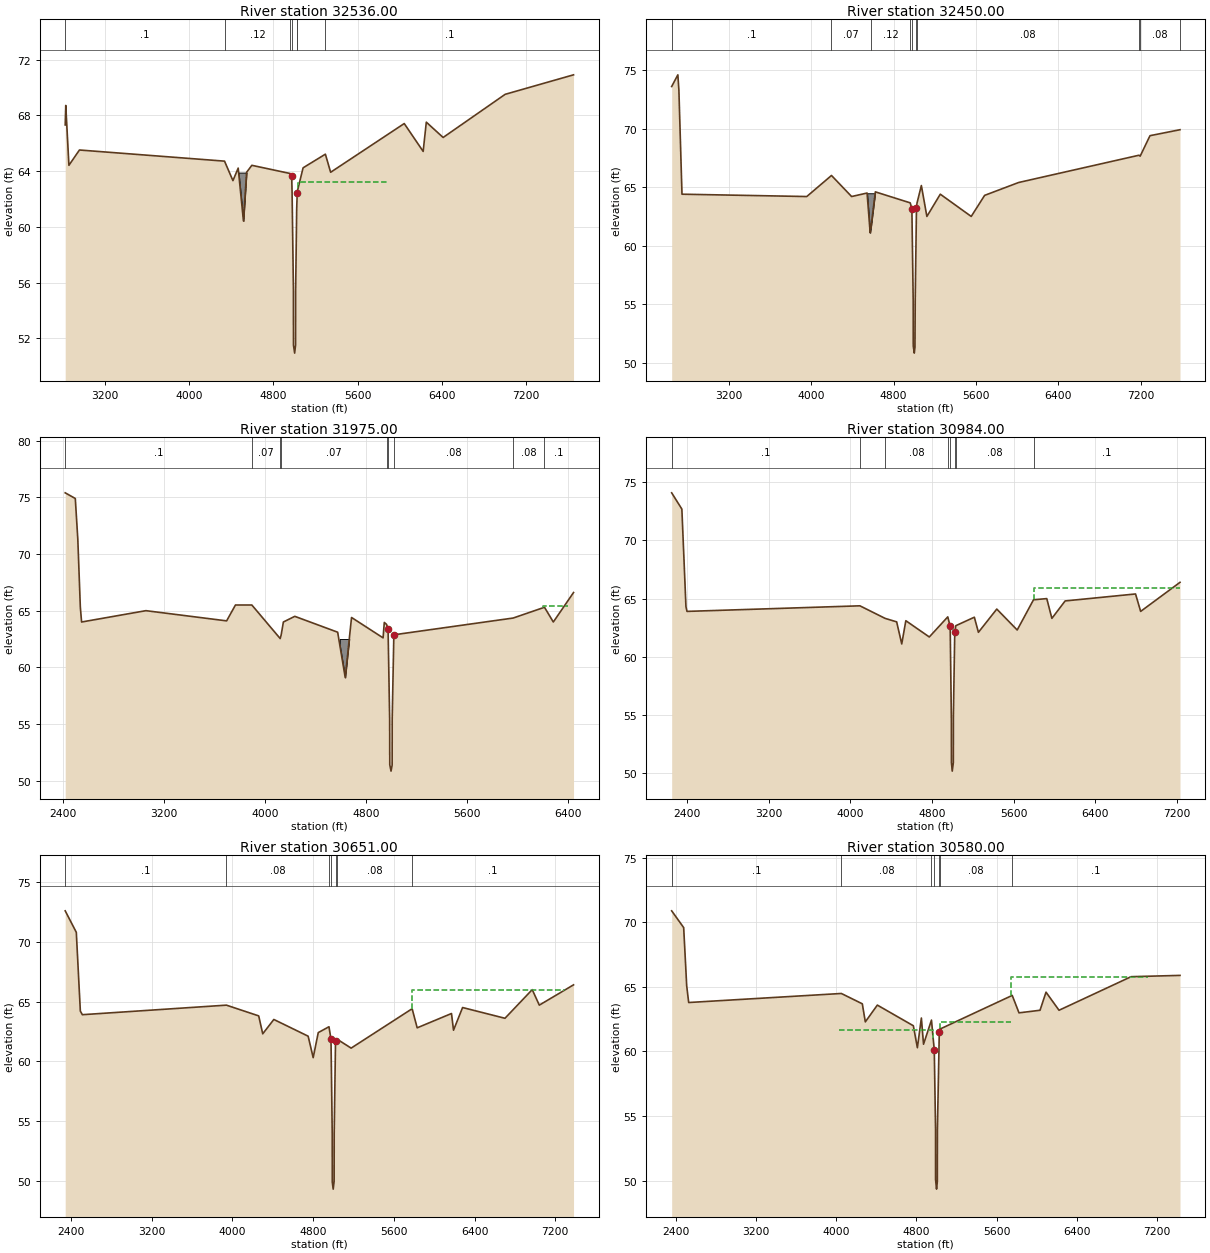
Type RM Length L Ch R = 1 ,32536.00,277.2,86,107.1
BEGIN DESCRIPTION:
LEAGO DRIVE
Downstream Section of Bridge/Culvert/Weir
END DESCRIPTION:
XS GIS Cut Line= 4
      3111898.37     13872346.97      3110037.41     13871507.18
      3109510.89     13871472.75      3107242.35     13871406.24
#Sta/Elev= 30
  2819.5   67.32  2824.8   68.72  2854.8   64.42  2954.8   65.52  4334.8   64.72
  4414.8   63.32  4464.8   64.22  4514.8   60.42  4544.8   63.92  4594.8   64.42
  4960.1   63.83  4973.6   63.63  4977.2   62.53  4990.1   55.48  4990.5   51.51
  5001.8   50.93  5010.5   51.52  5011.1   55.41  5021.1   61.27  5026.3   62.45
  5028.3   62.58    5082   64.24    5294   65.22    5344   63.92    6044   67.42
    6224   65.42    6254   67.52    6414   66.42    7004   69.52  7654.2   70.92
#Mann= 7 ,-1 , 0
  2819.5      .1       0  4334.8     .12       0  4960.1     .04       0
  4977.2    .015       0  5026.3     .04       0  5028.3     .08       0
    5294      .1       0
#XS Ineff= 3 ,-1
 5891.25 6647.75   66.36    5034 5891.25    63.2 4113.48    4966    63.2
Permanent Ineff=
       F       F       F
#Block Obstruct= 1 ,-1
 4465.86 4548.41    63.9
Bank Sta=4973.6,5026.3
XS Rating Curve= 0
Exp/Cntr=.5,.3

Type RM Length L Ch R = 1 ,32450.00,465.6,475,517
BEGIN DESCRIPTION:
Cross Section Xsec 26a
END DESCRIPTION:
XS GIS Cut Line= 4
      3112040.09     13872319.76      3110595.52     13871491.57
      3108624.64      13871265.7 3107344.957889613871321.8226252
#Sta/Elev= 30
  2648.7    73.6  2708.7    74.6  2718.7    73.3  2748.7    64.4  3958.7    64.2
  4198.7      66  4393.8    64.2  4543.8    64.5  4573.8    61.1  4581.9   61.59
  4623.8    64.6  4962.3   63.66  4978.3   63.14  4991.1    55.3  4991.7   51.42
  5001.5   50.82  5008.3   51.33  5010.6   55.34  5022.7   63.18    5028   63.64
  5070.2   65.14  5123.8    62.5  5253.8    64.4  5553.8    62.5  5683.8    64.3
  6013.8    65.4  7180.9   67.73  7192.1   67.65  7287.6    69.4  7578.5   69.91
#Mann= 10 ,-1 , 0
  2648.7      .1       0  4198.7     .07       0  4581.9     .12       0
  4962.3     .04       0  4978.3    .015       0  5022.7     .04       0
    5028     .08       0  7180.9     .12       0  7192.1     .08       0
  7578.5     .08       0
#Block Obstruct= 1 ,-1
 4543.49 4629.87   64.48
Bank Sta=4978.3,5022.7
XS Rating Curve= 0
Exp/Cntr=.3,.1

Type RM Length L Ch R = 1 ,31975.00,332.4,991,1352.3
BEGIN DESCRIPTION:
Cross Section x26
END DESCRIPTION:
XS GIS Cut Line= 3
      3112091.77     13872286.71      3110750.35     13871055.96
       3108563.3     13870736.14
#Sta/Elev= 30
  2416.3    75.4  2496.3    74.9  2516.3    71.3  2536.3    65.3  2546.3      64
  3056.3      65  3696.3    64.1  3766.3    65.5  3896.3    65.5    4121   62.54
  4128.8   62.86  4146.3      64  4236.8    64.5  4576.8    63.1  4636.8    59.1
  4686.8    64.4  4936.8    62.6  4946.6   63.96  4964.3   63.79  4976.5   63.39
  4989.1   55.38  4989.9   51.41  4999.9   50.84  5008.7   51.37  5009.2   55.44
  5022.3   62.87  5968.4   64.35  6216.8    65.3  6286.8      64  6447.1    66.6
#Mann= 9 ,-1 , 0
  2416.3      .1       0  3896.3     .07       0    4121     .08       0
  4128.8     .07       0  4964.3     .04       0  4976.5    .015       0
  5022.3     .08       0  5968.4     .08       0  6216.8      .1       0
#XS Ineff= 1 ,-1
  6204.1  6401.1   65.44
Permanent Ineff=
       F
#Block Obstruct= 1 ,-1
 4593.82 4696.29    62.5
Bank Sta=4976.5,5022.3
XS Rating Curve= 0
Exp/Cntr=.3,.1

Type RM Length L Ch R = 1 ,30984.00,383.6,333,314.1
BEGIN DESCRIPTION:
Cross Section x25
END DESCRIPTION:
XS GIS Cut Line= 4
      3112124.36     13872263.43      3110717.43      13870820.8
      3110438.11     13870069.54      3109367.57     13868186.92
#Sta/Elev= 30
  2248.4    74.1  2348.4    72.7  2388.4    64.3  2398.4    63.9  4093.4   64.38
  4340.3    63.3  4453.5      63  4503.5    61.1  4543.5    63.1  4773.5    61.7
  4954.6   63.43  4978.1   62.62  4989.7   54.77  4990.6   50.89  4998.4   50.16
  5009.3   50.89  5009.5   54.86    5023    62.1  5033.3   62.67    5215    63.4
    5255    62.1    5435    64.1    5635    62.3    5795    64.9    5925      65
    5975    63.3    6105    64.8    6795    65.4    6845    63.9  7230.7    66.4
#Mann= 8 ,-1 , 0
  2248.4      .1       0  4093.4     .07       0  4340.3     .08       0
  4954.6     .04       0  4978.1    .015       0    5023     .04       0
  5033.3     .08       0    5795      .1       0
#XS Ineff= 1 ,-1
 5796.69  7230.7    65.9
Permanent Ineff=
       F
Bank Sta=4978.1,5023
XS Rating Curve= 0
Exp/Cntr=.3,.1

Type RM Length L Ch R = 1 ,30651.00,70.6,71,84.8
BEGIN DESCRIPTION:
Cross Section Xsec 24b
END DESCRIPTION:
XS GIS Cut Line= 5
      3112147.64     13872235.49      3111190.17     13870957.07
      3110793.21     13870054.54      3110667.74     13869810.66
      3109442.83      13868008.2
#Sta/Elev= 30
  2344.5    72.6  2454.5    70.8  2494.5    64.2  2514.5    63.9  3941.7    64.7
  4261.7    63.8  4301.7    62.3  4411.7    63.5  4751.7    62.1  4801.7    60.3
  4851.7    62.4  4958.1   62.89  4978.1   61.84  4990.3   53.92  4990.9   49.89
    5000   49.29  5009.1   49.93  5009.7   53.91    5023   61.73  5038.3   61.85
  5177.7    61.1    5782    64.4    5832    62.8    6172      64    6192    62.6
    6282    64.5    6702    63.6    6972      66    7042    64.7  7381.2    66.4
#Mann= 7 ,-1 , 0
  2344.5      .1       0  3941.7     .08       0  4958.1     .04       0
  4978.1    .015       0    5023     .04       0  5038.3     .08       0
    5782      .1       0
#XS Ineff= 1 ,-1
 5777.78 7286.05   65.96
Permanent Ineff=
       F
Bank Sta=4978.1,5023
XS Rating Curve= 0
Exp/Cntr=.5,.3

Type RM Length L Ch R = 1 ,30580.00,56.9,58,58.2
BEGIN DESCRIPTION:
WERNER u/s
Upstream Section of Bridge/Culvert/Weir
END DESCRIPTION:
XS GIS Cut Line= 5
       3112220.2     13872181.75      3111244.17     13870895.54
      3110738.52     13869768.68      3110492.34     13869403.78
      3109492.16     13867921.24
#Sta/Elev= 30
  2354.7   70.89  2474.7   69.59  2504.7   65.09  2524.7   63.79  4049.7   64.49
  4259.3   63.69  4289.3   62.29  4409.3   63.59  4769.3   61.99  4809.3   60.29
  4849.3   62.59  4870.8   60.56  4950.2   62.43 4977.69   60.15  4979.4   59.53
  4990.8   54.06  4991.2   50.07  5000.8   49.34  5008.6   49.91  5009.4   53.92
  5025.5   60.38  5028.1   61.53  5034.1   61.73  5756.9   64.34  5824.6   62.99
  6034.6   63.19  6094.6   64.59  6224.6   63.19  6944.6   65.79    7433   65.89
#Mann= 7 ,-1 , 0
  2354.7      .1       0  4049.7     .08       0  4950.2     .04       0
  4979.4    .015       0  5025.5     .04       0  5034.1     .08       0
  5756.9      .1       0
#XS Ineff= 3 ,-1
 5749.41 7115.84   65.75 5036.21 5749.41   62.29 4023.64 4967.79   61.65
Permanent Ineff=
       F       F       F
Bank Sta=4977.69,5028.1
XS Rating Curve= 0
Exp/Cntr=.5,.3