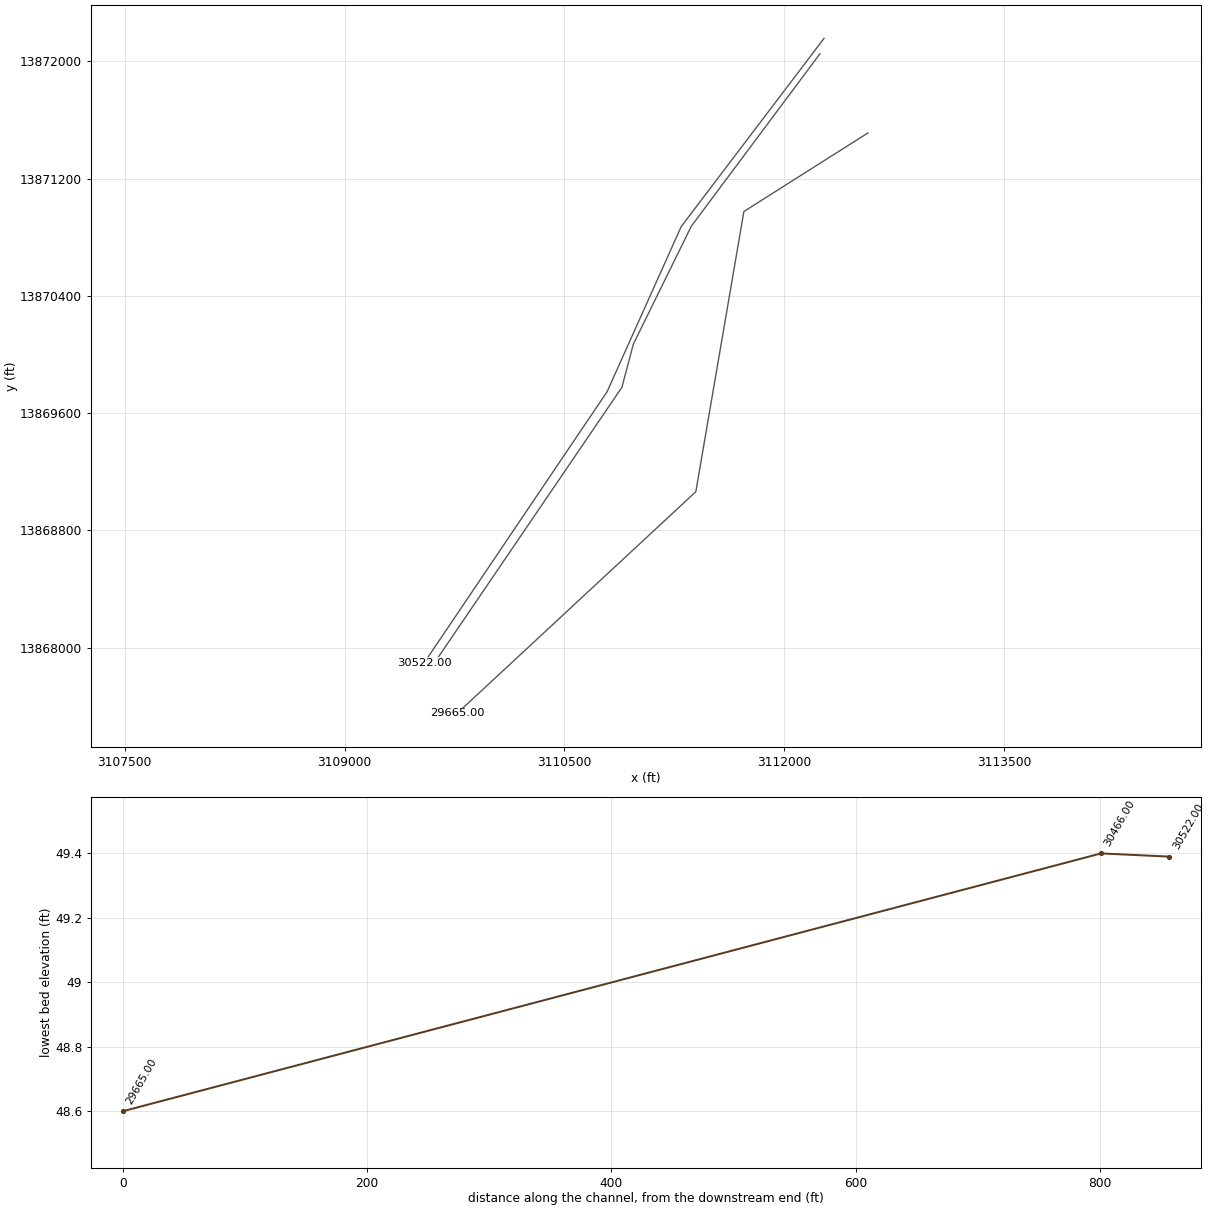
HEC-RAS study E101_00_00.prj: E101-00-00

--- E101_00_00.g01 (geometry) --- (continued)

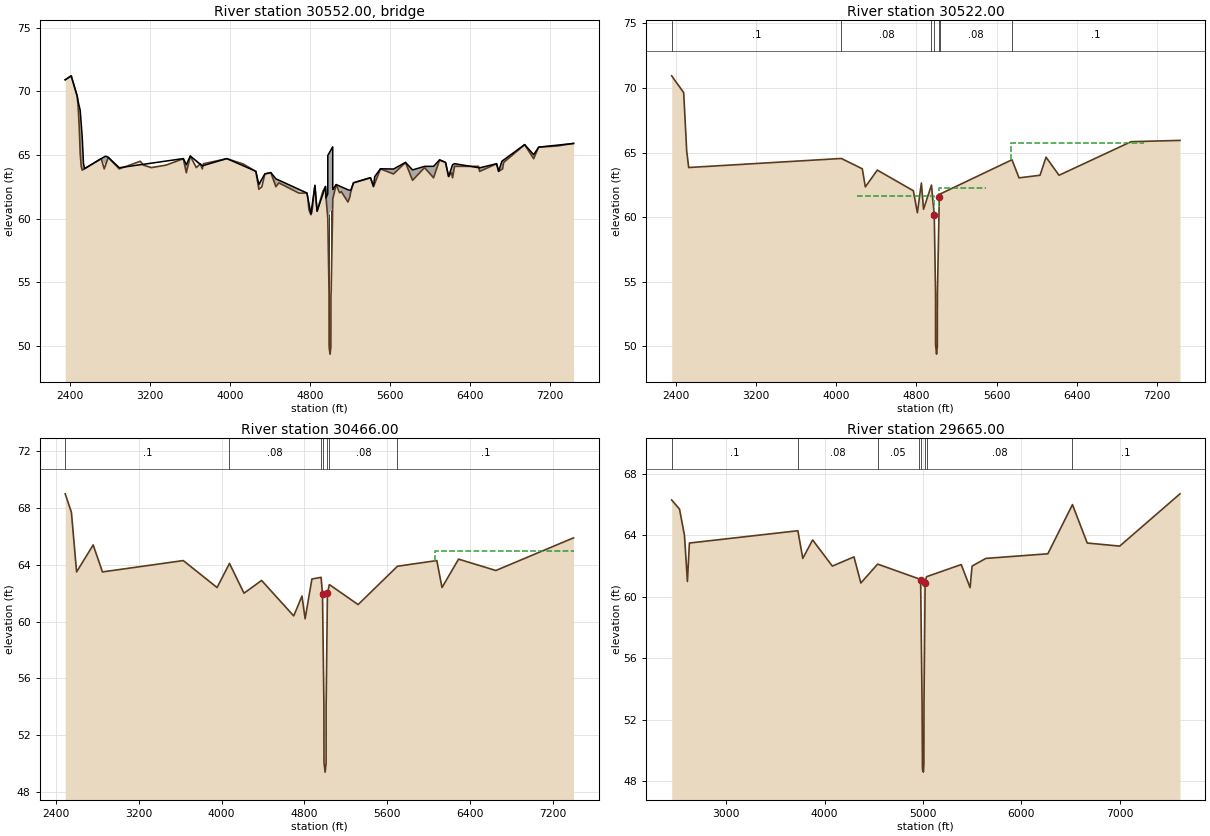
Type RM Length L Ch R = 3 ,30552.00,,,
BEGIN DESCRIPTION:
WERNER
Structure ID: E101-00-00-23
END DESCRIPTION:
Bridge Culvert--1,0,-1,-1, 0
Deck Dist Width WeirC Skew NumUp NumDn MinLoCord MaxHiCord MaxSubmerge Is_Ogee
10,36,2.65,0, 60, 60, , , .95, 0, ,,,
  2354.7  2414.7  2474.7  2484.7  2504.7  2524.7  2537.8  2547.8  2714.7  2757.8
  2784.7  2894.7  3534.7  3564.7  3604.7  3724.7  3969.3  4259.3  4289.3  4349.3
  4409.3  4459.3  4769.3  4809.3  4849.3  4870.8  4954.9  4960.6  4977.8  4977.9
 5026.69  5027.3 5027.41  5027.8  5061.7  5179.3  5206.4  5234.4  5404.4  5434.4
  5446.9  5504.4  5634.4  5754.6  5824.6  5944.6  6034.6  6094.6  6154.6  6184.6
  6224.6  6244.6  6494.6  6664.6  6684.6  6716.9  6944.6  7034.6  7084.6    7433
    70.9   71.21   69.61   69.17    68.5    66.4    64.3   63.92   64.71    64.9
   64.81   63.99   64.71   64.23   64.91   64.14   64.71   63.71   62.68   63.51
   63.61   63.12   62.01   60.36   62.61   60.58   62.52   61.62   61.95   64.95
   65.63   65.44   62.44   62.28   62.67   62.26   62.21   62.81   63.21   62.55
    63.3   63.91   63.89   64.41   63.82    64.1    64.1   64.61   64.41   63.31
   64.23   64.31   63.98   64.31   63.71    64.5   65.81   65.02   65.61    65.9
    70.9    71.2    69.6    68.7    65.1    63.8   63.86   63.91    64.7   64.19
    64.8    63.9    64.7    63.6    64.9    63.9    64.7    63.7    62.3    63.5
    63.6    62.5      62    60.3    62.6   60.57   62.51   61.61   60.15   60.11
   60.92   61.19   61.23   61.41   62.66    61.3   62.05    62.8    63.2    62.5
   62.75    63.9    63.5    64.4      63      64    63.2    64.6    64.4    63.3
    63.2    64.1    63.7    64.3    63.7   63.86    65.8    64.7    65.6    65.9
  2354.7  2414.7  2474.7  2484.7  2504.7  2524.7  2537.8  2547.8  2714.7  2757.8
  2784.7  2894.7  3534.7  3564.7  3604.7  3724.7  3969.3  4259.3  4289.3  4349.3
  4409.3  4459.3  4769.3  4809.3  4849.3  4870.8  4954.9  4960.6  4977.8  4977.9
 5026.69  5027.3 5027.41  5027.8  5061.7  5179.3  5206.4  5234.4  5404.4  5434.4
  5446.9  5504.4  5634.4  5754.6  5824.6  5944.6  6034.6  6094.6  6154.6  6184.6
  6224.6  6244.6  6494.6  6664.6  6684.6  6716.9  6944.6  7034.6  7084.6    7433
    70.9   71.21   69.61   69.17    68.5    66.4    64.3   63.92   64.71    64.9
   64.81   63.99   64.71   64.23   64.91   64.14   64.71   63.71   62.68   63.51
   63.61   63.12   62.01   60.36   62.61   60.58   62.52   61.62   61.95   64.95
   65.63   65.44   62.44   62.28   62.67   62.26   62.21   62.81   63.21   62.55
    63.3   63.91   63.89   64.41   63.82    64.1    64.1   64.61   64.41   63.31
   64.23   64.31   63.98   64.31   63.71    64.5   65.81   65.02   65.61    65.9
    70.9    71.2    69.6    68.7    65.1    63.8   63.86   63.91    64.7   64.19
    64.8    63.9    64.7    63.6    64.9    63.9    64.7    63.7    62.3    63.5
    63.6    62.5      62    60.3    62.6   60.57   62.51   61.61   60.15   60.11
   60.92   61.19   61.23   61.41   62.66    61.3   62.05    62.8    63.2    62.5
   62.75    63.9    63.5    64.4      63      64    63.2    64.6    64.4    63.3
    63.2    64.1    63.7    64.3    63.7   63.86    65.8    64.7    65.6    65.9
Pier Skew, UpSta & Num, DnSta & Num=  ,4993.1, 2 ,4993.1, 2 , 0 , 0 , 0 ,,
       1       1
   48.74   61.38
       1       1
   48.78   61.42
Pier Skew, UpSta & Num, DnSta & Num=  ,5011.5, 2 ,5011.5, 2 , 0 , 0 , 0 ,,
       1       1
   53.17   61.63
       1       1
   53.21   61.67
BR Coef= 1 , 1 , 1 ,1.25, 0 ,,,.8,0,2,0,
WSPro=,,,, 1 ,,,, 0 ,,,, 0 ,,,,-1 ,-1 ,-1 , 0 , 0 , 0 , 0 , 0
BR U #Sta/Elev= 176
  2354.7    70.9  2387.8   71.07  2414.7    71.2    2445   70.39  2474.7    69.6
  2477.8   69.32  2484.7    68.7  2494.7    67.2  2504.7    65.1  2507.8   64.79
  2514.7    64.1  2517.8   64.01  2524.7    63.8  2537.8   63.86  2547.8   63.91
  2687.8   64.57  2714.7    64.7  2717.8   64.62  2744.7    63.9  2757.8   64.19
  2784.7    64.8  2797.8   64.69  2894.7    63.9  3067.8   64.39  3087.8   64.45
  3104.7    64.5  3107.8   64.47  3134.7    64.2  3214.7      64  3364.7    64.2
  3447.8   64.44  3467.8    64.5  3507.8   64.62  3527.8   64.68  3534.7    64.7
  3547.8   64.22  3564.7    63.6    3585   64.26  3597.8   64.68  3604.7    64.9
  3617.8    64.7  3623.1   64.62  3637.8    64.4  3664.7      64  3677.8    64.1
  3704.7    64.3  3717.8   64.04  3724.7    63.9  3734.7    64.3  3797.8   64.41
  3961.7   64.69  3969.3    64.7  4049.7    64.5  4083.7   64.41  4121.7   64.32
  4129.3    64.3  4131.7   64.29  4201.7   63.97  4231.7   63.83  4259.3    63.7
  4289.3    62.3  4319.3    62.5  4349.3    63.5  4361.7   63.52  4409.3    63.6
  4459.3    62.5  4489.3    62.8  4671.7   62.07  4689.3      62  4701.7      62
  4745.7      62  4769.3      62  4779.3    61.6  4789.3    60.7  4806.4   60.36
  4809.3    60.3  4819.3    60.5  4849.3    62.6  4870.8   60.57  4923.8   62.01
  4929.1   62.15  4950.2   62.44  4954.9   62.51  4960.6   61.61 4977.69   60.16
  4977.8   60.15  4977.9   60.11 4978.01   60.07  4978.1   60.04 4978.21   59.99
  4978.3   59.96  4979.4   59.54  4990.8   54.07  4991.1   51.08  4991.2   50.08
  4993.1   49.77  5000.8   49.35  5008.6   49.92  5008.8   50.06  5008.9    50.7
  5009.4   53.93  5011.5   54.25  5025.5   60.39 5026.69   60.92  5026.8   60.96
  5026.9   61.01 5027.19   61.14  5027.3   61.19 5027.41   61.23  5027.8   61.41
  5028.1   61.54  5034.1   61.74  5061.7   62.66  5064.9    62.6  5096.6   62.02
  5112.2   62.12    5157   61.57  5179.3    61.3  5199.3    61.7  5204.4      62
  5206.4   62.05  5234.4    62.8  5336.9   63.04  5356.9   63.09  5376.9   63.14
  5404.4    63.2  5426.9   62.67  5434.4    62.5  5446.9   62.75  5504.4    63.9
  5634.4    63.5  5636.9   63.52  5716.9   64.12  5754.6    64.4  5756.9   64.35
  5766.9   64.15  5796.9   63.55  5824.6      63  5836.9    63.1  5944.6      64
  6034.6    63.2  6066.9   63.95  6094.6    64.6  6106.9   64.56  6154.6    64.4
  6166.9   63.95  6184.6    63.3  6186.9   63.32  6214.6    63.6  6224.6    63.2
  6226.9    63.3  6244.6    64.1  6366.9    64.1  6396.9    64.1  6484.6    64.1
  6494.6    63.7  6616.9   64.13  6664.6    64.3  6676.9   63.93  6684.6    63.7
  6716.9   63.86  6724.6    63.9  6734.6    64.4  6796.9   64.82  6836.9   65.08
  6944.6    65.8  6946.9   65.77  6976.9   65.41  7006.9   65.04  7034.6    64.7
  7046.9   64.92  7084.6    65.6  7136.9   65.63  7274.6    65.7  7396.9   65.85
    7433    65.9
BR U #Mann= 7
  2354.7      .1  4049.7     .08  4950.2     .04  4979.4    .015  5025.5     .04
  5034.1     .08  6034.6      .1
BR U Banks=4979.4,5025.5
BR D #Sta/Elev= 176
  2354.7   70.94  2387.8   71.11  2414.7   71.24    2445   70.43  2474.7   69.64
  2477.8   69.36  2484.7   68.74  2494.7   67.24  2504.7   65.14  2507.8   64.83
  2514.7   64.14  2517.8   64.05  2524.7   63.84  2537.8    63.9  2547.8   63.95
  2687.8   64.61  2714.7   64.74  2717.8   64.66  2744.7   63.94  2757.8   64.23
  2784.7   64.84  2797.8   64.73  2894.7   63.94  3067.8   64.43  3087.8   64.49
  3104.7   64.54  3107.8   64.51  3134.7   64.24  3214.7   64.04  3364.7   64.24
  3447.8   64.48  3467.8   64.54  3507.8   64.66  3527.8   64.72  3534.7   64.74
  3547.8   64.26  3564.7   63.64    3585    64.3  3597.8   64.72  3604.7   64.94
  3617.8   64.74  3623.1   64.66  3637.8   64.44  3664.7   64.04  3677.8   64.14
  3704.7   64.34  3717.8   64.08  3724.7   63.94  3734.7   64.34  3797.8   64.45
  3961.7   64.73  3969.3   64.74  4049.7   64.54  4083.7   64.45  4121.7   64.36
  4129.3   64.34  4131.7   64.33  4201.7   64.01  4231.7   63.87  4259.3   63.74
  4289.3   62.34  4319.3   62.54  4349.3   63.54  4361.7   63.56  4409.3   63.64
  4459.3   62.54  4489.3   62.84  4671.7   62.11  4689.3   62.04  4701.7   62.04
  4745.7   62.04  4769.3   62.04  4779.3   61.64  4789.3   60.74  4806.4    60.4
  4809.3   60.34  4819.3   60.54  4849.3   62.64  4870.8   60.61  4923.8   62.05
  4929.1   62.19  4950.2   62.48  4954.9   62.55  4960.6   61.65 4977.69    60.2
  4977.8   60.19  4977.9   60.15 4978.01   60.11  4978.1   60.08 4978.21   60.03
  4978.3      60  4979.4   59.58  4990.8   54.11  4991.1   51.12  4991.2   50.12
  4993.1   49.81  5000.8   49.39  5008.6   49.96  5008.8    50.1  5008.9   50.74
  5009.4   53.97  5011.5   54.29  5025.5   60.43 5026.69   60.96  5026.8      61
  5026.9   61.05 5027.19   61.18  5027.3   61.23 5027.41   61.27  5027.8   61.45
  5028.1   61.58  5034.1   61.78  5061.7    62.7  5064.9   62.64  5096.6   62.06
  5112.2   62.16    5157   61.61  5179.3   61.34  5199.3   61.74  5204.4   62.04
  5206.4   62.09  5234.4   62.84  5336.9   63.08  5356.9   63.13  5376.9   63.18
  5404.4   63.24  5426.9   62.71  5434.4   62.54  5446.9   62.79  5504.4   63.94
  5634.4   63.54  5636.9   63.56  5716.9   64.16  5754.6   64.44  5756.9   64.39
  5766.9   64.19  5796.9   63.59  5824.6   63.04  5836.9   63.14  5944.6   64.04
  6034.6   63.24  6066.9   63.99  6094.6   64.64  6106.9    64.6  6154.6   64.44
  6166.9   63.99  6184.6   63.34  6186.9   63.36  6214.6   63.64  6224.6   63.24
  6226.9   63.34  6244.6   64.14  6366.9   64.14  6396.9   64.14  6484.6   64.14
  6494.6   63.74  6616.9   64.17  6664.6   64.34  6676.9   63.97  6684.6   63.74
  6716.9    63.9  6724.6   63.94  6734.6   64.44  6796.9   64.86  6836.9   65.12
  6944.6   65.84  6946.9   65.81  6976.9   65.45  7006.9   65.08  7034.6   64.74
  7046.9   64.96  7084.6   65.64  7136.9   65.67  7274.6   65.74  7396.9   65.89
    7433   65.94
BR D #Mann= 7
  2354.7      .1  4049.7     .08  4950.2     .04  4979.4    .015  5025.5     .04
  5034.1     .08  6034.6      .1
BR D Banks=4979.4,5025.5
BC Design=,, 0 ,, 0 ,,,,,,
BC HTab HWMax=71.19

Type RM Length L Ch R = 1 ,30522.00,44.7,56,68.5
BEGIN DESCRIPTION:
WERNER
D/S XS of Bridge/Culvert/Weir
The downtream internal XS n-value was raised to 0.02 to reflect a small pipe on the d/s side. --KHH
END DESCRIPTION:
XS GIS Cut Line= 4
      3112270.77      13872157.5      3111296.46     13870873.56
       3110791.1     13869747.34      3109543.53     13867898.12
#Sta/Elev= 30
  2354.7   70.94  2474.7   69.64  2504.7   65.14  2524.7   63.84  4049.7   64.54
  4259.3   63.74  4289.3   62.34  4409.3   63.64  4769.3   62.04  4809.3   60.34
  4849.3   62.64  4870.8   60.61  4950.2   62.48 4977.69    60.2  4979.4   59.58
  4990.8   54.11  4991.2   50.12  5000.8   49.39  5008.6   49.96  5009.4   53.97
  5025.5   60.43  5028.1   61.58  5034.1   61.78  5754.6   64.44  5824.6   63.04
  6034.6   63.24  6094.6   64.64  6224.6   63.24  6944.6   65.84    7433   65.94
#Mann= 7 ,-1 , 0
  2354.7      .1       0  4049.7     .08       0  4950.2     .04       0
  4979.4    .015       0  5025.5     .04       0  5034.1     .08       0
  5754.6      .1       0
#XS Ineff= 3 ,-1
 5749.41 7068.56   65.75 5026.21 5498.82   62.29 4208.04 4977.79   61.65
Permanent Ineff=
       F       F       F
Bank Sta=4977.69,5028.1
XS Rating Curve= 0
Exp/Cntr=.5,.3

Type RM Length L Ch R = 1 ,30466.00,482.4,801,791.6
BEGIN DESCRIPTION:
Cross Section Xsec 24a
END DESCRIPTION:
XS GIS Cut Line= 5
  3112242.09219413872051.3859218      3111365.48     13870876.02
      3110970.17     13870072.24      3110891.57     13869776.38
 3109631.433495613867924.5208019
#Sta/Elev= 30
  2490.6      69  2550.6    67.7  2600.6    63.5  2760.6    65.4  2850.6    63.5
  3630.6    64.3  3956.9    62.4  4076.9    64.1  4216.9      62  4386.9    62.9
  4696.9    60.4  4776.9    61.8  4806.9    60.2  4872.6      63  4961.3   63.12
  4974.9   61.92  4988.6   54.11  4989.3    50.1  5000.2    49.4  5009.6   50.01
  5009.9   54.06  5022.5      62  5040.9   62.61  5318.7    61.2  5698.7    63.9
  6078.7    64.3  6128.7    62.4  6288.7    64.4  6648.7    63.6  7398.7    65.9
#Mann= 7 ,-1 , 0
  2490.6      .1       0  4076.9     .08       0  4961.3     .04       0
  4974.9    .015       0  5022.5     .04       0  5040.9     .08       0
  5698.7      .1       0
#XS Ineff= 1 ,-1
 6061.47  7398.7   64.94
Permanent Ineff=
       F
Bank Sta=4974.9,5022.5
XS Rating Curve= 0
Exp/Cntr=.3,.1

Type RM Length L Ch R = 1 ,29665.00,1467.5,950,613.7
BEGIN DESCRIPTION:
Cross Section x24
END DESCRIPTION:
XS GIS Cut Line= 4
      3112570.55     13871512.19      3111723.95     13870976.01
      3111395.98     13869064.34      3109767.36     13867551.97
#Sta/Elev= 30
  2446.8    66.3  2526.8    65.7  2576.8      64  2606.8      61  2626.8    63.5
  3728.9    64.3  3778.9    62.5  3878.9    63.7  4078.9      62  4298.9    62.6
  4368.9    60.9  4539.2   62.13  4954.7   61.18  4976.1   61.12  4990.8   53.04
  4994.6   48.79  5004.2    48.6  5009.3   49.11  5010.2    53.1  5021.8   60.92
  5035.7   61.31  5388.5    62.1  5478.5    60.6  5498.5      62  5638.5    62.5
  6268.5    62.8  6518.5      66  6668.5    63.5  6998.5    63.3    7611    66.7
#Mann= 8 ,-1 , 0
  2446.8      .1       0  3728.9     .08       0  4539.2     .05       0
  4954.7     .04       0  4976.1    .015       0  5021.8     .04       0
  5035.7     .08       0  6518.5      .1       0
#XS Ineff= 1 ,-1
 6496.45  7546.1   65.01
Permanent Ineff=
       F
Bank Sta=4976.1,5021.8
XS Rating Curve= 0
Exp/Cntr=.3,.1