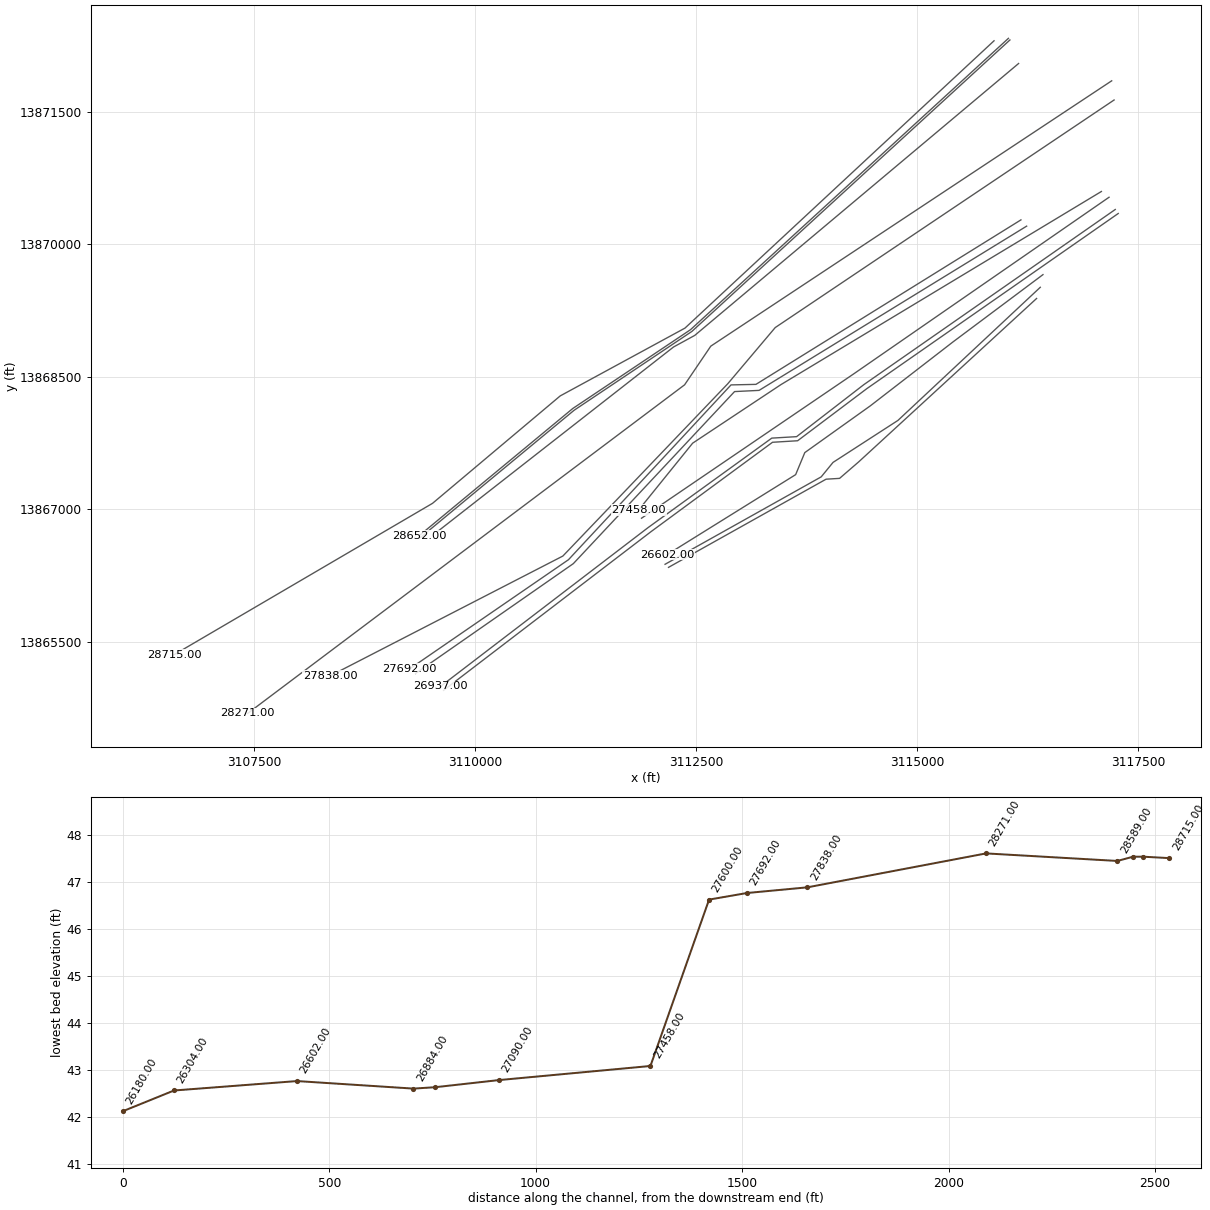
HEC-RAS study E101_00_00.prj: E101-00-00

--- E101_00_00.g01 (geometry) --- (continued)

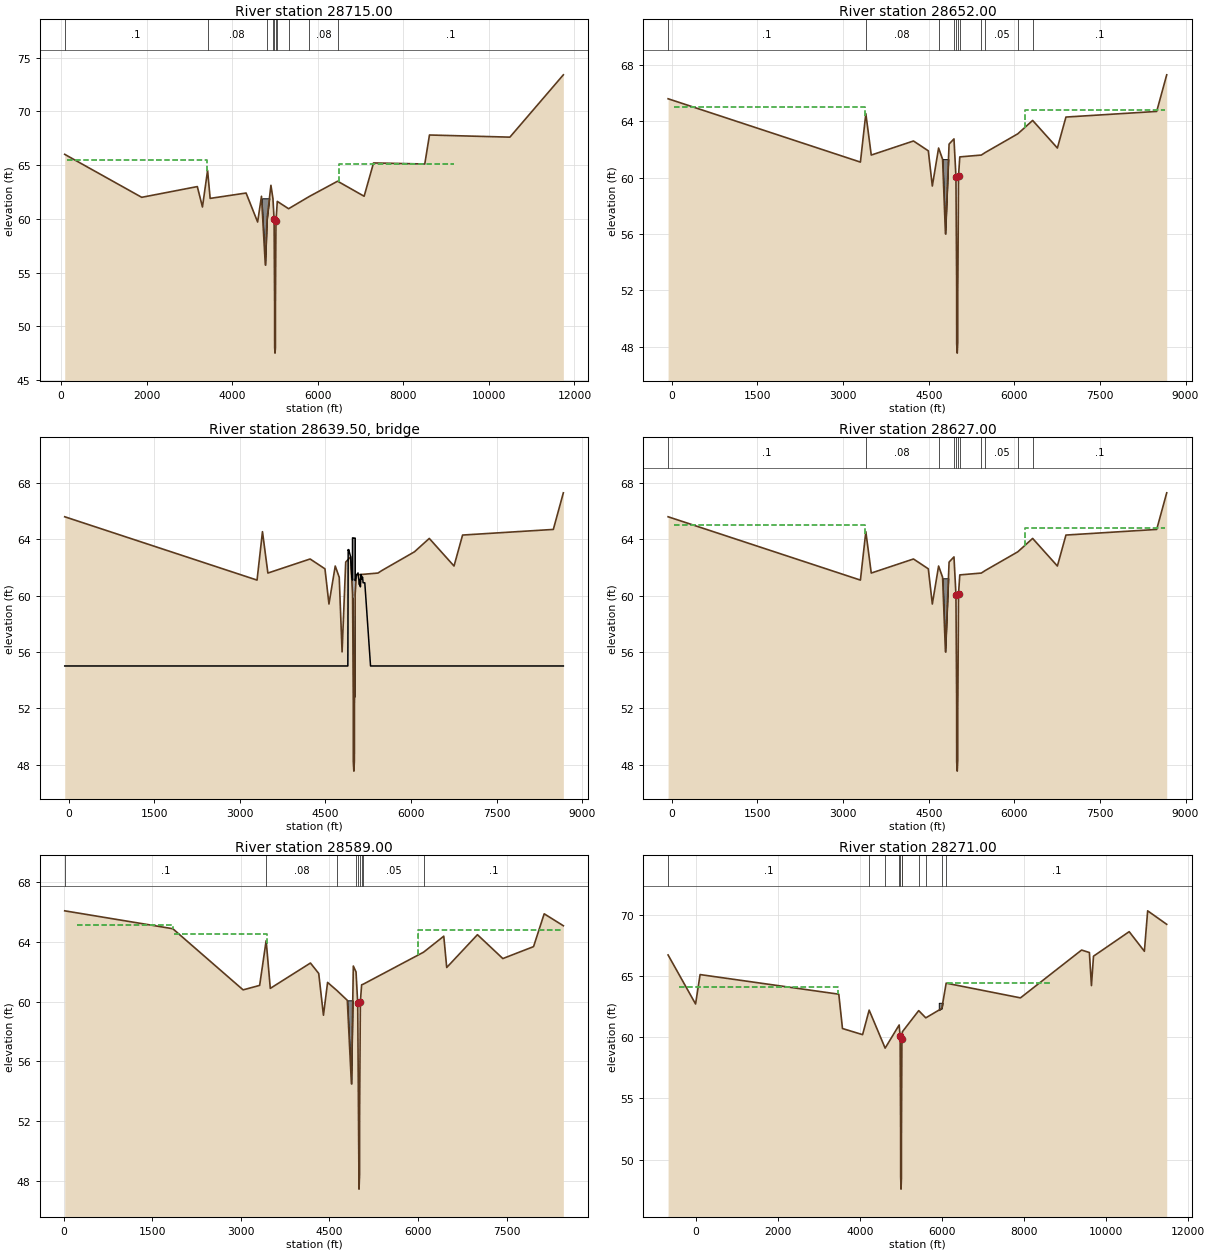
Type RM Length L Ch R = 1 ,28715.00,60.5,63,132.1
BEGIN DESCRIPTION:
Cross Section Xsec23b
END DESCRIPTION:
XS GIS Cut Line= 5
       3115867.5      13872300.8      3112370.97     13869050.37
      3110959.99     13868283.58       3109515.4     13867068.21
      3106590.29     13865355.04
#Sta/Elev= 30
    83.2      66  1883.2      62  3183.2      63  3303.2    61.1  3423.2    64.5
  3483.2    61.9  4323.2    62.4  4593.2    59.7  4683.2    62.1  4773.2    55.7
  4812.8   59.95  4903.9   63.12  4951.5   61.88  4978.1   59.94  4990.5   52.06
  4991.1   48.05  4999.8    47.5  5008.7   47.96  5009.6   52.02  5022.4   59.79
  5053.1   61.62  5317.5   60.94  5801.9   62.08  6463.1    63.5  7083.1    62.1
  7303.1    65.2  8500.9    65.1  8610.9    67.8 10490.9    67.6 11740.8    73.4
#Mann= 10 ,-1 , 0
    83.2      .1       0  3423.2     .08       0  4812.8      .1       0
  4951.5     .04       0  4978.1    .015       0  5022.4     .04       0
  5053.1     .05       0  5317.5     .08       0  5801.9     .08       0
  6463.1      .1       0
#XS Ineff= 2 ,-1
  141.84 3413.71   65.51    6487 9182.03   65.06
Permanent Ineff=
       F       F
#Block Obstruct= 1 ,-1
    4696 4892.99   61.91
Bank Sta=4978.1,5022.4
XS Rating Curve= 0
Exp/Cntr=.5,.3

Type RM Length L Ch R = 1 ,28652.00,24.8,25,31.8
BEGIN DESCRIPTION:
OXFORD FOOTBRIDGE u/s
Upstream Section of Bridge/Culvert/Weir
END DESCRIPTION:
XS GIS Cut Line= 4
      3116030.36     13872328.58      3112433.72     13869032.58
      3111101.72     13868140.87      3109364.39     13866702.16
#Sta/Elev= 30
   -66.4    65.6  3303.6    61.1  3398.6   64.54  3493.6    61.6  4233.6    62.6
  4493.6    61.9  4563.6    59.4  4673.6    62.1  4743.6    61.3  4793.6      56
  4857.4   62.38    4943   62.75 4976.61   60.14  4977.5   60.07  4989.7   52.65
  4990.8   48.16  5000.1   47.53  5009.3   48.29  5009.9    52.2  5012.1   52.82
  5022.4    60.1    5045   61.47  5422.1    61.6  5490.6   61.78  6061.6   63.11
  6321.6   64.06    6755    62.1    6905    64.3    8495    64.7  8670.7    67.3
#Mann= 11 ,-1 , 0
   -66.4      .1       0  3398.6     .08       0  4673.6      .1       0
    4943     .04       0 4976.61    .015       0  5012.1     .04       0
    5045     .05       0  5422.1     .08       0  5490.6     .05       0
  6061.6     .08       0  6321.6      .1       0
#XS Ineff= 4 ,-1
    33.1 3390.07      65 4912.53    4967      60    5032 5070.63      60
 6179.67 8647.75   64.83
Permanent Ineff=
       F       F       F       F
#Block Obstruct= 1 ,-1
 4740.48 4847.09   61.31
Bank Sta=4977.5,5022.4
XS Rating Curve= 0
Exp/Cntr=.5,.3

Type RM Length L Ch R = 3 ,28639.50,,,
BEGIN DESCRIPTION:
OXFORD FOOTBRIDGE
Structure ID: E101-00-00-22
END DESCRIPTION:
Bridge Culvert--1,0,-1,-1, 0
Deck Dist Width WeirC Skew NumUp NumDn MinLoCord MaxHiCord MaxSubmerge Is_Ogee
10,5,2.6,0, 28, 28, , , .95, 0, ,,,
   -66.4  4894.5  4900.4  4904.5  4909.3    4943  4961.5 4976.29  4976.4  4977.5
  5022.4  5023.6 5023.71  5024.2  5043.7  5073.6  5097.6  5104.7  5114.5  5122.1
  5124.5  5132.1  5142.1  5152.1  5162.1  5191.6  5292.1  8670.7
      55      55   63.26   63.21   63.27   62.76   61.47    61.1    64.1    64.1
   64.08   64.08   61.08   61.06   61.46   61.61   60.77   61.15   60.62   61.26
    61.5   61.42   61.17   61.31   60.91   60.91      55      55
                   63.25    63.2   63.15   62.75   61.31   60.16   60.16   59.89
   59.89   60.18   60.18   60.21   61.46    61.6   60.76   61.14   60.61    60.2
   60.25    60.4    61.1    61.3    60.9    60.9
   -66.4  4894.5  4900.4  4904.5  4909.3    4943  4961.5 4976.29  4976.4  4977.5
  5022.4  5023.6 5023.71  5024.2  5043.7  5073.6  5097.6  5104.7  5114.5  5122.1
  5124.5  5132.1  5142.1  5152.1  5162.1  5191.6  5292.1  8670.7
      55      55   63.26   63.21   63.27   62.76   61.47    61.1    64.1    64.1
   64.08   64.08   61.08   61.06   61.46   61.61   60.77   61.15   60.62   61.26
    61.5   61.42   61.17   61.31   60.91   60.91      55      55
                   63.25    63.2   63.15   62.75   61.31   60.16   60.16   59.89
   59.89   60.18   60.18   60.21   61.46    61.6   60.76   61.14   60.61    60.2
   60.25    60.4    61.1    61.3    60.9    60.9
Pier Skew, UpSta & Num, DnSta & Num=  ,4989.8, 2 ,4989.8, 2 , 0 , 0 , 0 ,,
       1       1
    50.2    60.9
       1       1
   50.13   60.83
Pier Skew, UpSta & Num, DnSta & Num=  ,5012.1, 2 ,5012.1, 2 , 0 , 0 , 0 ,,
       1       1
   51.68   60.89
       1       1
   51.61   60.82
BR Coef= 1 , 1 , 1 ,.9, 0 ,,,.8,0,1.2,0,
WSPro=,,,, 1 ,,,, 0 ,,,, 0 ,,,,-1 ,-1 ,-1 , 0 , 0 , 0 , 0 , 0
BC Design=,, 0 ,, 0 ,,,,,,
BC HTab HWMax=67.8

Type RM Length L Ch R = 1 ,28627.00,79.8,38,61.7
BEGIN DESCRIPTION:
OXFORD FOOTBRIDGE
Downstream Section of Bridge/Culvert/Weir
END DESCRIPTION:
XS GIS Cut Line= 4
      3116047.25     13872310.14      3112449.21     13869012.86
      3111116.68      13868120.8      3109380.33      13866682.9
#Sta/Elev= 30
   -66.4    65.6  3303.6    61.1  3398.6   64.54  3493.6    61.6  4233.6    62.6
  4493.6    61.9  4563.6    59.4  4673.6    62.1  4743.6    61.3  4793.6      56
  4857.4   62.38    4943   62.75 4976.61   60.14  4977.5   60.07  4989.7   52.65
  4990.8   48.16  5000.1   47.53  5009.3   48.29  5009.9    52.2  5012.1   52.82
  5022.4    60.1    5045   61.47  5422.1    61.6  5490.6   61.78  6061.6   63.11
  6321.6   64.06    6755    62.1    6905    64.3    8495    64.7  8670.7    67.3
#Mann= 11 ,-1 , 0
   -66.4      .1       0  3398.6     .08       0  4673.6      .1       0
    4943     .04       0 4976.61    .015       0  5012.1     .04       0
    5045     .05       0  5422.1     .08       0  5490.6     .05       0
  6061.6     .08       0  6321.6      .1       0
#XS Ineff= 4 ,-1
    33.1 3390.07      65 4912.53    4967      60    5032 5070.63      60
 6179.67 8647.75   64.83
Permanent Ineff=
       F       F       F       F
#Block Obstruct= 1 ,-1
  4735.6    4853   61.23
Bank Sta=4977.5,5022.4
XS Rating Curve= 0
Exp/Cntr=.5,.3

Type RM Length L Ch R = 1 ,28589.00,265.7,318,418.3
BEGIN DESCRIPTION:
Cross Section Xsec 23a
END DESCRIPTION:
XS GIS Cut Line= 4
      3116145.28     13872043.86      3112481.66     13868967.89
      3112241.92     13868836.85      3109575.83     13866752.19
#Sta/Elev= 30
    18.2    66.1  1848.2    64.9  3038.2    60.8  3318.2    61.1  3428.2    64.1
  3498.2    60.9  4178.2    62.6  4318.2    61.9  4398.2    59.1  4468.2    61.3
  4625.4   60.76  4801.9    60.1  4871.9    54.5  4903.9    62.4    4950      62
  4978.4   59.89  5000.3   47.44  5009.7   48.39  5010.4   52.37    5023      60
  5044.6   61.14  5071.2   61.18  6094.3   63.33  6435.1    64.4  6485.1    62.3
  7005.1    64.5  7435.1    62.9  7955.1    63.7  8135.1    65.9  8459.5    65.1
#Mann= 9 ,-1 , 0
    18.2      .1       0  3428.2     .08       0  4625.4      .1       0
    4950     .04       0  4978.4    .015       0    5023     .04       0
  5044.6     .12       0  5071.2     .05       0  6094.3      .1       0
#XS Ineff= 3 ,-1
  228.53 1851.85   65.13 1867.61 3435.78   64.56 6004.73  8459.5   64.82
Permanent Ineff=
       F       F       F
#Block Obstruct= 1 ,-1
 4798.04 4899.33    60.1
Bank Sta=4978.4,5023
XS Rating Curve= 0
Exp/Cntr=.3,.1

Type RM Length L Ch R = 1 ,28271.00,330.3,433,390
BEGIN DESCRIPTION:
Cross Section x23
END DESCRIPTION:
XS GIS Cut Line= 4
      3117198.55     13871848.11      3112663.29     13868846.49
      3112366.87     13868408.92      3107424.27     13864691.95
#Sta/Elev= 30
    -677    66.7      -7    62.7     103    65.1    3483    63.5    3573    60.7
    4063    60.2    4223    62.2  4612.7    59.1  4954.2   60.99  4977.8   60.07
  4990.1   52.19  4990.8   48.63  5000.1    47.6  5009.4   48.51    5010   52.02
  5021.6   59.84  5033.8   60.44  5430.7   62.16    5603   61.57  5993.4   62.34
  6100.1    64.4  7910.1    63.2  9400.1    67.1  9590.1    66.9  9640.1    64.2
  9690.1    66.6 10560.1    68.6 10930.1      67 11010.1    70.3 11474.4    69.2
#Mann= 11 ,-1 , 0
    -677      .1       0    4223     .08       0  4612.7      .1       0
  4954.2     .04       0  4977.8    .015       0  5021.6     .04       0
  5033.8     .12       0  5430.7     .08       0    5603     .05       0
  5993.4     .08       0  6100.1      .1       0
#XS Ineff= 2 ,-1
 -409.39    3471   64.08 6130.81 8679.28   64.41
Permanent Ineff=
       F       F
#Block Obstruct= 1 ,-1
 5919.17 6075.74    62.8
Bank Sta=4977.8,5021.6
XS Rating Curve= 0
Exp/Cntr=.3,.1

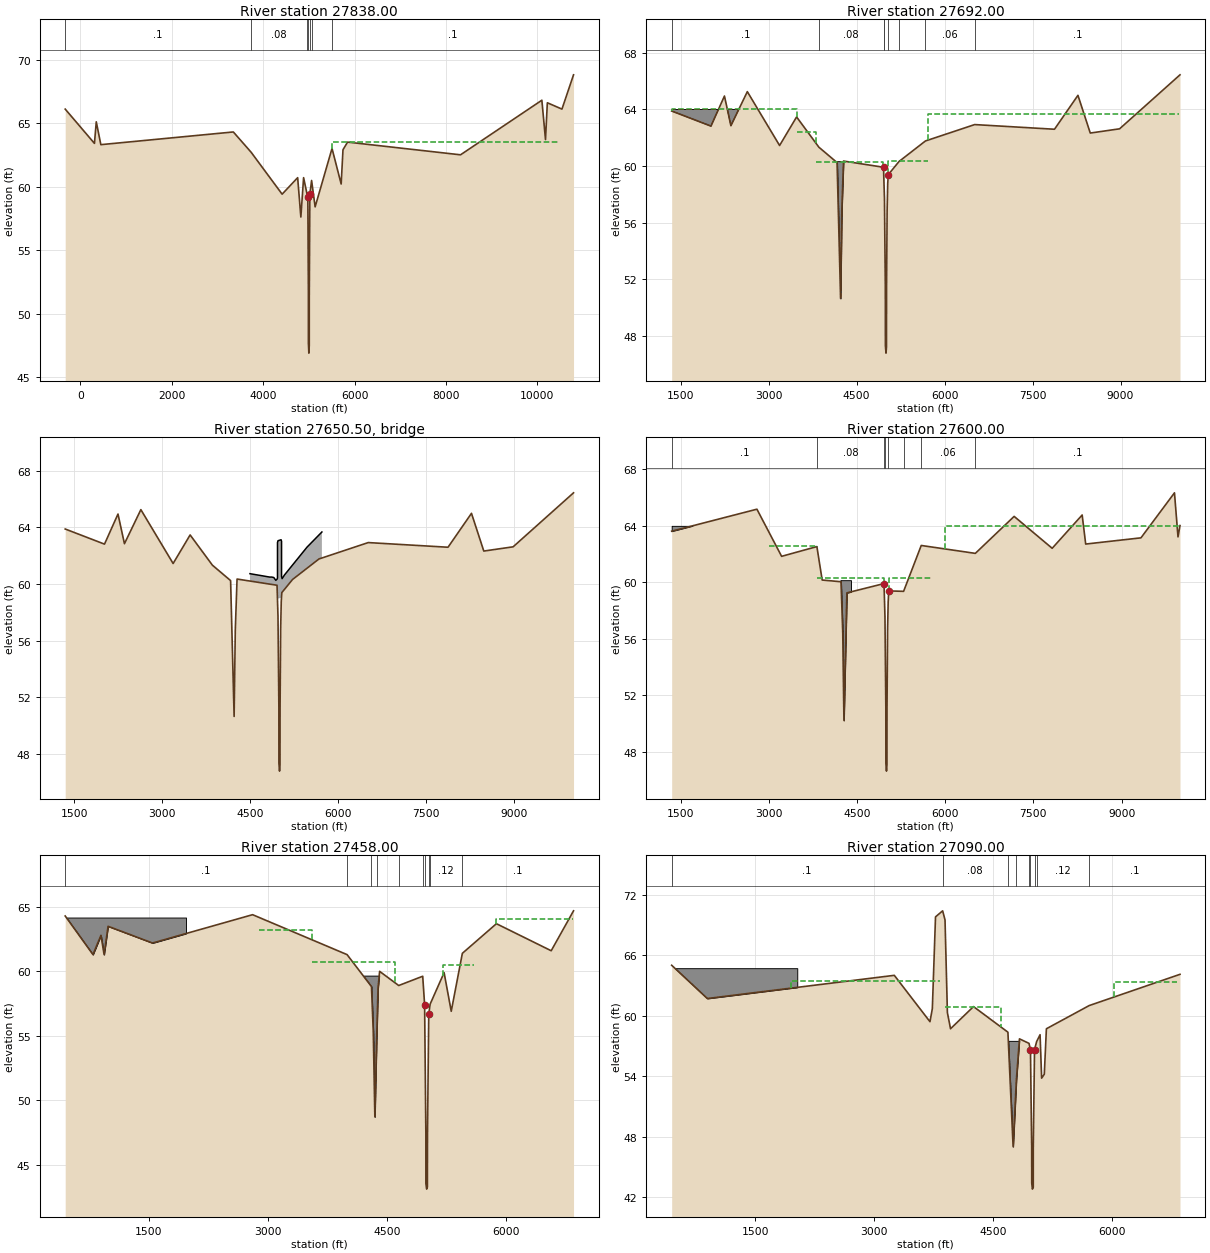
Type RM Length L Ch R = 1 ,27838.00,324.2,146,39.3
BEGIN DESCRIPTION:
Cross Section Xsec 22c
END DESCRIPTION:
XS GIS Cut Line= 5
      3117225.68      13871631.1      3113392.04     13869056.49
      3112854.94     13868420.63      3110989.92     13866471.94
       3108355.2     13865115.55
#Sta/Elev= 30
  -333.2    66.1   306.8    63.4   346.8    65.1   446.8    63.3  3346.8    64.3
  3736.8    62.7  4414.7    59.4  4754.7    60.7  4824.7    57.6  4884.7    60.7
  4966.2    59.3  4977.1   59.21  4989.6   51.64  4990.2    47.6  4999.7   46.88
  5008.7   47.48  5009.1   51.45  5021.9   59.39  5059.6   60.48  5137.1    58.4
  5506.9      63  5706.9    60.2  5746.9    62.9  5846.9    63.5  8319.6    62.5
 10099.6    66.8 10179.6    63.7 10219.6    66.6 10539.6    66.1 10792.9    68.8
#Mann= 7 ,-1 , 0
  -333.2      .1       0  3736.8     .08       0  4966.2     .04       0
  4977.1    .015       0  5021.9     .04       0  5059.6     .12       0
  5506.9      .1       0
#XS Ineff= 2 ,-1
  -333.2  3346.8   63.33 5501.9710455.48   63.47
Permanent Ineff=
       F       F
Bank Sta=4977.1,5021.9
XS Rating Curve= 0
Exp/Cntr=.5,.3

Type RM Length L Ch R = 1 ,27692.00,77.6,92,82
BEGIN DESCRIPTION:
VICTORIA u/s **See Note**
Upstream Section of Bridge/Culvert/Weir
Channel Data Skewed 40 degrees by adjusting data by 0.766 then recentering data on 5000 by adding 12.58 to all station. --KHH
END DESCRIPTION:
XS GIS Cut Line= 5
 3116171.801244513870274.7332951        3113174.     13868413.95
      3112892.15     13868407.93      3111053.27     13866430.41
 3109256.811455813865195.5582795
#Sta/Elev= 30
 1347.18   63.89 2017.18   62.82 2247.18   64.95 2357.18   62.85 2637.18   65.26
 3187.18   61.45 3477.18   63.47 3857.18   61.33 4167.18   60.24 4227.18   50.63
 4247.18   56.74 4277.18   60.35 4958.98   59.91  4975.2    57.7 4990.18   51.32
 4990.95   47.31 5001.58   46.76 5009.65   47.19 5010.66   51.17 5020.59   56.82
 5030.76   58.76 5040.62   59.39 5224.02   60.32 5673.92   61.77 6513.92   62.93
 7874.32    62.6 8274.32      65 8484.32   62.33 8984.32   62.6310014.22   66.45
#Mann= 8 ,-1 , 0
 1347.18      .1       0 3857.18     .08       0 4958.98     .04       0
  4975.2    .015       0 5030.76     .04       0 5224.02     .12       0
 5673.92     .06       0 6513.92      .1       0
#XS Ineff= 5 ,-1
 1347.18 3476.78      64 3476.78 3807.78   62.41 5043.87 5724.17   60.38
 3807.78 4957.03   60.26 5724.17 10003.2   63.68
Permanent Ineff=
       F       F       F       F       F
#Block Obstruct= 2 ,-1
 4143.58 4277.07   60.34 1347.18    2500      64
Bank Sta=4958.98,5040.62
XS Rating Curve= 0
Exp/Cntr=.5,.3

Type RM Length L Ch R = 3 ,27650.50,,,
BEGIN DESCRIPTION:
VICTORIA  Skewed 40 degrees
Structure ID: E101-00-00-21
END DESCRIPTION:
Bridge Culvert--1,0,-1,-1, 0
Deck Dist Width WeirC Skew NumUp NumDn MinLoCord MaxHiCord MaxSubmerge Is_Ogee
10,63,2.6,40, 16, 15, 0, , .95, 0, ,,,
 4497.18 4833.42 4867.58 4903.05 4937.75  4962.5 4966.56 4966.63 4974.52 5028.15
 5035.96 5036.04 5045.54 5084.14 5470.54 5723.92
   60.73   60.49   60.49   60.46   60.26   60.36   60.43   62.93   63.06   63.13
   63.02   60.52   60.38   60.63   62.61   63.68
                                                   58.83   58.83   58.96   59.03
   58.92   58.92   58.78
 4547.55 4833.42 4867.58 4903.05 4937.75  4962.5 4966.56 4966.63 4974.52 5028.15
 5035.96 5036.04 5045.54 5084.14 5592.43
   60.73   60.49   60.49   60.46   60.26   60.36   60.43   62.93   63.06   63.13
   63.02   60.52   60.38   60.63   62.61
                                                   58.83   58.83   58.96   59.03
   58.92   58.92   58.78
Pier Skew, UpSta & Num, DnSta & Num=  ,5921.228, 2 ,5921.228, 2 , 0 , 0 , 0 ,,
     1.5     1.5
   56.06   59.85
     1.5     1.5
   55.92   59.71
Pier Skew, UpSta & Num, DnSta & Num=  ,5928.854, 2 ,5928.854, 2 , 0 , 0 , 0 ,,
       2       2
   53.86   59.86
       2       2
   53.72   59.72
Pier Skew, UpSta & Num, DnSta & Num=  ,5964.847, 2 ,5964.847, 2 , 0 , 0 , 0 ,,
       2       2
   49.06   59.89
       2       2
   48.92   59.75
Pier Skew, UpSta & Num, DnSta & Num=  ,5986.774, 2 ,5986.774, 2 , 0 , 0 , 0 ,,
     1.5     1.5
   54.47   59.91
     1.5     1.5
   54.33   59.77
BR Coef= 1 , 1 , 0 ,.9, 0 ,,,.8,0,1.2,0,
WSPro=,,,, 1 ,,,, 0 ,,,, 0 ,,,,-1 ,-1 ,-1 , 0 , 0 , 0 , 0 , 0
BC Design=,, 0 ,, 0 ,,,,,,
BC HTab HWMax=69.01

Type RM Length L Ch R = 1 ,27600.00,76.8,142,211.8
BEGIN DESCRIPTION:
VICTORIA  **See Note**
Downstream Section of Bridge/Culvert/Weir
Channel Data Skewed 40 degrees by adjusting data by 0.766 then recentering data on 5000 by adding 12.58 to all station. --KHH
END DESCRIPTION:
XS GIS Cut Line= 5
 3116236.419881213870204.0161783      3113209.39     13868345.95
      3112932.02     13868332.35      3111108.35     13866386.21
 3109324.267479513865143.9274962
#Sta/Elev= 30
 1347.55   63.62 2797.55   65.18 3217.55   61.84 3817.55   62.53 3907.55   60.16
 4227.55   60.04 4257.55   56.41 4277.55   50.21 4327.55   59.25 4959.25   59.91
 4975.26   57.56 4990.04   51.18 4990.81   47.17  5001.3   46.62 5009.27   47.05
 5010.27   51.03 5020.07   56.68  5030.1   58.62 5039.83   59.39 5292.43   59.36
 5592.43   62.61 6512.43   62.05 7172.43   64.67 7819.53   62.41 8329.53   64.77
 8389.53   62.71 9329.53   63.15 9899.53   66.34 9959.53   63.22 9993.53   64.02
#Mann= 8 ,-1 , 0
 1347.55      .1       0 3817.55     .08       0 4959.25     .04       0
 4975.26    .015       0  5030.1     .04       0 5292.43     .12       0
 5592.43     .06       0 6512.43      .1       0
#XS Ineff= 4 ,-1
    600410027.03      64    3000  3816.3   62.54 5044.17 5781.17    60.3
  3816.3 4956.57    60.3
Permanent Ineff=
       F       F       F       F
#Block Obstruct= 2 ,-1
 1347.55 2907.88      64 4217.42 4397.63   60.15
Bank Sta=4959.25,5039.83
XS Rating Curve= 0
Exp/Cntr=.5,.3

Type RM Length L Ch R = 1 ,27458.00,363.6,368,375.2
BEGIN DESCRIPTION:
Cross Section Xsec 22b
END DESCRIPTION:
XS GIS Cut Line= 4
      3117081.91     13870595.94      3113457.23     13868411.47
      3112457.99     13867748.81      3111847.53     13866993.51
#Sta/Elev= 30
   447.9    64.3   797.9    61.3   897.9    62.8   937.9    61.3   987.9    63.5
  1547.9    62.2  2807.9    64.4  3997.9    61.3  4305.1   58.82  4327.9    55.3
  4347.9    48.7  4369.7    54.6  4387.9    58.7  4407.9      60  4648.5    58.9
  4950.6   59.62  4974.5   57.42  4990.2   47.47  4990.5   43.52  5000.3   43.09
  5009.3   43.26  5010.6   47.31  5026.6   56.66  5043.8   57.45  5219.9    59.9
  5309.9    56.9  5449.9    61.4  5878.9    63.7  6568.9    61.6  6850.1    64.7
#Mann= 10 ,-1 , 0
   447.9      .1       0  3997.9     .08       0  4305.1     .04       0
  4369.7     .05       0  4648.5     .08       0  4950.6     .04       0
  4974.5    .015       0  5026.6     .04       0  5043.8     .12       0
  5449.9      .1       0
#XS Ineff= 5 ,-1
 2884.95 3557.92   63.25 3557.92    4602    60.7
    5200    5600   60.49 5869.19 6845.55   64.08
Permanent Ineff=
       F       F       F       F       F
#Block Obstruct= 2 ,-1
   447.9 1968.94   64.18 4208.83 4434.99   59.67
Bank Sta=4974.5,5026.6
XS Rating Curve= 0
Exp/Cntr=.3,.1

Type RM Length L Ch R = 1 ,27090.00,217.9,153,83.9
BEGIN DESCRIPTION:
Cross Section Xsec 22a
END DESCRIPTION:
XS GIS Cut Line= 3
      3117168.71     13870530.84       3114282.4     13868534.35
      3111879.47     13866899.79
#Sta/Elev= 30
     446      65     896    61.7    3256      64    3706    59.4    3736    60.7
    3776    69.8    3866    70.4    3896    69.5    3926    60.3  3965.5    58.7
  4255.5    60.9  4689.9   58.36  4755.5      47  4796.7   53.63  4835.5    57.7
  4956.3   57.25  4974.4    56.6  4989.6   47.11  4990.6   43.36  4999.3   42.79
  5009.8   42.99  5009.9   46.94  5025.7   56.63  5052.4   57.43  5095.6   58.11
  5115.4    53.8    5149   54.19  5175.5    58.7  5715.5      61  6861.7    64.1
#Mann= 9 ,-1 , 0
     446      .1       0    3866     .08       0  4689.9     .04       0
  4796.7     .08       0  4956.3     .04       0  4974.4    .015       0
  5025.7     .04       0  5052.4     .12       0  5715.5      .1       0
#XS Ineff= 3 ,-1
 1952.72 3828.21   63.48 6034.67 6823.48   63.29 3894.41 4600.47   60.85
Permanent Ineff=
       F       F       F
#Block Obstruct= 2 ,-1
     446 2031.06   64.71 4628.05  4848.7    57.5
Bank Sta=4974.4,5025.7
XS Rating Curve= 0
Exp/Cntr=.5,.3

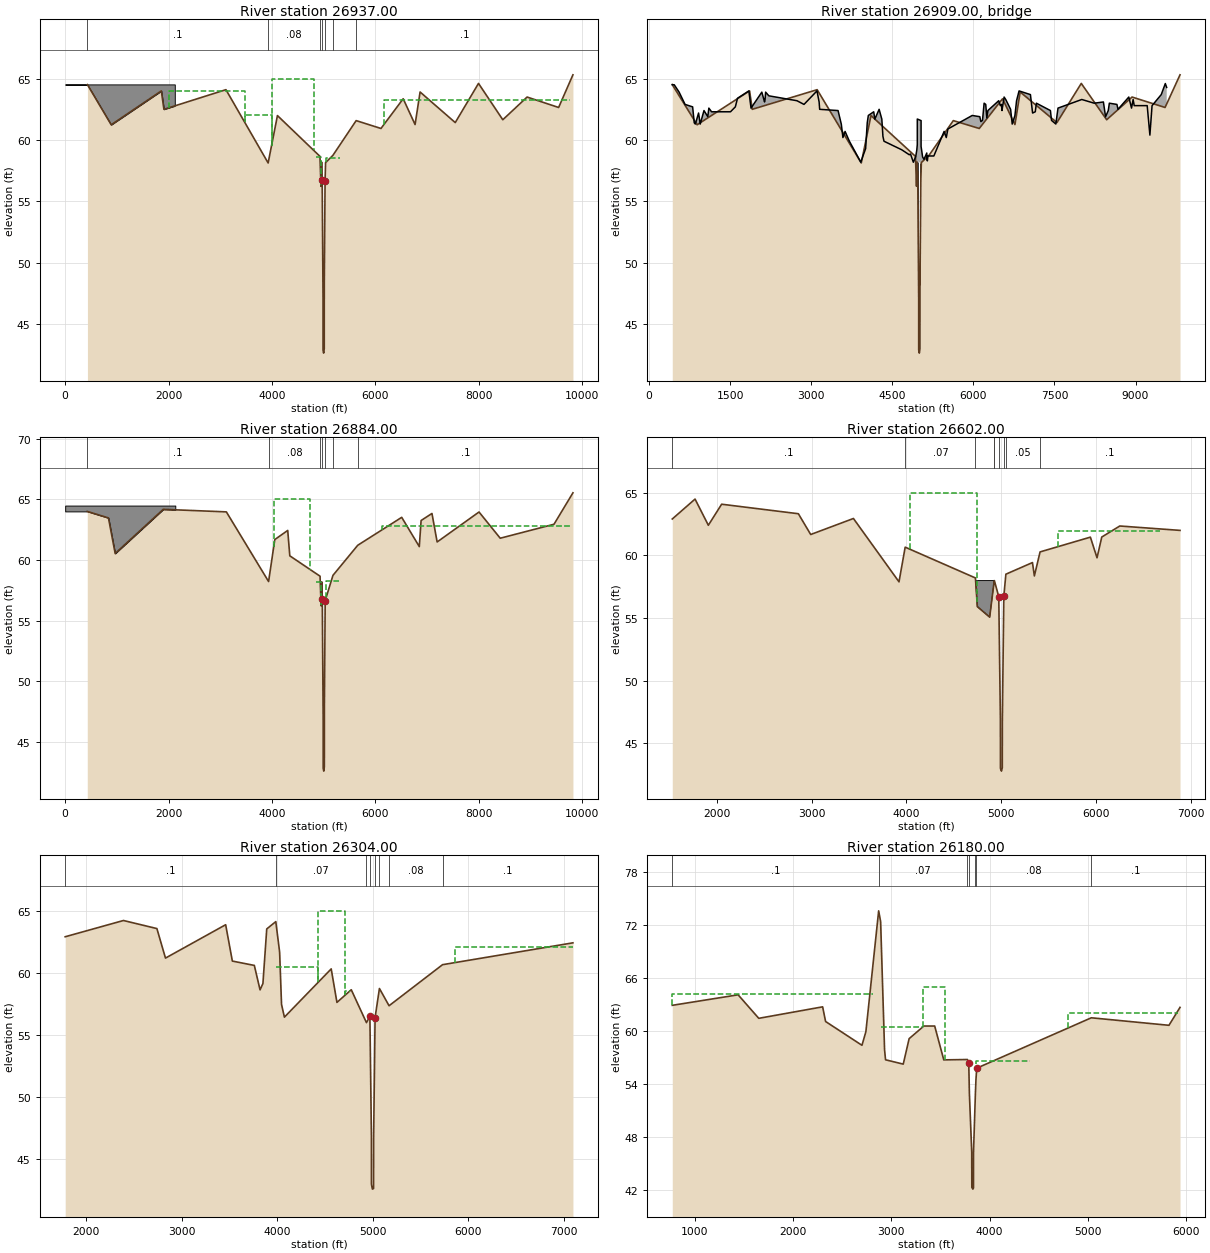
Type RM Length L Ch R = 1 ,26937.00,46.8,53,63.3
BEGIN DESCRIPTION:
DISTRIBUTION CENTER u/s
Upstream Section of Bridge/Culvert/Weir
END DESCRIPTION:
XS GIS Cut Line= 6
      3117238.78     13870392.25      3114394.49     13868410.85
      3113633.81     13867822.45      3113353.14     13867805.86
      3111953.86      13866793.6      3109605.53     13864996.82
#Sta/Elev= 30
   430.3   64.51   890.3   61.24  1860.3      64  1910.3    62.5  3110.3    64.1
  3926.7   58.13  4106.7   61.99  4928.8   58.67  4948.9   56.23  4960.5   58.21
  4971.9   56.77  4989.2   46.92  4989.5   42.88  5000.8   42.64  5011.9   42.99
  5012.9    48.2  5028.3   56.66  5037.9   58.16  5179.8   58.75  5629.6   61.58
  6109.6   60.94  6539.6   63.36  6769.6   61.26  6866.6   63.91  7546.6   61.42
  7996.6   64.61  8466.6   61.65  8936.6    63.5  9546.6   62.65  9823.5   65.31
#Mann= 7 ,-1 , 0
   430.3      .1       0  3926.7     .08       0  4928.8     .04       0
  4971.9    .015       0  5028.3     .04       0  5179.8     .12       0
  5629.6      .1       0
#XS Ineff= 6 ,-1
    2000    3471      64    3471    3992      62    3992    4807      65
 4845.26  4949.4   58.63  5045.4 5325.95   58.57 6161.25  9770.6   63.27
Permanent Ineff=
       F       F       F       F       F       F
#Block Obstruct= 2 , 0
       0 2120.67   64.53               0
Bank Sta=4971.9,5028.3
XS Rating Curve= 0
Exp/Cntr=.5,.3

Type RM Length L Ch R = 3 ,26909.00,,,
BEGIN DESCRIPTION:
DISTRIBUTION CENTER
Structure ID: E101-00-00-20
END DESCRIPTION:
Bridge Culvert--1,0,-1,-1, 0
Deck Dist Width WeirC Skew NumUp NumDn MinLoCord MaxHiCord MaxSubmerge Is_Ogee
10,36,2.6,0, 108, 108, , , .95, 0, ,,,
   430.3   467.1   557.1   667.1   807.1   837.1   857.1   917.1   947.1  1017.1
  1087.1  1107.1  1157.1  1507.1  1597.1  1637.1  1847.1  1887.1  2087.1  2137.1
  2147.1  2157.1  2217.1  2737.1  2867.1  3107.1  3147.1  3157.1  3497.1  3557.1
  3587.1  3627.1  3707.1  3917.1  4007.1  4037.1  4057.1  4157.1  4177.1  4257.1
  4307.1  4327.1  4347.1  4677.1  4814.5  4837.7    4890  4933.4    4953    4963
  4963.1  5033.1  5033.2  5061.5  5086.8  5138.5  5139.3  5149.3  5159.3  5269.3
  5459.3  5499.3  5529.3  5979.3  6119.3  6139.3  6169.3  6199.3  6229.3  6249.3
  6269.3  6469.3  6499.3  6519.3  6529.3  6569.3  6599.3  6689.3  6719.3  6769.3
  6799.3    6846    7056    7096    7146    7166    7426    7446    7526    7566
    8006    8236    8406    8446    8496    8516    8656    8676    8876    8926
    8956    8976    9216    9266    9306    9476  9551.4  9576.6
   64.51    64.5    63.9    62.9    62.7    61.4    61.3    62.2    61.3    62.4
    61.9    62.6    62.3    62.3    62.7    63.4      64    62.6    63.9    63.1
    63.3    63.9    63.6    63.2    62.9      64    63.1    62.5    62.4    61.3
    60.2    60.7    59.9    58.2    59.3    61.4      62    62.3    61.7    62.5
    61.7    60.3    59.9    59.2    58.8   58.86   58.19   58.64   59.16   59.61
   61.71   61.58   59.48   58.62   58.43   58.94    58.5    58.3    58.7    58.7
    60.7    60.2    60.9      62    61.9    61.5    61.6      63    62.9    61.8
    62.4    63.2    62.8    62.9    62.4    63.5    63.3    62.5    61.3      62
    63.2      64    63.7    62.2    62.3      63    62.4    61.6    61.3    62.6
    63.3      63    63.1    61.9    62.4      63    62.9    62.5    63.5    62.6
    63.3    62.8    62.8    60.4    62.8    63.7    64.6   64.28
                                                                                
                                                                                
                                                                                
                                                                                
                                                                      56   58.26
   58.26   58.13   58.13   57.27
                                                                                
                                                                                
                                                                                
                                                                                
                                                                
     427   467.1   557.1   667.1   807.1   837.1   857.1   917.1   947.1  1017.1
  1087.1  1107.1  1157.1  1507.1  1597.1  1637.1  1847.1  1887.1  2087.1  2137.1
  2147.1  2157.1  2217.1  2737.1  2867.1  3107.1  3147.1  3157.1  3497.1  3557.1
  3587.1  3627.1  3707.1  3917.1  4007.1  4037.1  4057.1  4157.1  4177.1  4257.1
  4307.1  4327.1  4347.1  4677.1  4814.5  4837.7    4890  4933.4    4953    4963
  4963.1  5033.1  5033.2  5061.5  5086.8  5138.5  5139.3  5149.3  5159.3  5269.3
  5459.3  5499.3  5529.3  5979.3  6119.3  6139.3  6169.3  6199.3  6229.3  6249.3
  6269.3  6469.3  6499.3  6519.3  6529.3  6569.3  6599.3  6689.3  6719.3  6769.3
  6799.3    6846    7056    7096    7146    7166    7426    7446    7526    7566
    8006    8236    8406    8446    8496    8516    8656    8676    8876    8926
    8956    8976    9216    9266    9306    9476  9551.4    9643
   64.01    64.5    63.9    62.9    62.7    61.4    61.3    62.2    61.3    62.4
    61.9    62.6    62.3    62.3    62.7    63.4      64    62.6    63.9    63.1
    63.3    63.9    63.6    63.2    62.9      64    63.1    62.5    62.4    61.3
    60.2    60.7    59.9    58.2    59.3    61.4      62    62.3    61.7    62.5
    61.7    60.3    59.9    59.2    58.8   58.86   58.19   58.64   59.16   59.61
   61.71   61.58   59.48   58.62   58.43   58.94    58.5    58.3    58.7    58.7
    60.7    60.2    60.9      62    61.9    61.5    61.6      63    62.9    61.8
    62.4    63.2    62.8    62.9    62.4    63.5    63.3    62.5    61.3      62
    63.2      64    63.7    62.2    62.3      63    62.4    61.6    61.3    62.6
    63.3      63    63.1    61.9    62.4      63    62.9    62.5    63.5    62.6
    63.3    62.8    62.8    60.4    62.8    63.7    64.6    64.9
                                                                                
                                                                                
                                                                                
                                                                                
                                                                      56   58.26
   58.26   58.13   58.13   57.27
                                                                                
                                                                                
                                                                                
                                                                                
                                                                
Pier Skew, UpSta & Num, DnSta & Num=  ,4981.7, 2 ,4981.7, 2 , 0 , 0 , 0 ,,
     1.5     1.5
   48.07   59.22
     1.5     1.5
   48.04   59.19
Pier Skew, UpSta & Num, DnSta & Num=  ,5012.9, 2 ,5012.9, 2 , 0 , 0 , 0 ,,
     1.5     1.5
   43.29   59.17
     1.5     1.5
   43.26   59.14
Abutment Skew #Up #Dn= , 2 , 2
  5044.5 5068.39
   42.99   58.05
  5044.5 5068.39
   42.96   58.02
BR Coef= 1 , 1 , 1 ,.9, 0 ,,,.8,0,1.2,0,
WSPro=,,,, 1 ,,,, 0 ,,,, 0 ,,,,-1 ,-1 ,-1 , 0 , 0 , 0 , 0 , 0
BC Design=,, 0 ,, 0 ,,,,,,
BC HTab HWMax=66.61

Type RM Length L Ch R = 1 ,26884.00,165.6,282,373.1
BEGIN DESCRIPTION:
DISTRIBUTION CENTER
Downstream Section of Bridge/Culvert/Weir
END DESCRIPTION:
XS GIS Cut Line= 6
      3117272.65     13870347.04      3114428.13     13868365.48
      3113645.57     13867776.13      3113361.43     13867758.85
      3111987.96     13866748.53       3109640.3     13864952.27
#Sta/Elev= 30
     427   64.01     837   63.47     967   60.54    1897   64.18    3117   63.97
  3933.7   58.23  4053.7   61.69  4303.7   62.44  4343.7   60.35  4928.8   58.67
  4948.9   56.23  4960.5   58.21  4971.9   56.77  4989.2   46.89  4989.5   42.85
  5000.8   42.61  5011.9   42.96  5012.9   48.17  5028.3   56.66  5178.5   58.74
    5658   61.22    6508   63.52    6848   61.11    6883   63.26    7093   63.84
    7193   61.49    8003   63.96    8413    61.8    9453   62.95  9819.1   65.54
#Mann= 7 ,-1 , 0
     427      .1       0  3933.7     .08       0  4928.8     .04       0
  4971.9    .015       0  5028.3     .04       0  5178.5     .12       0
    5658      .1       0
#XS Ineff= 5 ,-1
    2000    4032    60.5    4032    4740      65  4841.6  4949.4    58.2
  5045.4 5318.07    58.3 6129.73 9754.63   62.78
Permanent Ineff=
       F       F       F       F       F
#Block Obstruct= 2 , 0
       0 2129.55   64.49               0
Bank Sta=4971.9,5028.3
XS Rating Curve= 0
Exp/Cntr=.5,.3

Type RM Length L Ch R = 1 ,26602.00,304.6,298,235.8
BEGIN DESCRIPTION:
Cross Section x22
END DESCRIPTION:
XS GIS Cut Line= 6
      3116421.09     13869655.47      3115405.47     13868895.92
      3114467.97      13868171.1      3113726.61     13867642.02
       3113623.1     13867392.65      3112167.62     13866487.07
#Sta/Elev= 30
  1533.5   62.91  1773.5    64.5  1913.5   62.41  2053.5   64.09  2861.7   63.33
  2991.7   61.67  3441.7   62.95  3921.7   57.89  3986.8   60.66  4726.8    58.2
  4746.8   55.91  4876.8   55.07  4925.1   57.99  4926.9   57.97  4972.5    56.7
  4989.5   47.01  4990.4   42.98  5000.9   42.77  5009.6   43.05  5010.3   46.81
  5025.8   56.75  5047.5    58.5  5327.5   59.43  5347.5   58.36  5407.5   60.28
  5937.5   61.46  6007.5   59.81  6057.5   61.47  6247.5   62.35  6881.7      62
#Mann= 9 ,-1 , 0
  1533.5      .1       0  3986.8     .07       0  4726.8    .026       0
  4925.1     .07       0  4926.9     .04       0  4972.5    .015       0
  5025.8     .04       0  5047.5     .05       0  5407.5      .1       0
#XS Ineff= 4 ,-1
  3572.1    4034    60.5    4034    4746      65
    5595 6669.03   61.97
Permanent Ineff=
       F       F       F       F
#Block Obstruct= 1 ,-1
 4727.51 4925.16   57.99
Bank Sta=4972.5,5025.8
XS Rating Curve= 0
Exp/Cntr=.3,.1

Type RM Length L Ch R = 1 ,26304.00,184.4,124,49.9
BEGIN DESCRIPTION:
Cross Section Xsec 21b
END DESCRIPTION:
XS GIS Cut Line= 5
      3116390.71     13869512.24      3114780.47     13868006.17
      3114045.93     13867531.08       3113912.5     13867367.75
      3112145.92     13866378.56
#Sta/Elev= 30
    1781   62.91    2391   64.22    2741   63.57    2831   61.19    3461   63.88
    3531   60.95    3761    60.6    3821   58.63    3851   59.14    3891   63.54
  3985.8   64.13  4025.8   61.68  4045.8   57.46  4075.8   56.43  4565.8   60.32
  4625.8   57.62  4775.8   58.64  4934.7   55.99  4970.7   56.49  4986.7    46.9
  4987.3   42.95  4997.2   42.57  5009.1   42.62  5009.4   42.79  5009.8   46.63
    5025   56.39  5070.6   58.74  5171.5   57.35  5731.5   60.66  7096.2   62.42
#Mann= 8 ,-1 , 0
    1781      .1       0  3985.8     .07       0  4934.7     .04       0
  4970.7    .015       0    5025     .04       0  5070.6     .05       0
  5171.5     .08       0  5731.5      .1       0
#XS Ineff= 6 ,-1
 2119.78 3956.66   62.52 3983.52    4429   60.44    4709 4762.02   58.57
 5092.99 5561.86   58.31    5861  7096.2   62.06    4429    4709      65
Permanent Ineff=
       F       F       F       F       F       F
Bank Sta=4970.7,5025
XS Rating Curve= 0
Exp/Cntr=.5,.3

Type RM Length L Ch R = 1 ,26180.00,69.2,83,64.7
BEGIN DESCRIPTION:
WHITNEY u/s
Upstream Section of Bridge/Culvert/Weir
END DESCRIPTION:
XS GIS Cut Line= 5
      3116348.89     13869385.61       3114336.4     13867537.19
      3114120.08     13867350.49      3113967.42     13867341.28
      3112184.98     13866343.84
#Sta/Elev= 30
 771.064   62.921441.064   64.111651.064   61.452301.064   62.752331.064   61.09
2701.064    58.42741.064   59.942871.064   73.612891.064   72.392931.064   57.89
2941.064   56.763121.064   56.273181.064   59.153331.064   60.583441.064   60.58
3533.564   56.753774.148   56.793787.553   56.453794.218   52.923817.889   46.35
3818.885   42.34 3829.61   42.133835.584   42.273835.968   46.283855.502   53.03
3861.094   54.553868.754   55.81 5034.63   61.51 5824.63   60.66 5937.23   62.69
#Mann= 7 ,-1 , 0
 771.064      .1       02871.064     .07       03774.148     .04       0
3794.218    .015       03855.502     .04       03861.094     .08       0
 5034.63      .1       0
#XS Ineff= 6 ,-1
  771.06 2813.24   64.19 2898.35    3323   60.52    3323    3541      65
    3541 3782.51   56.47    3866 4411.35    56.6    4801 5919.62      62
Permanent Ineff=
       F       F       F       F       F       F
Bank Sta=3787.553,3868.754
XS Rating Curve= 0
Skew Angle= 40
Exp/Cntr=.5,.3