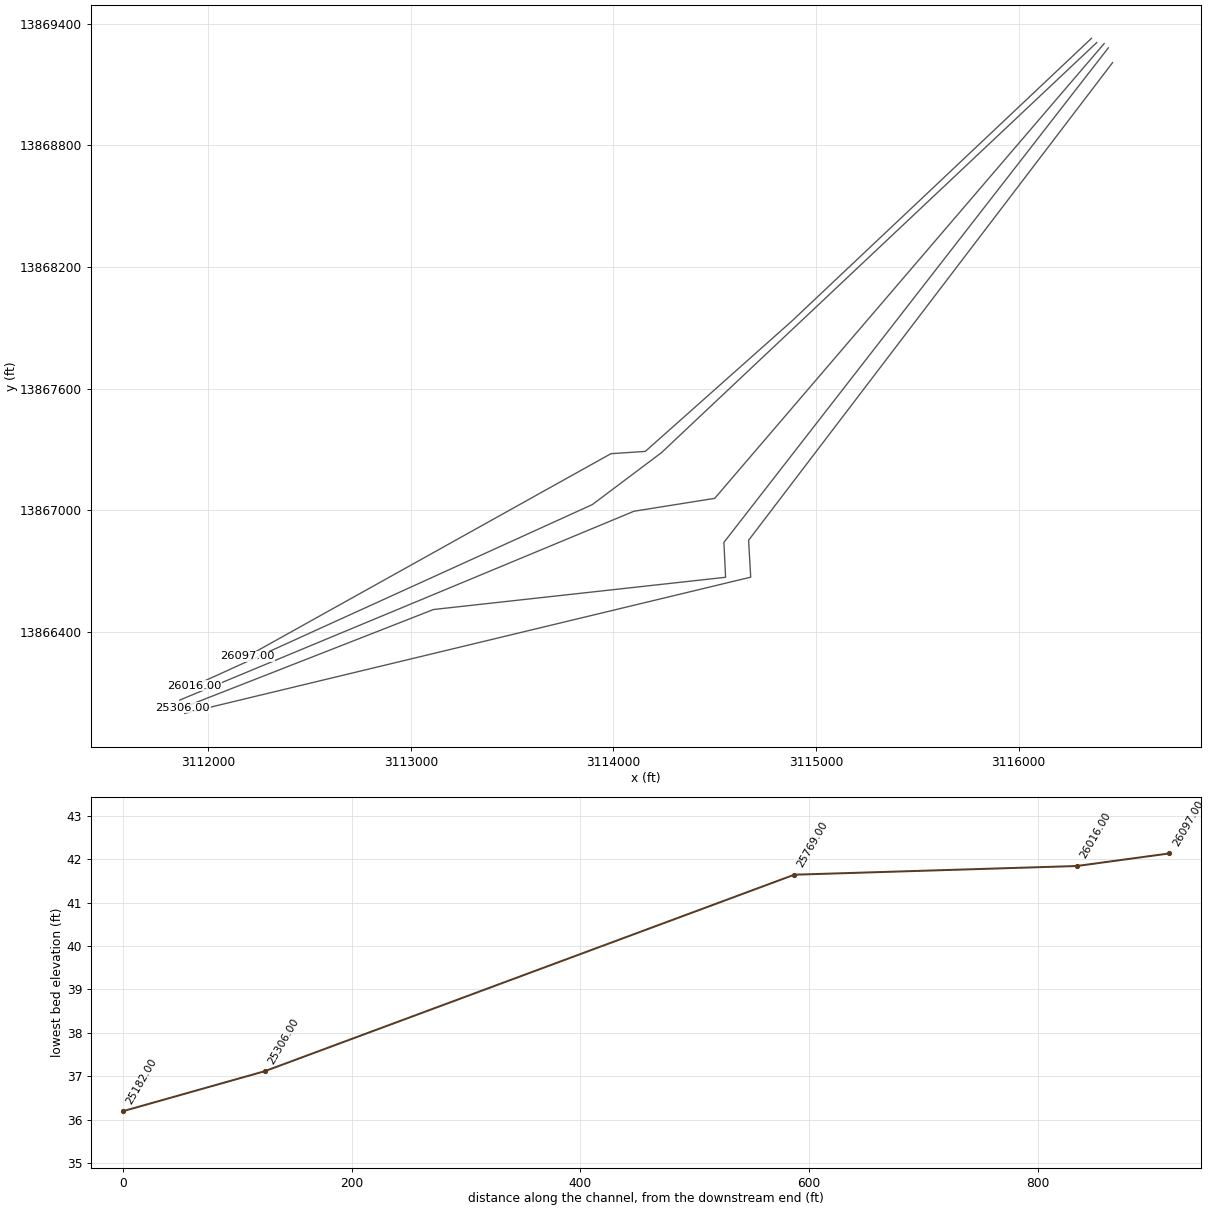
HEC-RAS study E101_00_00.prj: E101-00-00

--- E101_00_00.g01 (geometry) --- (continued)

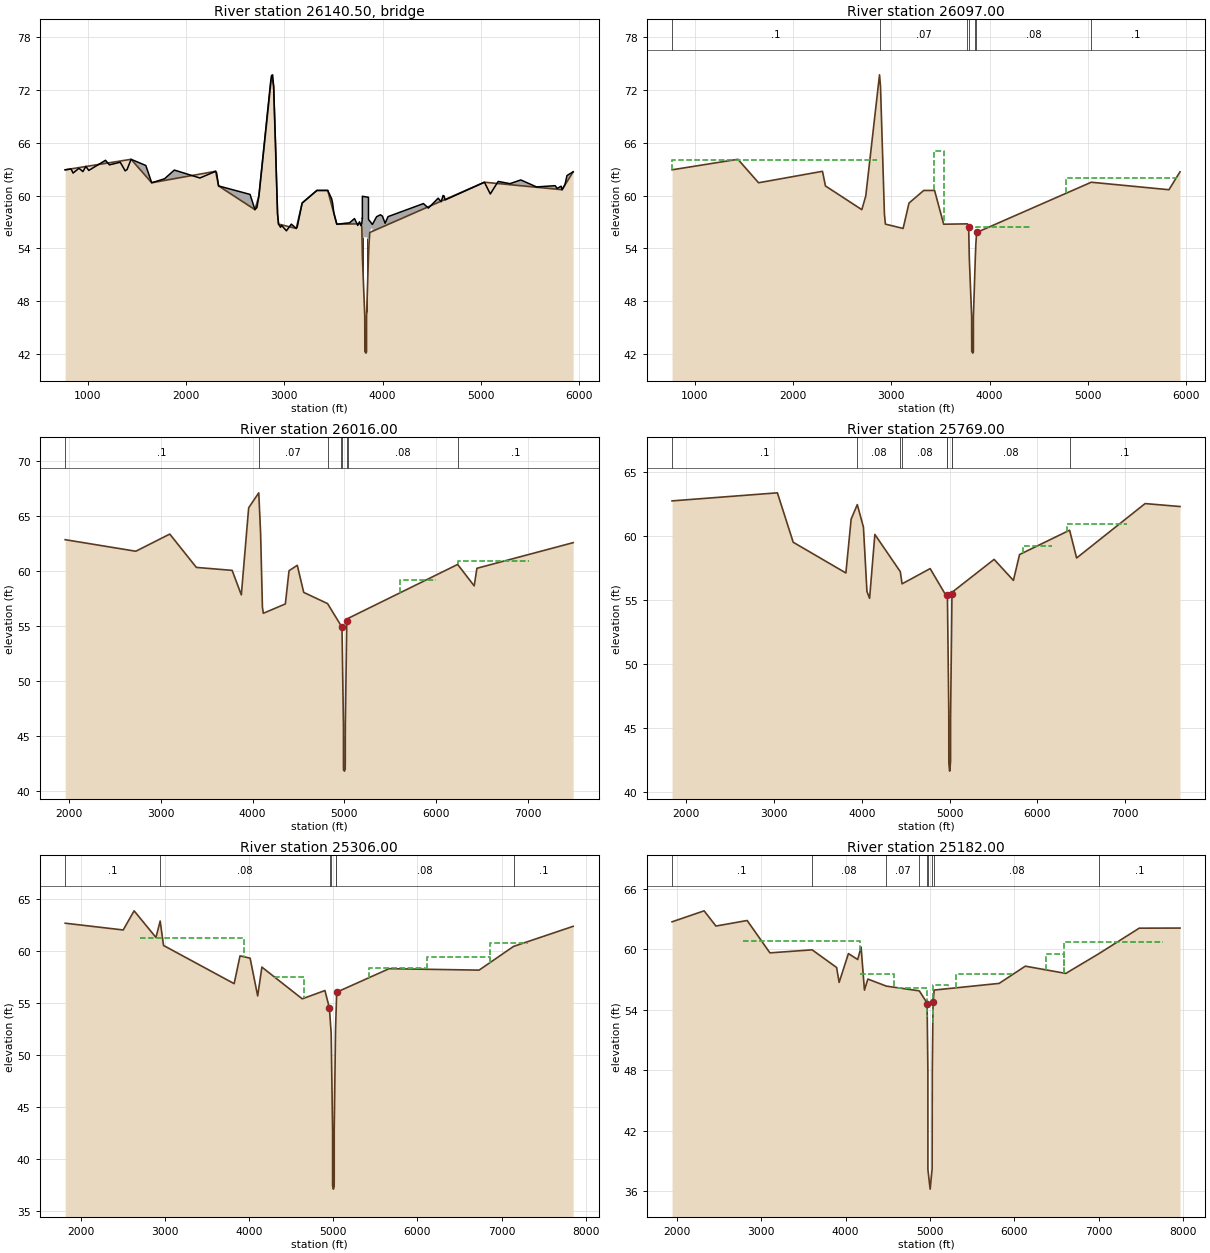
Type RM Length L Ch R = 3 ,26140.50,,,
BEGIN DESCRIPTION:
WHITNEY  (deck skewed 40°, overbanks not skewed)
Structure ID: E101-00-00-19
END DESCRIPTION:
Bridge Culvert--1,0,-1,-1, 0
Deck Dist Width WeirC Skew NumUp NumDn MinLoCord MaxHiCord MaxSubmerge Is_Ogee
10,59,2.6,40, 110, 110, 57.3, , .95, 0, ,,,
  771.06  831.06  851.06  911.06  951.06  981.06 1011.06 1181.06 1221.06 1331.06
 1381.06 1401.06 1441.06 1591.06 1651.06 1781.06 1881.06 2141.06 2301.06 2311.06
 2331.06 2651.06 2701.06 2721.06 2741.06 2861.06 2871.06 2881.06 2891.06 2911.06
 2921.06 2931.06 2941.06 2961.06 2971.06 3021.06 3071.06 3121.06 3131.06 3181.06
 3331.06 3441.06 3481.06 3491.06 3503.56 3533.56 3663.56 3713.56 3741.21 3746.26
 3764.19 3764.57 3774.15  3780.2 3787.55 3793.23  3793.3 3793.38 3793.52 3793.61
 3793.69 3794.22 3817.89 3818.81 3818.89 3825.86 3829.61 3834.67 3835.58 3835.97
 3854.89  3855.5 3855.57 3855.66 3855.74 3856.26 3856.34 3860.94 3861.09 3866.46
 3868.75 3878.56 3895.49 3902.23 3938.08 3976.61 3997.99 4024.63 4054.63 4144.63
 4414.63 4464.63 4564.63 4594.63 4614.63 4624.63 4634.63 5034.63 5094.63 5174.63
 5294.63 5404.63 5564.63 5754.63 5774.63 5814.63 5824.63 5854.63 5874.63 5937.23
   62.92   63.01   62.55   63.09   62.72   63.31   62.85      64   63.48   63.78
    62.8   62.96   64.11   63.41   61.45    61.9   62.89   61.99   62.75   62.58
   61.09   60.13    58.4   58.65   59.94   72.97   73.61   73.69   72.39   65.58
   61.49   57.89   56.76    56.4   56.63      56   56.76   56.27   56.44   59.15
   60.58   60.58   59.64   59.12   58.02   56.75   56.91   57.39   56.75   56.61
   57.02   57.01   56.76   56.61   56.84   57.43   57.44   57.45   57.42   59.92
   59.92   59.92   59.87   59.87   59.87   59.86   59.85   59.84   59.84   59.84
    59.8    59.8    59.8    59.8    57.3   57.29   57.29   57.22   57.22   57.14
   57.11   56.97   56.72   56.86    57.6   57.82   57.66   56.86   57.61   57.98
   59.09   58.58    59.7    59.3   60.01   59.95    59.5   61.51   60.18    61.6
   61.35   61.77   60.98   61.12   60.81   61.06   60.66   61.27   62.27   62.69
                                                                                
                                                                                
                                                                                
                                                                                
                                                                                
              57   56.75    56.6   56.41    53.4   55.34   55.35   55.32   55.32
   55.32   55.32   55.27   55.27   55.27   55.26   55.25   55.24   55.24   55.24
    55.2    55.2    55.2    55.2    55.2   55.19   53.22    54.5   54.51   55.02
   55.77   56.17   56.32
                                                                                
                                                                                
  771.06  831.06  851.06  911.06  951.06  981.06 1011.06 1181.06 1221.06 1331.06
 1381.06 1401.06 1441.06 1591.06 1651.06 1781.06 1881.06 2141.06 2301.06 2311.06
 2331.06 2651.06 2701.06 2721.06 2741.06 2861.06 2871.06 2881.06 2891.06 2911.06
 2921.06 2931.06 2941.06 2961.06 2971.06 3021.06 3071.06 3121.06 3131.06 3181.06
 3331.06 3441.06 3481.06 3491.06 3503.56 3533.56 3663.56 3713.56 3741.21 3746.26
 3764.19 3764.57 3774.15  3780.2 3787.55 3793.23  3793.3 3793.38 3793.52 3793.61
 3793.69 3794.22 3817.89 3818.81 3818.89 3825.86 3829.61 3834.67 3835.58 3835.97
 3854.89  3855.5 3855.57 3855.66 3855.74 3856.26 3856.34 3860.94 3861.09 3866.46
 3868.75 3878.56 3895.49 3902.23 3938.08 3976.61 3997.99 4024.63 4054.63 4144.63
 4414.63 4464.63 4564.63 4594.63 4614.63 4624.63 4634.63 5034.63 5094.63 5174.63
 5294.63 5404.63 5564.63 5754.63 5774.63 5814.63 5824.63 5854.63 5874.63 5937.23
   62.92   63.01   62.55   63.09   62.72   63.31   62.85      64   63.48   63.78
    62.8   62.96   64.11   63.41   61.45    61.9   62.89   61.99   62.75   62.58
   61.09   60.13    58.4   58.65   59.94   72.97   73.61   73.69   72.39   65.58
   61.49   57.89   56.76    56.4   56.63      56   56.76   56.27   56.44   59.15
   60.58   60.58   59.64   59.12   58.02   56.75   56.91   57.39   56.75   56.61
   57.02   57.01   56.76   56.61   56.84   57.43   57.44   57.45   57.42   59.92
   59.92   59.92   59.87   59.87   59.87   59.86   59.85   59.84   59.84   59.84
    59.8    59.8    59.8    59.8    57.3   57.29   57.29   57.22   57.22   57.14
   57.11   56.97   56.72   56.86    57.6   57.82   57.66   56.86   57.61   57.98
   59.09   58.58    59.7    59.3   60.01   59.95    59.5   61.51   60.18    61.6
   61.35   61.77   60.98   61.12   60.81   61.06   60.66   61.27   62.27   62.69
                                                                                
                                                                                
                                                                                
                                                                                
                                                                                
              57   56.75    56.6   56.41    53.4   55.34   55.35   55.32   55.32
   55.32   55.32   55.27   55.27   55.27   55.26   55.25   55.24   55.24   55.24
    55.2    55.2    55.2    55.2    55.2   55.19   53.22    54.5   54.51   55.02
   55.77   56.17   56.32
                                                                                
                                                                                
Pier Skew, UpSta & Num, DnSta & Num=  ,3804.177, 2 ,3804.177, 2 , 0 , 0 , 0 ,,
     1.5     1.5
   48.96    56.3
     1.5     1.5
   48.44   55.78
Pier Skew, UpSta & Num, DnSta & Num=  ,3837.5, 2 ,3837.5, 2 , 0 , 0 , 0 ,,
     1.5     1.5
   45.57   56.24
     1.5     1.5
   45.05   55.72
BR Coef= 1 , 1 , 1 ,.9, 0 ,,,.8,0,1.2,0,
WSPro=,,,, 1 ,,,, 0 ,,,, 0 ,,,,-1 ,-1 ,-1 , 0 , 0 , 0 , 0 , 0
BC Design=,, 0 ,, 0 ,,,,,,
BC HTab HWMax=73.69

Type RM Length L Ch R = 1 ,26097.00,51.4,81,172.4
BEGIN DESCRIPTION:
WHITNEY
Downstream Section of Bridge/Culvert/Weir
END DESCRIPTION:
XS GIS Cut Line= 5
      3116359.31     13869328.32      3114880.14     13867932.49
      3114157.33     13867289.78      3113987.73     13867278.45
      3112193.66     13866278.74
#Sta/Elev= 30
 771.064   62.921441.064   64.111651.064   61.452301.064   62.752331.064   61.09
2701.064    58.42741.064   59.942881.064   73.692891.064   72.392931.064   57.89
2941.064   56.763121.064   56.273181.064   59.153331.064   60.583441.064   60.58
3533.564   56.753774.148   56.793787.553   56.453794.218   52.923817.889   46.35
3818.885   42.34 3829.61   42.133835.584   42.273835.968   46.283855.502   53.03
3861.094   54.553868.754   55.81 5034.63   61.51 5824.63   60.66 5937.23   62.69
#Mann= 7 ,-1 , 0
 771.064      .1       02881.064     .07       03774.148     .04       0
3794.218    .015       03855.502     .04       03861.094     .08       0
 5034.63      .1       0
#XS Ineff= 5 ,-1
  771.06 2851.06   64.06 2868.61 3359.53   60.39    3432  3536.2      65
    3866 4406.62    56.4    4782 5910.17      62
Permanent Ineff=
       F       T       F       F       F
Bank Sta=3787.553,3868.754
XS Rating Curve= 0
Skew Angle= 40
Exp/Cntr=.5,.3

Type RM Length L Ch R = 1 ,26016.00,319.1,247,116.4
BEGIN DESCRIPTION:
Cross Section Xsec 21a
END DESCRIPTION:
XS GIS Cut Line= 4
      3116385.35     13869307.49      3114237.26     13867283.63
      3113895.91     13867027.25       3111930.8     13866133.66
#Sta/Elev= 30
  1956.7   62.88  2726.7   61.83  3096.7   63.39  3386.7   60.36  3776.7   60.09
  3876.7   57.86  3956.7   65.78  4066.7   67.14  4086.7   63.52  4106.7   56.74
  4116.7   56.19  4356.7   57.04  4396.7   60.06  4486.7   60.55  4556.7   58.09
  4816.7   57.07  4966.4   55.03  4973.9   54.94  4990.1   45.91  4990.4   42.16
  4990.8   41.95  5001.2   41.84  5009.4   42.04  5010.3   45.99  5026.3   55.51
  5041.2   55.73  6234.9   60.63  6414.9   58.68  6444.9   60.28  7493.7   62.61
#Mann= 8 ,-1 , 0
  1956.7      .1       0  4066.7     .07       0  4816.7     .08       0
  4966.4     .04       0  4973.9    .015       0  5026.3     .04       0
  5041.2     .08       0  6234.9      .1       0
#XS Ineff= 4 ,-1
 3228.53 4000.79   61.04 6234.83 7007.09    60.9 4033.89 4442.08   59.44
 5605.99 6003.15   59.26
Permanent Ineff=
       F       F       F       F
Bank Sta=4973.9,5026.3
XS Rating Curve= 0
Exp/Cntr=.3,.1

Type RM Length L Ch R = 1 ,25769.00,156.2,463,361.2
BEGIN DESCRIPTION:
Cross Section x21
END DESCRIPTION:
XS GIS Cut Line= 4
      3116421.81     13869302.28      3114499.99     13867058.09
      3114101.37     13866994.41      3111859.61     13866062.47
#Sta/Elev= 30
  1837.6   62.75  3037.6   63.38  3217.6   59.52  3817.6   57.12  3877.6   61.33
  3947.6   62.46  4017.6    60.7  4057.6   55.67  4087.6   55.14  4147.6   60.13
  4437.6   57.22  4457.6   56.27  4777.6   57.46  4965.9   55.27  4974.3   55.36
  4989.8    46.3  4990.2   42.83  4990.7   42.23  4999.8   41.64  5009.9   42.37
  5010.1   45.77    5026   55.45  5028.6   55.62  5505.9   58.18  5725.9   56.54
  5795.9   58.56  6365.9   60.46  6445.9   58.29  7225.9   62.54  7623.6   62.31
#Mann= 9 ,-1 , 0
  1837.6      .1       0  3947.6     .08       0  4437.6     .07       0
  4457.6     .08       0  4965.9     .04       0  4974.3    .015       0
    5026     .04       0  5028.6     .08       0  6365.9      .1       0
#XS Ineff= 6 ,-1
 2853.43 3945.63   61.02 6334.12 7018.12   60.92 3956.66 4171.79   59.39
 5837.67 6168.64   59.24 5589.44 5837.67   57.34 4364.85 4778.57   57.18
Permanent Ineff=
       F       F       F       F       F       F
Bank Sta=4974.3,5026
XS Rating Curve= 0
Exp/Cntr=.3,.1

Type RM Length L Ch R = 1 ,25306.00,87.3,124,102.6
BEGIN DESCRIPTION:
Cross Section Xsec 20c
END DESCRIPTION:
XS GIS Cut Line= 5
      3116442.64     13869281.44      3114545.33      13866840.7
      3114553.59     13866668.58      3113112.14     13866509.49
       3111874.6       13866025.
#Sta/Elev= 30
  1809.3   62.68  2499.3   62.03  2629.3   63.87  2889.3   61.31  2939.3   62.89
  2979.3   60.54  3819.3   56.87  3889.3   59.54  4009.3   59.32  4099.3   55.69
  4149.3   58.46  4629.3   55.41  4899.3   56.21  4952.4   54.54  4963.4   53.28
  4973.8   52.08  4990.2   42.88  4990.3    38.2  4990.8   37.46  4999.7   37.12
  5009.3   37.38  5009.8   38.23  5009.9   42.85  5025.3   52.32  5034.2   54.74
    5039   56.05  5663.1   58.31  6733.3   58.17  7143.3   60.45  7852.3   62.38
#Mann= 7 ,-1 , 0
  1809.3      .1       0  2939.3     .08       0  4963.4     .04       0
  4973.8    .015       0  5025.3     .04       0  5034.2     .08       0
  7143.3      .1       0
#XS Ineff= 6 ,-1
 2704.49 3934.59   61.25 6858.16    7316   60.81 6107.96 6858.16   59.44
 5418.44 6085.89   58.35 4309.69 4651.69   57.54 3978.72 4188.34   57.53
Permanent Ineff=
       F       F       F       F       F       F
Bank Sta=4952.4,5039
XS Rating Curve= 0
Exp/Cntr=.5,.3

Type RM Length L Ch R = 1 ,25182.00,77.8,95,32.1
BEGIN DESCRIPTION:
AIRLINE u/s
Upstream Section of Bridge/Culvert/Weir
END DESCRIPTION:
XS GIS Cut Line= 4
      3116463.47     13869208.53      3114667.17     13866851.33
      3114677.59     13866669.11      3111883.97      13865996.9
#Sta/Elev= 30
    1943   62.72    2323   63.81    2463    62.3    2833   62.85    3103   59.64
    3603   59.94    3893   58.19    3923   56.71    4033   59.57    4143   58.98
    4183   60.22    4223   55.94    4263   57.04    4483   56.34  4872.9   55.87
  4960.8   54.72  4965.5   54.58  4974.8   47.91    4975   38.14  5001.5    36.2
  5025.1   38.22    5027   47.95  5035.8   54.73  5049.3   55.95  5819.1   56.61
  6129.1   58.32  6609.1    57.6  6999.1   59.55  7479.1   62.09  7962.5    62.1
#Mann= 9 ,-1 , 0
    1943      .1       0    3603     .08       0    4483     .07       0
  4872.9     .08       0  4960.8     .04       0  4974.8    .015       0
    5027     .04       0  5049.3     .08       0  6999.1      .1       0
#XS Ineff= 7 ,-1
 2781.72 4171.79   60.81 6593.38 7762.81    60.7 6372.73 6593.38   59.49
 4171.79 4574.47   57.59 5308.12 5981.09   57.53 5033.19 5215.23   56.45
 4614.28 4967.32   56.19
Permanent Ineff=
       F       F       F       F       F       F       F
Bank Sta=4965.5,5035.8
XS Rating Curve= 0
Exp/Cntr=.5,.3

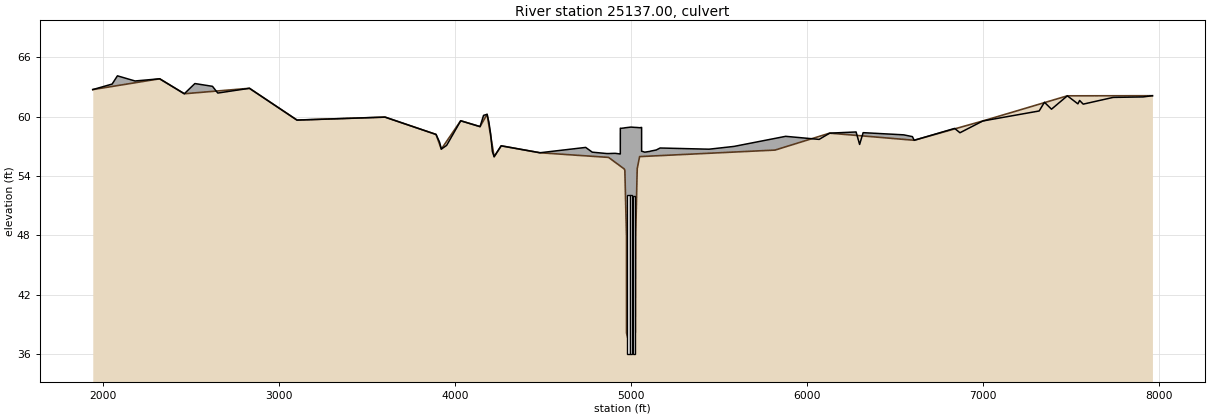
Type RM Length L Ch R = 2 ,25137.00,,,
BEGIN DESCRIPTION:
AIRLINE (field surveyed negative slope)
Structure ID: E101-00-00-18
END DESCRIPTION:
Bridge Culvert--1,0,-1,-1, 0
Deck Dist Width WeirC Skew NumUp NumDn MinLoCord MaxHiCord MaxSubmerge Is_Ogee
10,70,2.6,0, 82, 82, , , .95, 0, ,,,
    1943    2053    2083    2183    2323    2463    2523    2623    2653    2833
    3103    3603    3893    3913    3923    3953    4033    4143    4163    4183
    4193    4203    4213    4223    4263    4483    4743  4780.3  4862.8  4872.9
  4904.7    4912  4937.4 4939.69  4939.8 4939.91    4945  4960.8  4965.5  4974.8
    4975  4999.3  5001.5  5025.1    5027  5035.8  5042.3  5049.3  5050.8  5054.8
 5060.59  5060.7 5060.81  5078.6  5108.1  5112.9  5143.7  5165.7  5443.7  5585.2
  5879.1  6069.1  6129.1  6279.1  6299.1  6319.1  6549.1  6599.1  6609.1  6839.1
  6869.1  6999.1  7319.1  7349.1  7389.1  7479.1  7539.1  7549.1  7569.1  7739.1
  7909.1  7962.5
   62.72   63.28   64.11   63.59   63.81    62.3   63.33   63.05   62.37   62.85
   59.64   59.94   58.19   57.41   56.71   57.08   59.57   58.98   60.12   60.22
   59.45   58.26   56.46   55.94   57.04   56.34   56.88    56.4   56.26   56.26
   56.28   56.28   56.22   56.22   58.82   58.82   58.81   58.84   58.86   58.88
   58.88   58.93   58.93    58.9    58.9   58.89   58.88   58.87   58.87   58.88
    58.9    58.9    56.5    56.4   56.48   56.51   56.62   56.82    56.7   56.98
      58   57.69   58.32   58.44   57.18   58.37   58.15   57.97    57.6    58.8
   58.36   59.55   60.56   61.44   60.74   62.09   61.28   61.62   61.25   61.93
   61.98    62.1
                                                                                
                                                                                
                                                                                
                                                                                
                                                                                
                                                                                
                                                                                
                                                                                
                
    1943    2053    2083    2183    2323    2463    2523    2623    2653    2833
    3103    3603    3893    3913    3923    3953    4033    4143    4163    4183
    4193    4203    4213    4223    4263    4483    4743  4780.3  4862.8  4872.9
  4904.7    4912  4937.4 4939.69  4939.8 4939.91    4945  4960.8  4965.5  4974.8
    4975  4999.3  5001.5  5025.1    5027  5035.8  5042.3  5049.3  5050.8  5054.8
 5060.59  5060.7 5060.81  5078.6  5108.1  5112.9  5143.7  5165.7  5443.7  5585.2
  5879.1  6069.1  6129.1  6279.1  6299.1  6319.1  6549.1  6599.1  6609.1  6839.1
  6869.1  6999.1  7319.1  7349.1  7389.1  7479.1  7539.1  7549.1  7569.1  7739.1
  7909.1  7962.5
   62.72   63.28   64.11   63.59   63.81    62.3   63.33   63.05   62.37   62.85
   59.64   59.94   58.19   57.41   56.71   57.08   59.57   58.98   60.12   60.22
   59.45   58.26   56.46   55.94   57.04   56.34   56.88    56.4   56.26   56.26
   56.28   56.28   56.22   56.22   58.82   58.82   58.81   58.84   58.86   58.88
   58.88   58.93   58.93    58.9    58.9   58.89   58.88   58.87   58.87   58.88
    58.9    58.9    56.5    56.4   56.48   56.51   56.62   56.82    56.7   56.98
      58   57.69   58.32   58.44   57.18   58.37   58.15   57.97    57.6    58.8
   58.36   59.55   60.56   61.44   60.74   62.09   61.28   61.62   61.25   61.93
   61.98    62.1
                                                                                
                                                                                
                                                                                
                                                                                
                                                                                
                                                                                
                                                                                
                                                                                
                
BR Coef= 1 , 1 , 1 ,1.25, 0 ,,,.8,0,2,0,
WSPro=,,,, 1 ,,,, 0 ,,,, 0 ,,,,-1 ,-1 ,-1 , 0 , 0 , 0 , 0 , 0
Culvert=2,16,15,70,.015,.5,1,8,2,36.03,4984.7,36.71,4984.7,Culvert #1  , 0 ,10
Culvert Bottom n=.015
Culvert=2,16,15,70,.015,.5,1,8,2,36.04,5000.7,36.71,5000.7,Culvert #2  , 0 ,10
Culvert Bottom n=.015
Culvert=2,16,15,70,.015,.5,1,8,2,36,5016.6,36.71,5016.6,Culvert #3  , 0 ,10
Culvert Bottom n=.015
BC Design=,, 0 ,, 0 ,,,,,,
BC HTab HWMax=64.11