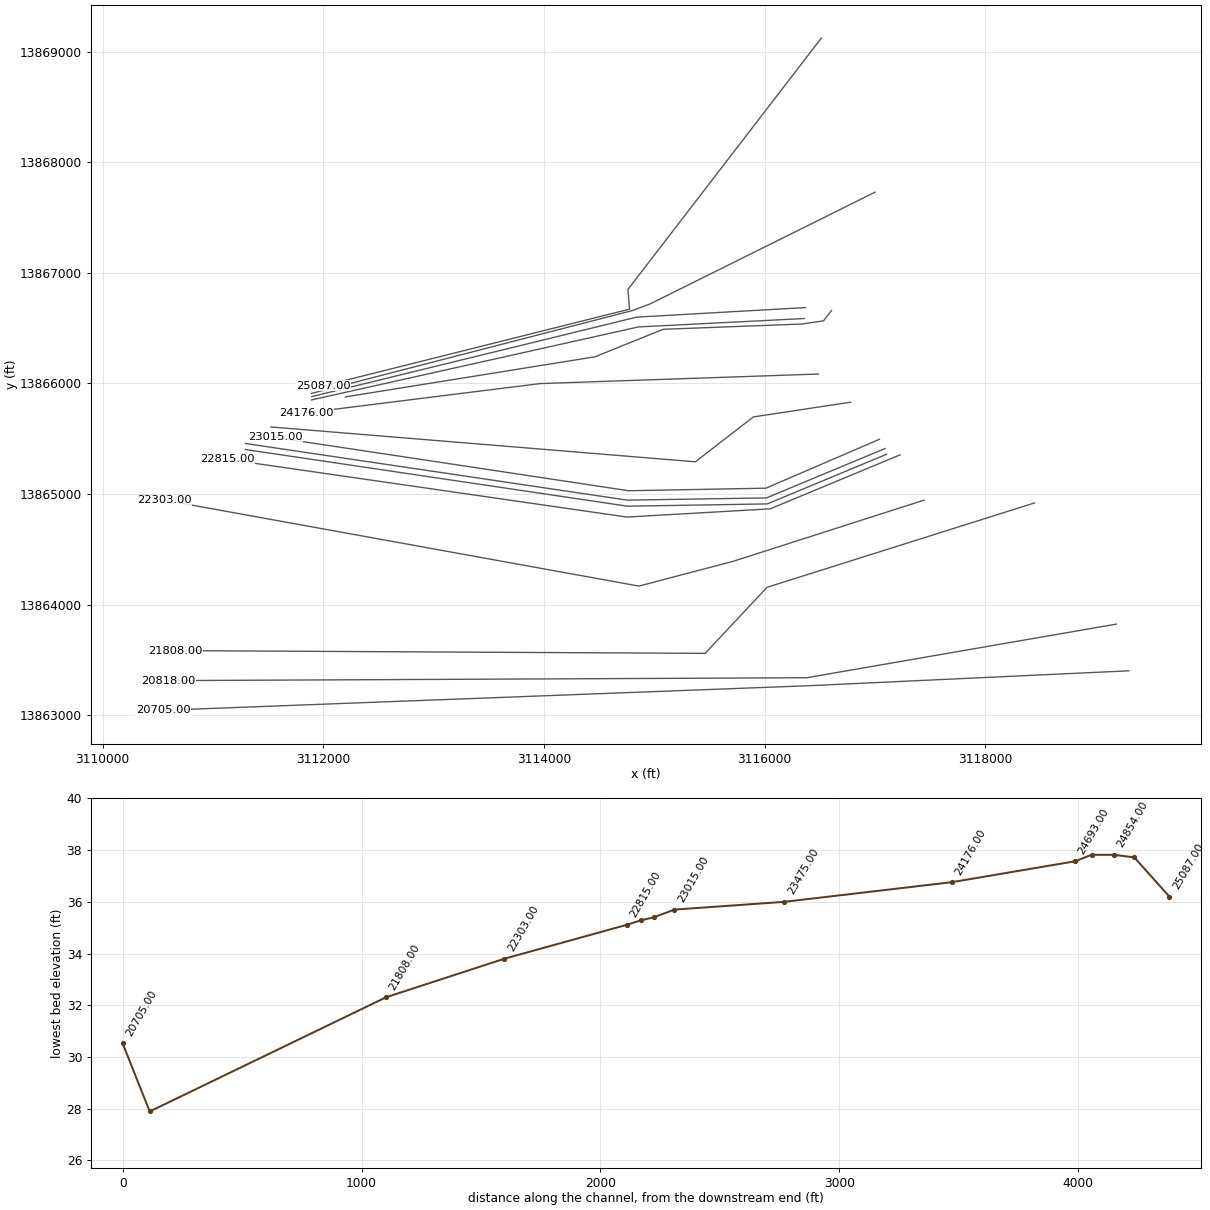
HEC-RAS study E101_00_00.prj: E101-00-00

--- E101_00_00.g01 (geometry) --- (continued)

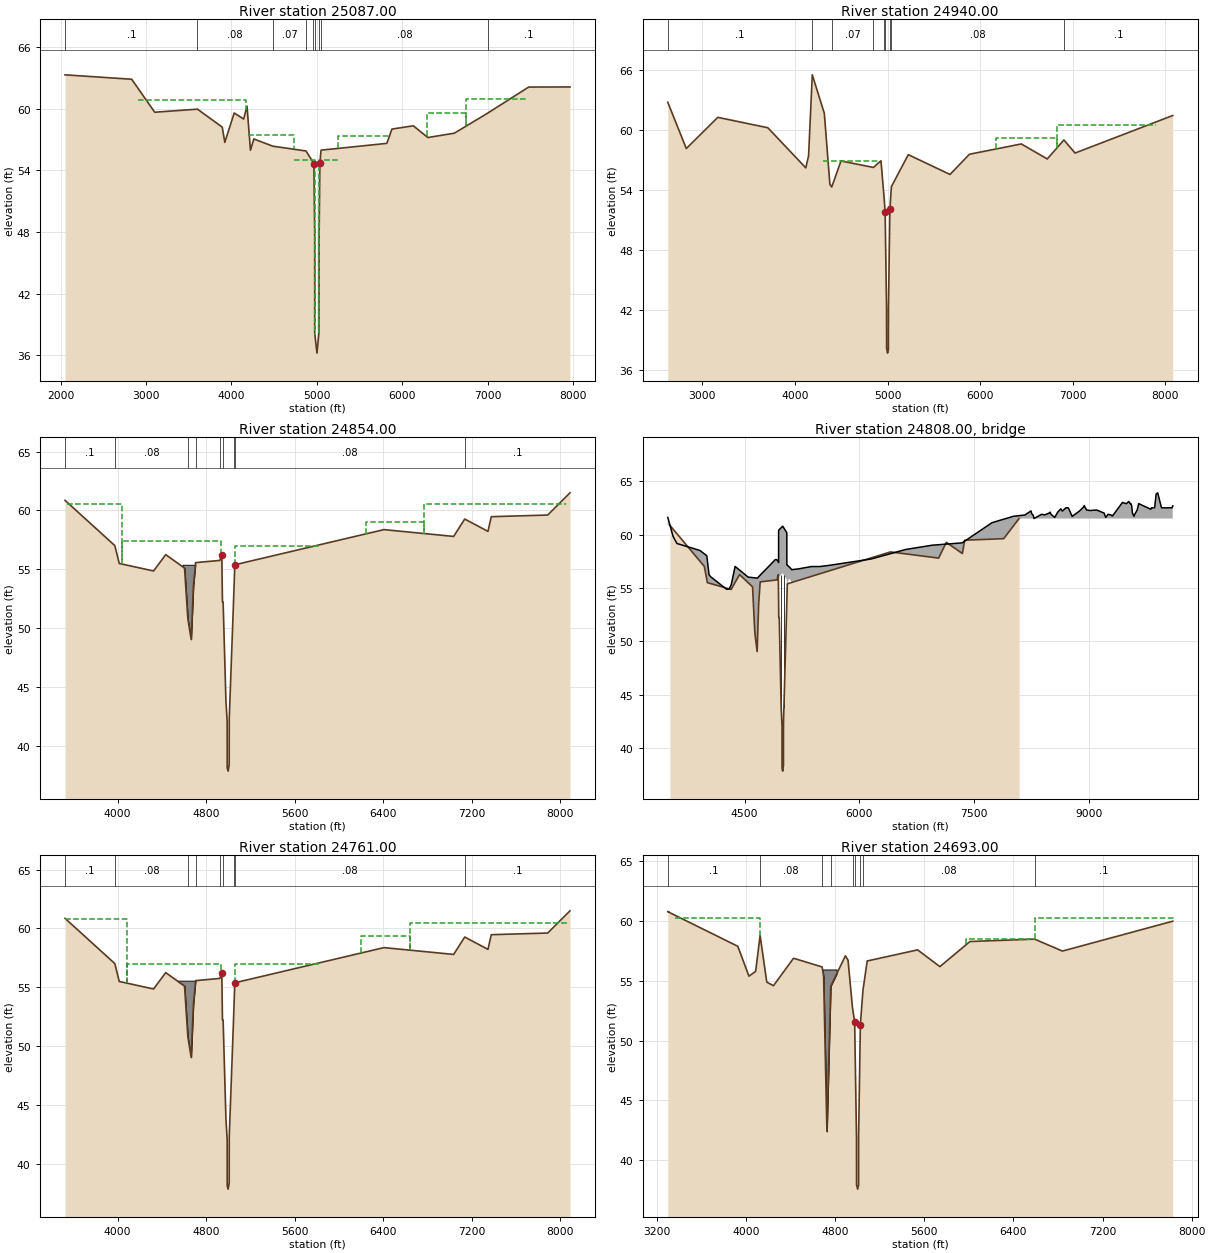
Type RM Length L Ch R = 1 ,25087.00,328.9,147,28.4
BEGIN DESCRIPTION:
AIRLINE
Downstream Section of Bridge/Culvert/Weir
END DESCRIPTION:
XS GIS Cut Line= 4
 3116512.564072113869121.4670009      3114760.55     13866849.12
      3114775.67     13866671.57 3111999.139326513865977.4542112
#Sta/Elev= 30
    2053   63.28    2833   62.85    3103   59.64    3603   59.94    3893   58.19
    3923   56.71    4033   59.57    4143   58.98    4183   60.22    4223   55.94
    4263   57.04    4483   56.34  4872.9   55.87  4960.8   54.72  4965.5   54.58
  4974.8   47.91    4975   38.14  5001.5    36.2  5025.1   38.22    5027   47.95
  5035.8   54.73  5049.3   55.95  5819.1   56.61  5879.1      58  6129.1   58.32
  6299.1   57.18  6609.1    57.6  6999.1   59.55  7479.1   62.09  7962.5    62.1
#Mann= 9 ,-1 , 0
    2053      .1       0    3603     .08       0    4483     .07       0
  4872.9     .08       0  4960.8     .04       0  4974.8    .015       0
    5027     .04       0  5049.3     .08       0  6999.1      .1       0
#XS Ineff= 7 ,-1
 6742.32 7475.18   60.92 2903.07 4170.21   60.81 6283.69 6742.32    59.6
 4189.13 4737.59   57.47  5243.5 5872.34   57.28 4737.59 4977.21      55
 5024.08  5243.5      55
Permanent Ineff=
       F       F       F       F       F       F       F
Bank Sta=4965.5,5035.8
XS Rating Curve= 0
Exp/Cntr=.5,.3

Type RM Length L Ch R = 1 ,24940.00,216.5,86,75.9
BEGIN DESCRIPTION:
Cross Section Xsec 20b
END DESCRIPTION:
XS GIS Cut Line= 4
      3116999.85     13867728.97       3114961.1     13866718.49
      3114800.74     13866658.63      3111891.46     13865908.86
#Sta/Elev= 30
  2627.3    62.8  2827.3   58.17  3167.3   61.29  3707.3   60.25  4117.3   56.24
  4147.3   57.43  4187.3   65.54  4317.3   61.69  4377.3    54.6  4397.3   54.33
  4497.3   56.93  4847.3   56.28  4928.9   56.95  4961.9   53.34  4973.7   51.86
  4989.1   42.22  4989.7   38.22  4999.8   37.72  5008.9   38.07  5009.4   42.06
  5025.1   52.09  5041.3   54.36  5223.9   57.56  5673.9   55.58  5883.9    57.6
  6443.9   58.63  6723.9   57.13  6903.9   59.03  7023.9   57.72  8078.2   61.47
#Mann= 9 ,-1 , 0
  2627.3      .1       0  4187.3     .08       0  4397.3     .07       0
  4847.3     .08       0  4961.9     .04       0  4973.7    .015       0
  5025.1     .04       0  5041.3     .08       0  6903.9      .1       0
#XS Ineff= 5 ,-1
 2639.87 4223.01   61.64 6832.15 7896.77   60.48 6175.73 6832.15   59.19
 5221.43 5855.79   57.11 4305.75  4901.5   56.97
Permanent Ineff=
       F       F       F       F       F
Bank Sta=4973.7,5025.1
XS Rating Curve= 0
Exp/Cntr=.5,.3

Type RM Length L Ch R = 1 ,24854.00,106.6,93,106.1
BEGIN DESCRIPTION:
CROSSTIMBERS u/s
Upstream Section of Bridge/Culvert/Weir
END DESCRIPTION:
XS GIS Cut Line= 3
      3116369.87      13866685.8      3114840.01     13866599.35
      3111895.21     13865880.76
#Sta/Elev= 30
  3524.8   60.86  3974.8   57.01  4014.8   55.49  4324.8   54.85  4434.8   56.24
  4604.8    55.1  4634.8   50.78  4664.8   49.03  4684.8   53.51  4704.8   55.56
  4924.8   55.75  4941.6   56.25  4947.5   52.22  4953.6    52.2    4979   43.78
  4990.2      42  4990.8   38.08  4998.9   37.82  5008.5   38.36  5008.9   42.29
  5047.6   52.25  5059.1   55.35  5060.4   55.38  6407.1   58.37  7037.1   57.79
  7137.1   59.27  7347.1   58.22  7377.1   59.47  7887.1   59.61  8088.3    61.5
#Mann= 9 ,-1 , 0
  3524.8      .1       0  3974.8     .08       0  4634.8     .04       0
  4704.8     .08       0  4924.8     .04       0  4953.6    .015       0
  5047.6     .04       0  5060.4     .08       0  7137.1      .1       0
#XS Ineff= 5 ,-1
 3543.74 4035.46   60.59 6773.05 8054.37   60.59 6248.23 6773.05   58.98
 4035.46    4935   57.39    5063 5836.88      57
Permanent Ineff=
       F       F       F       F       F
#Block Obstruct= 1 ,-1
 4587.77  4760.7   55.38
Bank Sta=4941.6,5059.1
XS Rating Curve= 0
Exp/Cntr=.5,.3

Type RM Length L Ch R = 3 ,24808.00,,,
BEGIN DESCRIPTION:
CROSSTIMBERS
Structure ID: E101-00-00-17
END DESCRIPTION:
Bridge Culvert--1,0,-1,-1, 0
Deck Dist Width WeirC Skew NumUp NumDn MinLoCord MaxHiCord MaxSubmerge Is_Ogee
10,72,2.6,0, 126, 126, , , .95, 0, ,,,
  3496.8  3499.8  3566.8  3616.8  3916.8  4006.8  4036.8  4059.8  4266.8  4299.8
  4326.8  4376.8  4546.8  4666.8  4717.8  4903.6  4924.9  4941.6  4944.9 4945.01
 4945.09  4945.2  4945.3 4945.41  4947.5  4998.9    5006  5008.5  5008.6  5008.9
  5014.7  5043.2  5047.6  5050.2 5052.69  5052.8 5052.89    5053  5053.1 5053.21
  5059.1  5060.4    5080  5089.5    5116  5117.8  5195.1  5205.1  5375.1  5485.1
  5605.6  5606.4  6156.4  6605.6  6953.2  7343.9  7733.9  8013.9  8163.2  8243.2
  8243.9  8253.2  8273.2  8273.9  8283.2  8383.2  8423.2  8483.9  8493.2  8503.9
  8553.2  8593.2  8633.9  8651.9  8659.6  8699.6  8731.9  8739.6  8759.6  8781.9
  8789.6  8859.6  8879.6  8931.9  8939.6  8969.6  9011.9  9101.9  9199.6  9219.6
  9221.9  9251.9  9299.6  9301.9  9309.6  9439.6  9489.6  9521.9  9541.9  9549.6
  9551.9  9559.6  9561.9  9569.6  9571.9  9589.6  9591.9  9609.6  9619.6  9631.9
  9651.9  9659.6  9809.6  9819.6  9831.9  9841.9  9859.6  9879.6  9881.9  9899.6
  9949.6 10001.9 10041.9 10089.6 10095.6   10096
    61.6   61.53   59.81   59.16   58.51   58.01   56.21   56.03   54.86    54.9
   55.31   57.01   56.01   55.91   56.29   57.66   57.62   57.47   57.37   57.37
   57.37   60.37   60.37   60.37   60.42   60.78    60.7   60.67   60.67   60.67
    60.6   60.28   60.22   60.19   60.15   60.15   60.15   60.15   57.15   57.15
   57.12   57.11   56.99   56.94    56.7   56.71   56.77   56.78      57      57
   57.11   57.11   57.71    58.6      59   59.22   61.11   61.71   61.83   62.21
   62.21   61.96    61.8   61.78    61.5    61.9   61.84   62.02    62.1   61.92
    61.6    62.1   62.41    62.2   62.23   62.51    62.5   62.38   62.06    61.7
   61.74   62.11   62.22   62.59   62.71   62.31   62.25    62.3   62.01   61.61
   61.62    61.9   61.81   61.74   61.75   63.01   62.89    63.1   62.88   62.91
   62.86   62.71   62.55   62.01   61.98   61.71    61.8   62.02   62.15    62.3
    62.9   62.87   62.37   62.51   62.51    62.5   62.51   63.81   63.82   63.91
   62.51    62.5   62.51   62.51    62.7    62.7
                                                                                
                                                           56.26   54.01   53.93
   53.88    53.8   55.97   55.97   56.02   56.38    56.3   56.27   56.27   56.27
    56.2   55.88   55.82   55.79   55.75   53.15   53.18   53.22   53.26    53.3
   55.36   55.39   55.82   55.85    55.5    55.5
                                                                                
                                                                                
                                                                                
                                                                                
                                                                                
                                                                                
                                                                                
                                                
  3496.8  3499.8  3566.8  3616.8  3916.8  4006.8  4036.8  4059.8  4266.8  4299.8
  4326.8  4376.8  4546.8  4666.8  4717.8  4903.6  4924.9  4941.6  4944.9 4945.01
 4945.09  4945.2  4945.3 4945.41  4947.5  4998.9    5006  5008.5  5008.6  5008.9
  5014.7  5043.2  5047.6  5050.2 5052.69  5052.8 5052.89    5053  5053.1 5053.21
  5059.1  5060.4    5080  5089.5    5116  5117.8  5195.1  5205.1  5375.1  5485.1
  5605.6  5606.4  6156.4  6605.6  6953.2  7343.9  7733.9  8013.9  8163.2  8243.2
  8243.9  8253.2  8273.2  8273.9  8283.2  8383.2  8423.2  8483.9  8493.2  8503.9
  8553.2  8593.2  8633.9  8651.9  8659.6  8699.6  8731.9  8739.6  8759.6  8781.9
  8789.6  8859.6  8879.6  8931.9  8939.6  8969.6  9011.9  9101.9  9199.6  9219.6
  9221.9  9251.9  9299.6  9301.9  9309.6  9439.6  9489.6  9521.9  9541.9  9549.6
  9551.9  9559.6  9561.9  9569.6  9571.9  9589.6  9591.9  9609.6  9619.6  9631.9
  9651.9  9659.6  9809.6  9819.6  9831.9  9841.9  9859.6  9879.6  9881.9  9899.6
  9949.6 10001.9 10041.9 10089.6 10095.6   10096
    61.6   61.53   59.81   59.16   58.51   58.01   56.21   56.03   54.86    54.9
   55.31   57.01   56.01   55.91   56.29   57.66   57.62   57.47   57.37   57.37
   57.37   60.37   60.37   60.37   60.42   60.78    60.7   60.67   60.67   60.67
    60.6   60.28   60.22   60.19   60.15   60.15   60.15   60.15   57.15   57.15
   57.12   57.11   56.99   56.94    56.7   56.71   56.77   56.78      57      57
   57.11   57.11   57.71    58.6      59   59.22   61.11   61.71   61.83   62.21
   62.21   61.96    61.8   61.78    61.5    61.9   61.84   62.02    62.1   61.92
    61.6    62.1   62.41    62.2   62.23   62.51    62.5   62.38   62.06    61.7
   61.74   62.11   62.22   62.59   62.71   62.31   62.25    62.3   62.01   61.61
   61.62    61.9   61.81   61.74   61.75   63.01   62.89    63.1   62.88   62.91
   62.86   62.71   62.55   62.01   61.98   61.71    61.8   62.02   62.15    62.3
    62.9   62.87   62.37   62.51   62.51    62.5   62.51   63.81   63.82   63.91
   62.51    62.5   62.51   62.51    62.7    62.7
                                                                                
                                                           56.26   54.01   53.93
   53.88    53.8   55.97   55.97   56.02   56.38    56.3   56.27   56.27   56.27
    56.2   55.88   55.82   55.79   55.75   53.15   53.18   53.22   53.26    53.3
   55.36   55.39   55.82   55.85    55.5    55.5
                                                                                
                                                                                
                                                                                
                                                                                
                                                                                
                                                                                
                                                                                
                                                
Pier Skew, UpSta & Num, DnSta & Num=  ,4979, 2 ,4979, 2 , 0 , 0 , 0 ,,
     1.5     1.5
   42.67   57.52
     1.5     1.5
   42.67   57.52
Pier Skew, UpSta & Num, DnSta & Num=  ,5014.7, 2 ,5014.7, 2 , 0 , 0 , 0 ,,
     1.5     1.5
   42.89   57.21
     1.5     1.5
   42.89   57.21
BR Coef= 1 , 1 , 1 ,.9, 0 ,,,.8,0,1.2,0,
WSPro=,,,, 1 ,,,, 0 ,,,, 0 ,,,,-1 ,-1 ,-1 , 0 , 0 , 0 , 0 , 0
BC Design=,, 0 ,, 0 ,,,,,,
BC HTab HWMax=61.5

Type RM Length L Ch R = 1 ,24761.00,41.7,68,224.4
BEGIN DESCRIPTION:
CROSSTIMBERS
Downstream Section of Bridge/Culvert/Weir
END DESCRIPTION:
XS GIS Cut Line= 3
      3116362.06     13866586.84      3114855.64     13866510.66
      3111893.33     13865850.78
#Sta/Elev= 30
  3524.8   60.86  3974.8   57.01  4014.8   55.49  4324.8   54.85  4434.8   56.24
  4604.8    55.1  4634.8   50.78  4664.8   49.03  4684.8   53.51  4704.8   55.56
  4924.8   55.75  4941.6   56.25  4947.5   52.22  4953.6    52.2    4979   43.78
  4990.2      42  4990.8   38.08  4998.9   37.82  5008.5   38.36  5008.9   42.29
  5047.6   52.25  5059.1   55.35  5060.4   55.38  6407.1   58.37  7037.1   57.79
  7137.1   59.27  7347.1   58.22  7377.1   59.47  7887.1   59.61  8088.3    61.5
#Mann= 9 ,-1 , 0
  3524.8      .1       0  3974.8     .08       0  4634.8     .04       0
  4704.8     .08       0  4924.8     .04       0  4953.6    .015       0
  5047.6     .04       0  5060.4     .08       0  7137.1      .1       0
#XS Ineff= 5 ,-1
  3524.8 4082.74   60.81 6640.66 8078.01   60.48 6200.95 6640.66   59.32
    5063 5832.15      57 4082.74    4935      57
Permanent Ineff=
       F       F       F       F       F
#Block Obstruct= 1 ,-1
  4434.8  4704.8   55.56
Bank Sta=4941.6,5059.1
XS Rating Curve= 0
Exp/Cntr=.5,.3

Type RM Length L Ch R = 1 ,24693.00,507.3,517,420.7
BEGIN DESCRIPTION:
Cross Section Xsec 20a
END DESCRIPTION:
XS GIS Cut Line= 6
 3116605.161525513866659.5010161      3116533.28     13866565.74
      3116334.72     13866536.85      3115080.18     13866489.49
       3114461.7      13866240.5 3112200.570945813865878.1161596
#Sta/Elev= 30
  3297.1    60.8  3925.9    57.9  4025.9    55.4  4085.9    55.8  4125.9    58.8
  4185.9    54.9  4245.9    54.6  4425.9    56.9    4683   56.17  4695.9    55.4
  4725.9    42.4  4760.2   54.56  4891.3    57.1  4915.3   56.74  4955.4   52.75
  4974.7   51.56  4991.5    41.8  4991.7   37.94  5001.6   37.57    5010   37.92
  5010.1   41.95  5026.1   51.35  5049.3   54.22  5087.3   56.67  5539.9    57.6
  5739.9    56.2  6009.9    58.3  6589.9    58.5  6839.9    57.5  7829.9      60
#Mann= 9 ,-1 , 0
  3297.1      .1       0  4125.9     .08       0    4683     .04       0
  4760.2     .08       0  4955.4     .04       0  4974.7    .015       0
  5026.1     .04       0  5049.3     .08       0  6589.9      .1       0
#XS Ineff= 4 ,-1
 3362.49 4122.93   60.26 6597.32  7829.9   60.26 5978.72 6597.32   58.54
 4146.57  4434.2   55.99
Permanent Ineff=
       F       F       F       F
#Block Obstruct= 2 ,-1
  3297.1 3303.46   60.87  4655.9  4813.1   55.96
Bank Sta=4974.7,5026.1
XS Rating Curve= 0
Exp/Cntr=.3,.1

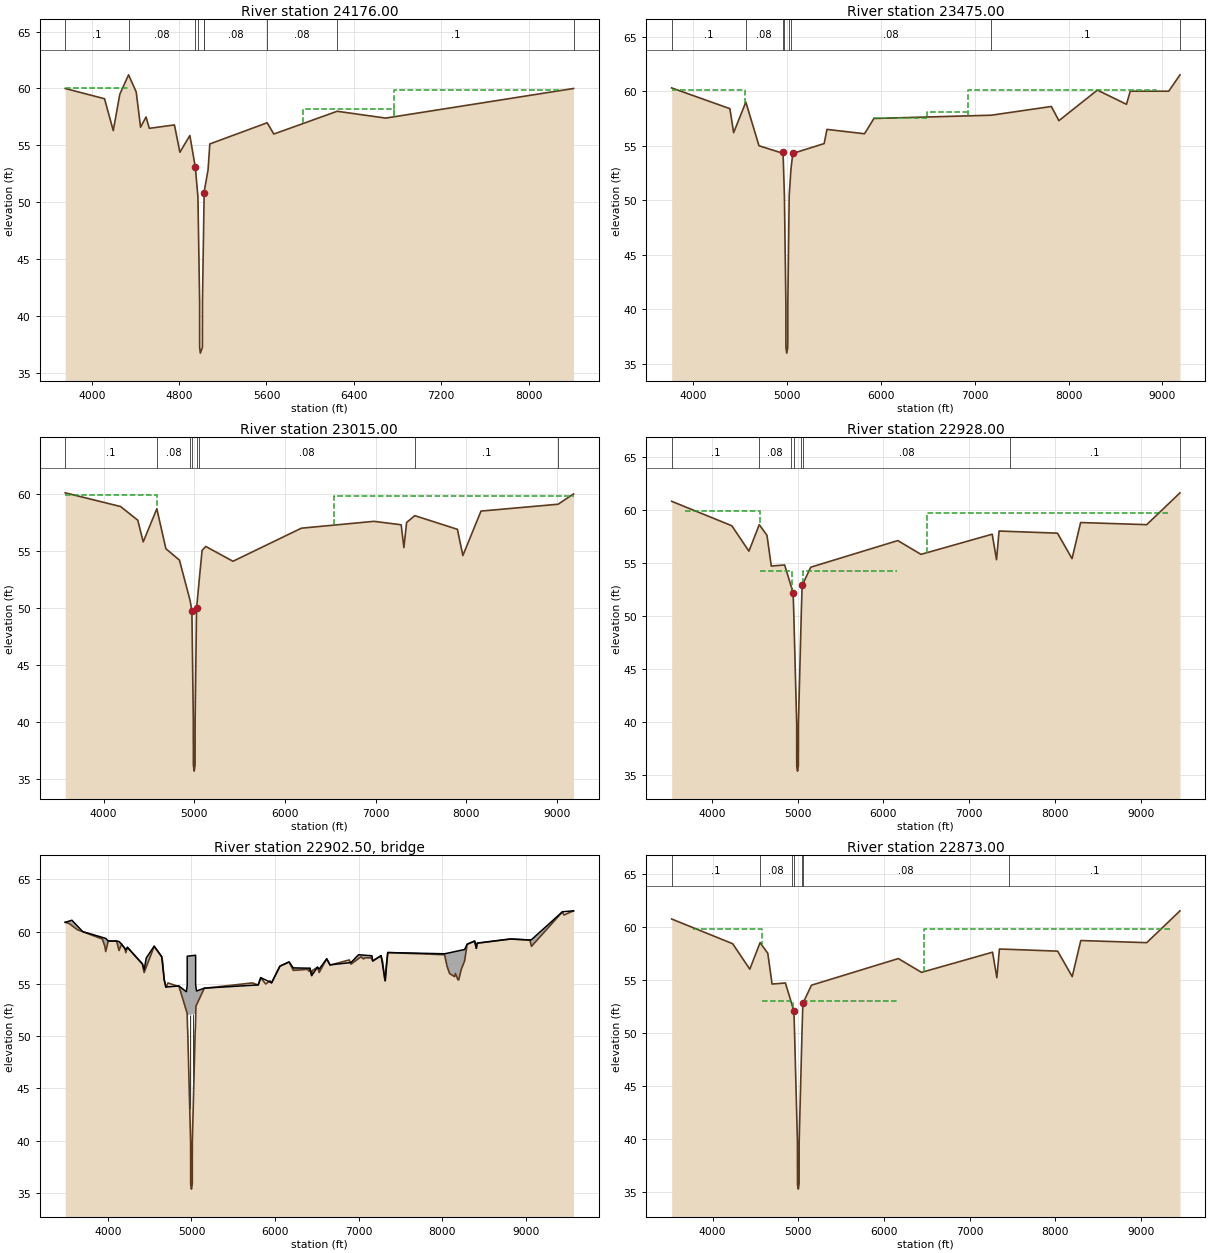
Type RM Length L Ch R = 1 ,24176.00,500.2,701,756.1
BEGIN DESCRIPTION:
Cross Section x20
END DESCRIPTION:
XS GIS Cut Line= 3
      3116485.71      13866084.8      3113963.53     13865998.42
 3111849.793653613865735.1130325
#Sta/Elev= 30
  3757.3      60  4117.3    59.1  4197.3    56.3  4257.3    59.5  4337.3    61.2
  4407.3    59.7  4447.3    56.6  4497.3    57.5  4527.3    56.5  4757.3    56.8
  4807.3    54.4  4898.4   55.87  4946.4    53.2  4948.4    53.1  4972.4   50.47
    4988   41.25  4988.1    37.8  4988.4   37.24  4994.6   36.76  5013.3   37.27
  5013.9   41.26  5029.4   50.86  5032.3   51.09  5065.2   52.86  5081.1   55.13
  5606.3   56.99  5667.3      56  6247.3      58    6691    57.4    8411      60
#Mann= 9 ,-1 , 0
  3757.3      .1       0  4337.3     .08       0  4946.4     .04       0
  4972.4    .015       0  5029.4     .04       0  5032.3     .08       0
  5606.3     .08       0  6247.3      .1       0    8411      .1       0
#XS Ineff= 3 ,-1
 3761.23 4342.79   60.04 6763.59 8304.96    59.9 5936.17 6763.59    58.2
Permanent Ineff=
       F       F       F
Bank Sta=4948.4,5029.4
XS Rating Curve= 0
Exp/Cntr=.3,.1

Type RM Length L Ch R = 1 ,23475.00,560.6,460,281.1
BEGIN DESCRIPTION:
Cross Section x19
END DESCRIPTION:
XS GIS Cut Line= 4
      3116777.68     13865829.81      3115897.57     13865697.14
       3115371.9     13865291.37 3111524.816120513865606.3837324
#Sta/Elev= 30
  3773.4    60.3  4393.4    58.4  4433.4    56.2  4563.4      59  4703.5      55
  4954.8   54.32  4959.7    54.4  4974.3    50.4  4989.9    40.5  4990.1   37.06
  4990.5   36.51  4999.1      36  5009.3   36.52  5010.1   37.07  5010.5   40.51
  5025.3   50.45  5043.8   52.86  5063.5    54.3  5397.5    55.2  5427.5    56.5
  5827.5    56.1  5927.5    57.5  7177.5    57.8  7817.5    58.6  7897.5    57.3
  8307.5    60.1  8617.5    58.8  8657.5      60  9067.5      60  9187.5    61.5
#Mann= 8 ,-1 , 0
  3773.4      .1       0  4563.4     .08       0  4954.8     .04       0
  4974.3    .015       0  5025.3     .04       0  5043.8     .08       0
  7177.5      .1       0  9187.5      .1       0
#XS Ineff= 4 ,-1
 6933.02 8935.38    60.1  3773.4 4555.56    60.1 6491.73 6933.02   58.12
 5923.56 6491.64    57.5
Permanent Ineff=
       F       F       F       F
Bank Sta=4959.7,5063.5
XS Rating Curve= 0
Exp/Cntr=.3,.1

Type RM Length L Ch R = 1 ,23015.00,86.8,87,89.5
BEGIN DESCRIPTION:
Cross Section Xsec 18b
END DESCRIPTION:
XS GIS Cut Line= 4
      3117039.71     13865494.76      3116011.35     13865052.71
      3114767.39     13865029.67      3111563.45      13865511.7
#Sta/Elev= 30
  3577.8    60.1  4187.8    58.9  4377.8    57.7  4437.8    55.8  4587.8    58.7
  4687.8    55.2  4837.1    54.2  4954.9   50.65  4974.3   49.72    4990   40.22
  4990.7   36.23  4999.7    35.7  5009.3   36.22    5010   40.22  5025.7   49.96
  5056.7   52.58  5086.6   55.05  5127.1    55.4  5427.1    54.1  6181.3      57
  6981.3    57.6  7281.3    57.3  7311.3    55.3  7341.3    57.5  7431.3    58.1
  7901.3    56.9  7961.3    54.6  8161.3    58.5  9011.3    59.1  9181.3      60
#Mann= 8 ,-1 , 0
  3577.8      .1       0  4587.8     .08       0  4954.9     .04       0
  4974.3    .015       0  5025.7     .04       0  5056.7     .08       0
  7431.3      .1       0  9011.3      .1       0
#XS Ineff= 2 , 0
         4588.65   59.93 6541.37           59.81
Permanent Ineff=
       F       F
Bank Sta=4974.3,5025.7
XS Rating Curve= 0
Exp/Cntr=.5,.3

Type RM Length L Ch R = 1 ,22928.00,54.8,55,57.7
BEGIN DESCRIPTION:
RIGGS u/s
Upstream Section of Bridge/Culvert/Weir
END DESCRIPTION:
XS GIS Cut Line= 4
      3117091.98      13865411.9      3116016.37     13864964.91
      3114757.06     13864944.43      3111296.54      13865456.6
#Sta/Elev= 30
  3533.3   60.83  4233.7   58.53  4433.7   56.13  4553.7   58.63  4643.7   57.63
  4693.7   54.73  4849.3   54.83  4926.9   52.78  4948.2   52.22    4955   50.57
  4989.9   39.86  4990.5   35.83  4999.8    35.4  5009.5    35.9  5010.1    39.9
  5044.5    50.6  5053.3    52.9  5057.9   52.98  5153.4   54.62    6168   57.13
    6438   55.83    7268   57.73    7318   55.33    7348   58.03  7478.8   57.99
    8028   57.83    8198   55.43    8298   58.83    9068   58.63  9455.8   61.63
#Mann= 8 ,-1 , 0
  3533.3      .1       0  4553.7     .08       0  4926.9     .04       0
    4955    .015       0  5044.5     .04       0  5057.9     .08       0
  7478.8      .1       0  9455.8      .1       0
#XS Ineff= 4 ,-1
    3684 4561.07   59.93 6513.79    9316   59.69    5059 6155.24    54.3
 4561.07    4939    54.3
Permanent Ineff=
       F       F       F       F
Bank Sta=4948.2,5053.3
XS Rating Curve= 0
Exp/Cntr=.5,.3

Type RM Length L Ch R = 3 ,22902.50,,,
BEGIN DESCRIPTION:
RIGGS
Structure ID: E101-00-00-16
END DESCRIPTION:
Bridge Culvert--1,0,-1,-1, 0
Deck Dist Width WeirC Skew NumUp NumDn MinLoCord MaxHiCord MaxSubmerge Is_Ogee
10,31,2.6,0, 60, 60, , , .95, 0, ,,,
  3489.2  3569.2  3699.2  3933.7  3973.7  4003.7  4103.7  4133.7  4163.7  4213.7
  4233.7  4413.7  4433.7  4459.2  4553.7  4643.7  4673.7  4693.7  4849.3  4938.9
 4948.69  4948.8  5049.5 5049.61  5049.8  5053.3  5060.1  5153.4  5798.5  5828.5
    5958    6058    6168    6218    6418    6438    6508    6528    6618    6658
    6908  6998.8  7158.8  7168.8    7268    7318    7348    8028    8088    8198
    8268    8298    8388    8408    8418    8818    9048    9068    9438    9571
    60.9    61.1   60.01   59.46   59.36   59.12   59.11   59.06   58.81   58.26
   58.51   56.91   56.36    57.5   58.62   57.61   55.41   54.71   54.81   54.26
   54.86   57.66   57.75   54.95   54.95   54.74   54.33    54.6   54.91   55.61
   55.11   56.71   57.11   56.54   56.51   55.81   56.61   56.43   57.41   56.83
   57.05    57.8    57.7    57.2   57.71   55.31   58.01   57.89   57.99   58.18
    58.3   58.81   59.11   58.41   58.91   59.31   59.21   59.24   61.91      62
    60.9   60.59      60    59.3    58.1    59.1    59.1    58.2    58.8      58
    58.5    56.9    56.1   56.62    58.6    57.6    55.4    54.7    54.8   52.44
   52.03      52   52.15   52.15   51.73   52.87   52.99   54.59    54.9    55.6
    55.1    56.7    57.1    56.3    56.5    55.8    56.6    56.1    57.4    56.8
    56.9   57.43   57.34    57.2    57.7    55.3      58    57.8      56    55.4
    57.2    58.8    59.1    58.4    58.9    59.3    59.2    58.6    61.9      62
  3489.2  3569.2  3699.2  3933.7  3973.7  4003.7  4103.7  4133.7  4163.7  4213.7
  4233.7  4413.7  4433.7  4459.2  4553.7  4643.7  4673.7  4693.7  4849.3  4938.9
 4948.69  4948.8  5049.5 5049.61  5049.8  5053.3  5060.1  5153.4  5798.5  5828.5
    5958    6058    6168    6218    6418    6438    6508    6528    6618    6658
    6908  6998.8  7158.8  7168.8    7268    7318    7348    8028    8088    8198
    8268    8298    8388    8408    8418    8818    9048    9068    9438    9571
    60.9    61.1   60.01   59.46   59.36   59.12   59.11   59.06   58.81   58.26
   58.51   56.91   56.36    57.5   58.62   57.61   55.41   54.71   54.81   54.26
   54.86   57.66   57.75   54.95   54.95   54.74   54.33    54.6   54.91   55.61
   55.11   56.71   57.11   56.54   56.51   55.81   56.61   56.43   57.41   56.83
   57.05    57.8    57.7    57.2   57.71   55.31   58.01   57.89   57.99   58.18
    58.3   58.81   59.11   58.41   58.91   59.31   59.21   59.24   61.91      62
   60.84   60.53   59.94   59.24   58.04   59.04   59.04   58.14   58.74   57.94
   58.44   56.84   56.04   56.56   58.54   57.54   55.34   54.64   54.74   52.38
   51.97   51.94   52.09   52.09   51.67   52.81   52.93   54.53   54.84   55.54
   55.04   56.64   57.04   56.24   56.44   55.74   56.54   56.04   57.34   56.74
   56.84   57.37   57.28   57.14   57.64   55.24   57.94   57.74   55.94   55.34
   57.14   58.74   59.04   58.34   58.84   59.24   59.14   58.54   61.84   61.94
Pier Skew, UpSta & Num, DnSta & Num=  ,4979.6, 2 ,4979.6, 2 , 0 , 0 , 0 ,,
     1.5     1.5
   41.76   53.09
     1.5     1.5
    41.7   53.03
Pier Skew, UpSta & Num, DnSta & Num=  ,5019.4, 2 ,5019.4, 2 , 0 , 0 , 0 ,,
     1.5     1.5
   41.53   53.12
     1.5     1.5
   41.47   53.06
BR Coef= 1 , 1 , 1 ,1.25, 0 ,,,.8,0,2,0,
WSPro=,,,, 1 ,,,, 0 ,,,, 0 ,,,,-1 ,-1 ,-1 , 0 , 0 , 0 , 0 , 0
BR U #Sta/Elev= 199
  3489.2    60.9  3521.6   60.83  3533.7    60.8  3569.2   60.59  3633.7    60.2
  3699.2      60  3739.2   59.88  3759.2   59.82  3789.2   59.73  3879.2   59.46
  3933.7    59.3  3963.7    58.6  3973.7    58.1  3999.2   58.95  4003.7    59.1
  4009.2    59.1  4029.2    59.1  4059.2    59.1  4103.7    59.1  4129.2   58.34
  4133.7    58.2  4163.7    58.8  4203.7    58.4  4213.7      58  4229.2   58.39
  4233.7    58.5  4269.2   58.18  4349.2   57.47  4369.2    57.3  4413.7    56.9
  4419.2   56.68  4433.7    56.1  4439.2   56.21  4453.7    56.5  4459.2   56.62
  4553.7    58.6  4569.2   58.43  4629.2   57.76  4643.7    57.6  4653.7    57.2
  4673.7    55.4  4679.2   55.21  4683.2   55.07  4693.7    54.7  4698.5    54.7
  4718.5    55.1  4828.5    54.8  4849.3    54.8  4900.2   53.46  4926.9   52.75
  4938.9   52.44  4948.2   52.19 4948.69   52.03  4948.8      52 4948.91   51.96
    4949   51.93 4949.11    51.9  4949.2   51.87  4949.3   51.83  4952.4   50.83
    4955   50.54  4989.9   39.83  4990.5    35.8  4999.8   35.37  5009.5   35.87
  5010.1   39.87  5044.5   50.57  5046.9   50.79 5049.29   51.57  5049.4    51.6
  5049.5   51.63 5049.61   51.67 5049.69    51.7  5049.8   51.73  5049.9   51.76
  5053.3   52.87  5057.9   52.95  5060.1   52.99  5107.6    53.8  5113.2    53.9
  5133.2   54.24  5143.2   54.41  5153.4   54.59  5173.2   54.61  5203.2   54.63
  5223.2   54.65  5253.2   54.68  5263.2   54.69  5293.2   54.71  5383.2   54.79
  5463.2   54.86  5728.5    55.1  5793.2   54.92  5798.5    54.9  5823.2   55.48
  5828.5    55.6  5833.2   55.55  5863.2   55.25  5883.2   55.05  5888.5      55
  5938.5    55.3    5958    55.1  5968.8   55.27  6048.8   56.55    6058    56.7
    6168    57.1  6198.8   56.61  6202.8   56.54    6218    56.3  6228.8   56.31
  6258.8   56.32  6318.8   56.36    6388    56.4    6408    56.2    6418    56.5
  6428.8   56.12    6438    55.8  6438.8   55.84    6448    56.3    6508    56.6
  6518.8   56.33    6528    56.1    6618    57.4    6658    56.8  6678.8   56.85
  6698.8   56.89  6788.8   57.08  6818.8   57.15    6888    57.3  6898.8   57.08
    6908    56.9  6938.8   57.08  6998.8   57.43    7028    57.6    7058    57.4
    7078    57.5    7148    57.5  7158.8   57.34    7168    57.2  7168.8    57.2
    7268    57.7  7278.8   57.38    7288    57.1  7288.8   57.04    7308    55.6
  7308.8   55.58    7318    55.3  7318.8    55.4    7328    56.6  7328.8   56.66
    7348      58  7348.8      58  7358.8      58  7458.8   57.97  7478.8   57.96
  7508.8   57.95  7518.8   57.95  7578.8   57.93  7678.8    57.9    8028    57.8
    8058    56.7    8088      56    8148    55.7    8158      56    8188    55.4
    8198    55.4    8228    56.4    8268    57.2    8298    58.8    8388    59.1
  8388.8   59.07    8408    58.4  8408.8   58.44    8418    58.9  8428.8   58.91
  8438.8   58.92  8448.8   58.93  8458.8   58.94  8478.8   58.96  8488.8   58.97
  8508.8   58.99  8538.8   59.02  8568.8   59.05  8578.8   59.06  8598.8   59.08
  8618.8    59.1  8658.8   59.14    8818    59.3    9048    59.2    9068    58.6
  9188.8   59.68  9248.8   60.21  9308.8   60.75  9388.8   61.46    9438    61.9
  9456.2    61.6  9478.8   61.68  9528.8   61.85    9571      62
BR U #Mann= 7
  3489.2     .99  4553.7     .08  4926.9     .04    4955    .015  5044.5     .04
  5057.9     .08  6202.8     .99
BR D #Sta/Elev= 199
  3489.2   60.84  3521.6   60.77  3533.7   60.74  3569.2   60.53  3633.7   60.14
  3699.2   59.94  3739.2   59.82  3759.2   59.76  3789.2   59.67  3879.2    59.4
  3933.7   59.24  3963.7   58.54  3973.7   58.04  3999.2   58.89  4003.7   59.04
  4009.2   59.04  4029.2   59.04  4059.2   59.04  4103.7   59.04  4129.2   58.28
  4133.7   58.14  4163.7   58.74  4203.7   58.34  4213.7   57.94  4229.2   58.33
  4233.7   58.44  4269.2   58.12  4349.2   57.41  4369.2   57.24  4413.7   56.84
  4419.2   56.62  4433.7   56.04  4439.2   56.15  4453.7   56.44  4459.2   56.56
  4553.7   58.54  4569.2   58.37  4629.2    57.7  4643.7   57.54  4653.7   57.14
  4673.7   55.34  4679.2   55.15  4683.2   55.01  4693.7   54.64  4698.5   54.64
  4718.5   55.04  4828.5   54.74  4849.3   54.74  4900.2    53.4  4926.9   52.69
  4938.9   52.38  4948.2   52.13 4948.69   51.97  4948.8   51.94 4948.91    51.9
    4949   51.87 4949.11   51.84  4949.2   51.81  4949.3   51.77  4952.4   50.77
    4955   50.48  4989.9   39.77  4990.5   35.74  4999.8   35.31  5009.5   35.81
  5010.1   39.81  5044.5   50.51  5046.9   50.73 5049.29   51.51  5049.4   51.54
  5049.5   51.57 5049.61   51.61 5049.69   51.64  5049.8   51.67  5049.9    51.7
  5053.3   52.81  5057.9   52.89  5060.1   52.93  5107.6   53.74  5113.2   53.84
  5133.2   54.18  5143.2   54.35  5153.4   54.53  5173.2   54.55  5203.2   54.57
  5223.2   54.59  5253.2   54.62  5263.2   54.63  5293.2   54.65  5383.2   54.73
  5463.2    54.8  5728.5   55.04  5793.2   54.86  5798.5   54.84  5823.2   55.42
  5828.5   55.54  5833.2   55.49  5863.2   55.19  5883.2   54.99  5888.5   54.94
  5938.5   55.24    5958   55.04  5968.8   55.21  6048.8   56.49    6058   56.64
    6168   57.04  6198.8   56.55  6202.8   56.48    6218   56.24  6228.8   56.25
  6258.8   56.26  6318.8    56.3    6388   56.34    6408   56.14    6418   56.44
  6428.8   56.06    6438   55.74  6438.8   55.78    6448   56.24    6508   56.54
  6518.8   56.27    6528   56.04    6618   57.34    6658   56.74  6678.8   56.79
  6698.8   56.83  6788.8   57.02  6818.8   57.09    6888   57.24  6898.8   57.02
    6908   56.84  6938.8   57.02  6998.8   57.37    7028   57.54    7058   57.34
    7078   57.44    7148   57.44  7158.8   57.28    7168   57.14  7168.8   57.14
    7268   57.64  7278.8   57.32    7288   57.04  7288.8   56.98    7308   55.54
  7308.8   55.52    7318   55.24  7318.8   55.34    7328   56.54  7328.8    56.6
    7348   57.94  7348.8   57.94  7358.8   57.94  7458.8   57.91  7478.8    57.9
  7508.8   57.89  7518.8   57.89  7578.8   57.87  7678.8   57.84    8028   57.74
    8058   56.64    8088   55.94    8148   55.64    8158   55.94    8188   55.34
    8198   55.34    8228   56.34    8268   57.14    8298   58.74    8388   59.04
  8388.8   59.01    8408   58.34  8408.8   58.38    8418   58.84  8428.8   58.85
  8438.8   58.86  8448.8   58.87  8458.8   58.88  8478.8    58.9  8488.8   58.91
  8508.8   58.93  8538.8   58.96  8568.8   58.99  8578.8      59  8598.8   59.02
  8618.8   59.04  8658.8   59.08    8818   59.24    9048   59.14    9068   58.54
  9188.8   59.62  9248.8   60.15  9308.8   60.69  9388.8    61.4    9438   61.84
  9456.2   61.54  9478.8   61.62  9528.8   61.79    9571   61.94
BR D #Mann= 7
  3489.2     .99  4553.7     .08  4926.9     .04    4955    .015  5044.5     .04
  5057.9     .08  6202.8     .99
BC Design=,, 0 ,, 0 ,,,,,,
BC HTab HWMax=62.03

Type RM Length L Ch R = 1 ,22873.00,49.7,58,89.2
BEGIN DESCRIPTION:
RIGGS
Downstream Section of Bridge/Culvert/Weir
END DESCRIPTION:
XS GIS Cut Line= 4
      3117104.75      13865359.7      3116023.85     13864910.54
      3114756.34     13864889.93       3111293.4     13865402.46
#Sta/Elev= 30
  3521.6   60.74  4233.7   58.41  4433.7   56.01  4553.7   58.51  4643.7   57.51
  4693.7   54.61  4849.3   54.71  4926.9   52.66  4948.2    52.1    4955   50.45
  4989.9   39.74  4990.5   35.71  4999.8   35.28  5009.5   35.78  5010.1   39.78
  5044.5   50.48  5053.3   52.78  5057.9   52.86  5153.4    54.5    6168   57.01
    6438   55.71    7268   57.61    7318   55.21    7348   57.91  7458.8   57.88
    8028   57.71    8198   55.31    8298   58.71    9068   58.51  9456.2   61.51
#Mann= 7 ,-1 , 0
  3521.6      .1       0  4553.7     .08       0  4926.9     .04       0
    4955    .015       0  5044.5     .04       0  5057.9     .08       0
  7458.8      .1       0
#XS Ineff= 4 ,-1
 3769.23  4580.1    59.8 6464.15 9338.06    59.8    5059 6166.27      53
  4580.1    4939      53
Permanent Ineff=
       F       F       F       F
Bank Sta=4948.2,5053.3
XS Rating Curve= 0
Exp/Cntr=.5,.3

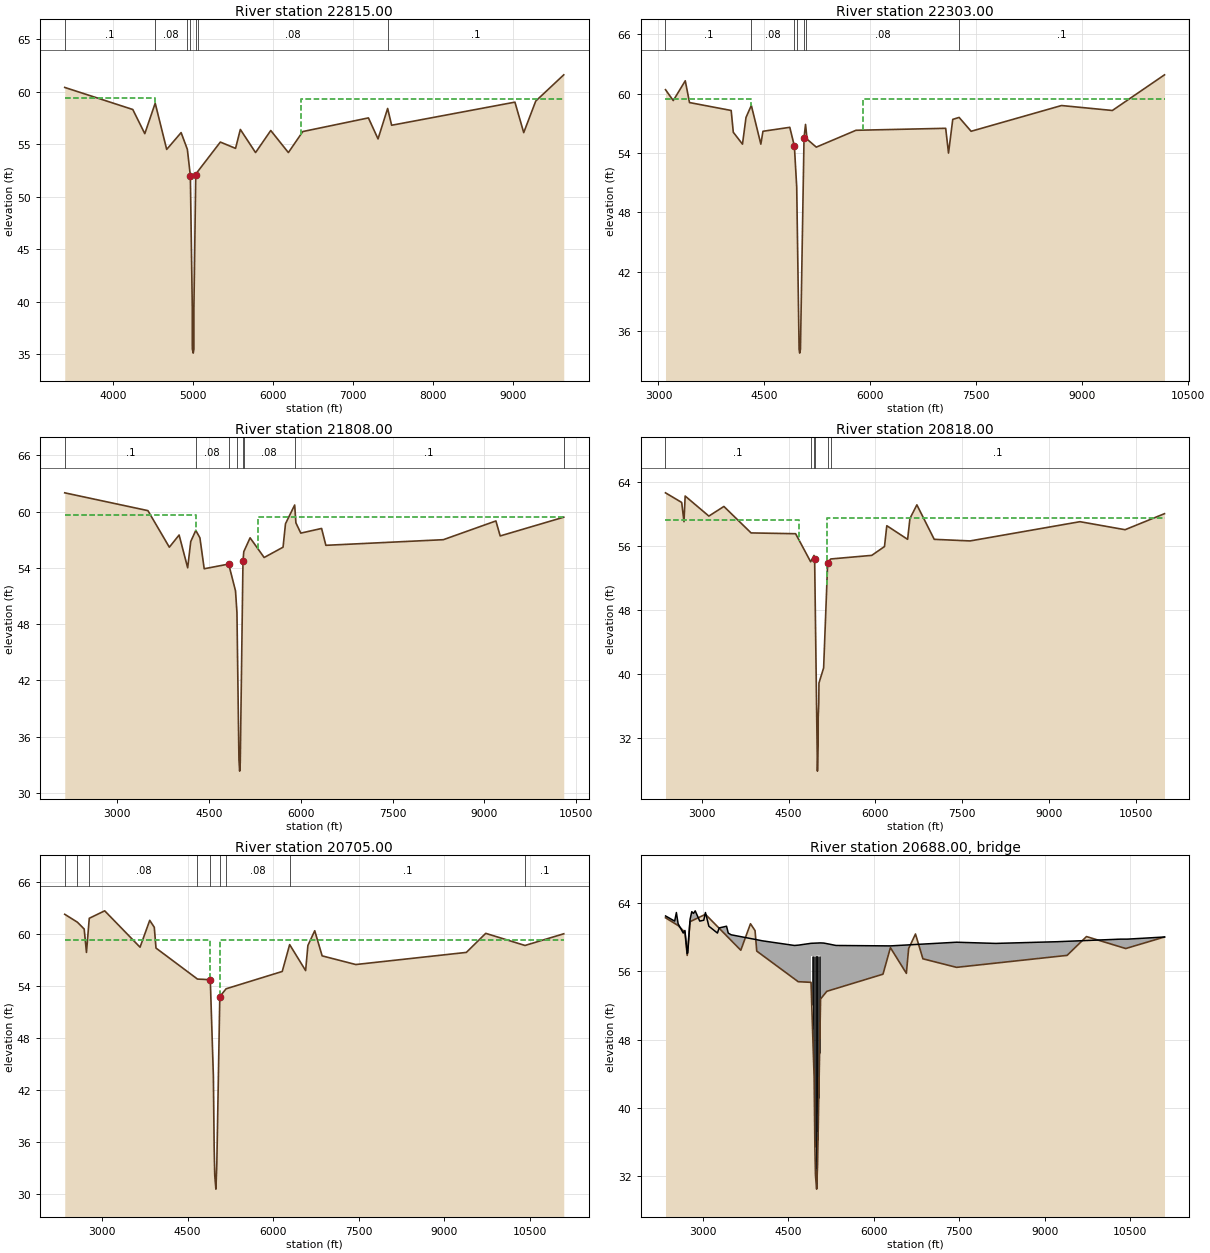
Type RM Length L Ch R = 1 ,22815.00,380.8,512,586.5
BEGIN DESCRIPTION:
Cross Section Xsec 18a
END DESCRIPTION:
XS GIS Cut Line= 4
      3117226.33     13865353.77      3116049.75     13864865.86
      3114752.04     13864791.63 3111129.375637513865313.5750868
#Sta/Elev= 30
  3395.9    60.4  4245.9    58.3  4395.9      56  4525.9    58.9  4669.6    54.5
  4849.6    56.1  4927.6   54.51  4965.1   51.99  4989.1    39.5  4989.7   35.51
    5001   35.11  5009.5   35.48  5009.7   39.51  5032.5   52.07  5057.6    52.4
  5339.6    55.2  5529.6    54.6  5589.6    56.4  5779.6    54.2  5969.5    56.3
  6189.5    54.2  6369.5    56.2  7189.5    57.5  7309.5    55.5  7429.5    58.4
  7479.5    56.8  9019.5      59  9129.5    56.1  9279.5    59.1  9629.5    61.6
#Mann= 7 ,-1 , 0
  3395.9      .1       0  4525.9     .08       0  4927.6     .04       0
  4965.1    .015       0  5032.5     .04       0  5057.6     .08       0
  7429.5      .1       0
#XS Ineff= 2 , 0
         4527.97   59.38 6342.79           59.32
Permanent Ineff=
       F       F
#Block Obstruct= 2 , 0
                          8664.6           59.25
Bank Sta=4965.1,5032.5
XS Rating Curve= 0
Exp/Cntr=.3,.1

Type RM Length L Ch R = 1 ,22303.00,319.7,495,670.4
BEGIN DESCRIPTION:
Cross Section x18
END DESCRIPTION:
XS GIS Cut Line= 4
      3117442.75      13864944.1      3115714.11     13864391.48
      3114860.69     13864167.56      3110562.35     13864944.25
#Sta/Elev= 30
  3099.1    60.4  3209.1    59.3  3379.1    61.3  3439.1    59.1  4029.1    58.3
  4059.1    56.1  4189.1    54.9  4239.1    57.6  4314.5   58.81  4449.1    54.9
  4479.1    56.2  4859.1    56.6  4923.9    54.7    4957   50.56  4990.8   34.19
  4999.2    33.8  5009.9    34.2  5060.6   55.55  5081.7   56.89  5103.9    55.4
  5233.9    54.6  5796.2    56.3  7066.2    56.5  7106.2      54  7166.2    57.4
  7256.2    57.6  7426.2    56.2  8706.2    58.8  9426.2    58.3 10164.2    61.9
#Mann= 7 ,-1 , 0
  3099.1      .1       0  4314.5     .08       0  4923.9     .04       0
    4957    .015       0  5060.6     .04       0  5081.7     .08       0
  7256.2      .1       0
#XS Ineff= 2 , 0
         4311.27   59.47 5893.62           59.47
Permanent Ineff=
       F       F
Bank Sta=4923.9,5060.6
XS Rating Curve= 0
Exp/Cntr=.3,.1

Type RM Length L Ch R = 1 ,21808.00,980.3,990,537.7
BEGIN DESCRIPTION:
Cross Section x17
END DESCRIPTION:
XS GIS Cut Line= 4
      3118444.18     13864919.19      3116021.22     13864156.25
      3115460.62     13863559.19      3110661.52     13863584.04
#Sta/Elev= 30
  2141.2      62  3501.2    60.1  3851.2    56.2  4011.2    57.5  4151.2      54
  4201.2    56.8  4283.5   57.99  4351.2    57.2  4421.2    53.9  4821.4    54.4
  4933.2   51.54  4956.6   49.23  4989.2   33.57  5000.9   32.31  5010.8   33.24
  5055.2    54.7  5068.5   55.72  5171.4    57.2  5401.4    55.1  5710.4    56.2
  5750.4    58.7  5900.4    60.7  5920.4    58.8  6000.4    57.7  6340.4    58.2
  6410.4    56.4  8330.4      57  9190.4      59  9260.4    57.4 10299.6    59.4
#Mann= 8 ,-1 , 0
  2141.2      .1       0  4283.5     .08       0  4821.4     .04       0
  4956.6    .015       0  5055.2     .04       0  5068.5     .08       0
  5900.4      .1       0 10299.6      .1       0
#XS Ineff= 2 , 0
         4293.14    59.6 5301.81           59.47
Permanent Ineff=
       F       F
Bank Sta=4821.4,5055.2
XS Rating Curve= 0
Exp/Cntr=.3,.1

Type RM Length L Ch R = 1 ,20818.00,120.1,113,94
BEGIN DESCRIPTION:
Cross Section Xsec 16b
END DESCRIPTION:
XS GIS Cut Line= 3
      3119185.93     13863823.68      3116380.84     13863338.83
      3110599.21      13863312.9
#Sta/Elev= 30
  2370.4    62.6  2650.4    61.4  2690.4      59  2710.4    62.2  3120.4    59.7
  3380.4    60.9  3850.4    57.6  4620.4    57.5  4880.4      54  4938.5   54.79
  4949.2   54.39  4997.6   27.89  5010.1   31.08  5010.8   34.57  5020.7   36.31
  5024.1   38.88  5104.9   40.77  5174.3   53.84  5227.3   54.35  5937.1    54.8
  6157.1    55.9  6197.1    58.5  6557.1    56.8  6597.1    59.4  6717.1    61.1
  7017.1    56.8  7637.1    56.6  9537.1      59 10317.1      58 10998.8      60
#Mann= 6 ,-1 , 0
  2370.4      .1       0  4880.4     .05       0  4938.5     .04       0
  4949.2     .04       0  5174.3     .08       0  5227.3      .1       0
#XS Ineff= 2 , 0
         4687.16   59.26 5159.97           59.41
Permanent Ineff=
       F       F
Bank Sta=4949.2,5174.3
XS Rating Curve= 0
Exp/Cntr=.5,.3

Type RM Length L Ch R = 1 ,20705.00,37.9,35,34.8
BEGIN DESCRIPTION:
HOUSTON BELT TERMINAL R.R u/s
Upstream Section of Bridge/Culvert/Weir
END DESCRIPTION:
XS GIS Cut Line= 3
      3119298.76      13863401.4      3116386.97     13863266.15
      3110551.29      13863044.7
#Sta/Elev= 30
  2345.5   62.25  2567.1   61.34  2686.6   60.55  2726.6   57.85    2776   61.79
  3046.6   62.65  3666.6   58.45  3836.6   61.55  3916.6   60.75  3946.6   58.35
  4674.5   54.77  4899.1    54.7  4953.4   43.54  4966.8   35.42  4977.1   32.13
  4997.4   30.52  5013.6   33.39  5066.1   52.75  5176.6   53.65  6161.5   55.65
  6291.5   58.75  6571.5   55.75  6611.5   58.65  6731.5   60.35  6861.5   57.45
  7451.5   56.45  9391.5   57.85  9731.5   60.05 10420.3   58.65 11100.3      60
#Mann= 9 ,-1 , 0
  2345.5     .05       0  2567.1     .08       0    2776     .08       0
  4674.5     .05       0  4899.1     .04       0  5066.1     .04       0
  5176.6     .08       0  6291.5      .1       0 10420.3      .1       0
#XS Ineff= 2 , 0
       0 4889.92   59.23  5072.8       0    59.3
Permanent Ineff=
       F       F
Bank Sta=4899.1,5066.1
XS Rating Curve= 0
Exp/Cntr=.5,.3

Type RM Length L Ch R = 3 ,20688.00,,,
BEGIN DESCRIPTION:
HOUSTON BELT TERMINAL R.R
Structure ID: E101-00-00-15
END DESCRIPTION:
Bridge Culvert--1,0,-1,-1, 0
Deck Dist Width WeirC Skew NumUp NumDn MinLoCord MaxHiCord MaxSubmerge Is_Ogee
10,14,2.6,0, 49, 49, , , .95, 0, ,,,
  2346.6  2359.4  2506.6  2536.6  2566.6  2567.1  2656.6  2686.6  2726.6  2736.6
    2776  2776.6  2806.6  2836.6  2866.6  2946.6  3016.6  3046.6  3106.6  3256.6
  3286.6  3416.6  3446.6  3496.6  4049.4  4606.6  4646.6  4674.5  4679.4  4866.6
  4886.6 4897.81  4897.9 5062.79  5062.9    5123  5216.6  5226.6  5246.6  5291.5
  5321.5  5341.5  6291.5  7451.5  8139.4  9219.4 10329.4 10449.4 11100.3
   62.46   62.41   61.86   62.86   61.56   61.55   60.46   60.76   58.06   58.16
      62   62.06   62.96   62.76   63.06   61.86   61.96   62.86   61.26   60.46
   61.06   61.26   60.46   60.26   59.55   59.01   59.03   59.05   59.05   59.23
   59.25   59.26   59.26   59.31   59.31   59.29   59.17   59.16   59.13   59.07
   59.03   59.01   58.96   59.39   59.25   59.45   59.75   59.75      60
                                                                                
                                                                                
                                                                                
                   57.77   57.82
                                                                        
  2346.6  2359.4  2506.6  2536.6  2566.6  2567.1  2656.6  2686.6  2726.6  2736.6
    2776  2776.6  2806.6  2836.6  2866.6  2946.6  3016.6  3046.6  3106.6  3256.6
  3286.6  3416.6  3446.6  3496.6  4049.4  4606.6  4646.6  4674.5  4679.4  4866.6
  4886.6 4897.81  4897.9 5062.79  5062.9    5123  5216.6  5226.6  5246.6  5291.5
  5321.5  5341.5  6291.5  7451.5  8139.4  9219.4 10329.4 10449.4 11100.3
   62.46   62.41   61.86   62.86   61.56   61.55   60.46   60.76   58.06   58.16
      62   62.06   62.96   62.76   63.06   61.86   61.96   62.86   61.26   60.46
   61.06   61.26   60.46   60.26   59.55   59.01   59.03   59.05   59.05   59.23
   59.25   59.26   59.26   59.31   59.31   59.29   59.17   59.16   59.13   59.07
   59.03   59.01   58.96   59.39   59.25   59.45   59.75   59.75      60
                                                                                
                                                                                
                                                                                
                   57.77   57.82
                                                                        
Pier Skew, UpSta & Num, DnSta & Num=  ,4912.2, 2 ,4912.2, 2 , 0 , 0 , 0 ,,
       1       1
   51.61   58.44
       1       1
   52.32   59.15
Pier Skew, UpSta & Num, DnSta & Num=  ,4925.5, 2 ,4925.5, 2 , 0 , 0 , 0 ,,
       1       1
   48.27   58.47
       1       1
   48.98   59.18
Pier Skew, UpSta & Num, DnSta & Num=  ,4939.7, 2 ,4939.7, 2 , 0 , 0 , 0 ,,
       1       1
    45.5   58.48
       1       1
   46.21   59.19
Pier Skew, UpSta & Num, DnSta & Num=  ,4953.4, 2 ,4953.4, 2 , 0 , 0 , 0 ,,
       1       1
   42.09   58.48
       1       1
    42.8   59.19
Pier Skew, UpSta & Num, DnSta & Num=  ,4966.8, 2 ,4966.8, 2 , 0 , 0 , 0 ,,
       1       1
   34.11   58.49
       1       1
   34.82    59.2
Pier Skew, UpSta & Num, DnSta & Num=  ,4981, 2 ,4981, 2 , 0 , 0 , 0 ,,
       1       1
   29.77   58.49
       1       1
   30.48    59.2
Pier Skew, UpSta & Num, DnSta & Num=  ,4995.1, 2 ,4995.1, 2 , 0 , 0 , 0 ,,
       1       1
    28.6   58.47
       1       1
   29.31   59.18
Pier Skew, UpSta & Num, DnSta & Num=  ,5007.5, 2 ,5007.5, 2 , 0 , 0 , 0 ,,
       1       1
   30.47   58.46
       1       1
   31.18   59.17
Pier Skew, UpSta & Num, DnSta & Num=  ,5021.4, 2 ,5021.4, 2 , 0 , 0 , 0 ,,
       1       1
   35.74   58.45
       1       1
   36.45   59.16
Pier Skew, UpSta & Num, DnSta & Num=  ,5034.7, 2 ,5034.7, 2 , 0 , 0 , 0 ,,
       1       1
   40.45   58.45
       1       1
   41.16   59.16
Pier Skew, UpSta & Num, DnSta & Num=  ,5049, 2 ,5049, 2 , 0 , 0 , 0 ,,
       1       1
   44.93   58.46
       1       1
   45.64   59.17
BR Coef= 1 , 1 , 1 ,1.25, 0 ,,,.8,0,2,0,
WSPro=,,,, 1 ,,,, 0 ,,,, 0 ,,,,-1 ,-1 ,-1 , 0 , 0 , 0 , 0 , 0
BC Design=,, 0 ,, 0 ,,,,,,
BC HTab HWMax=62.85