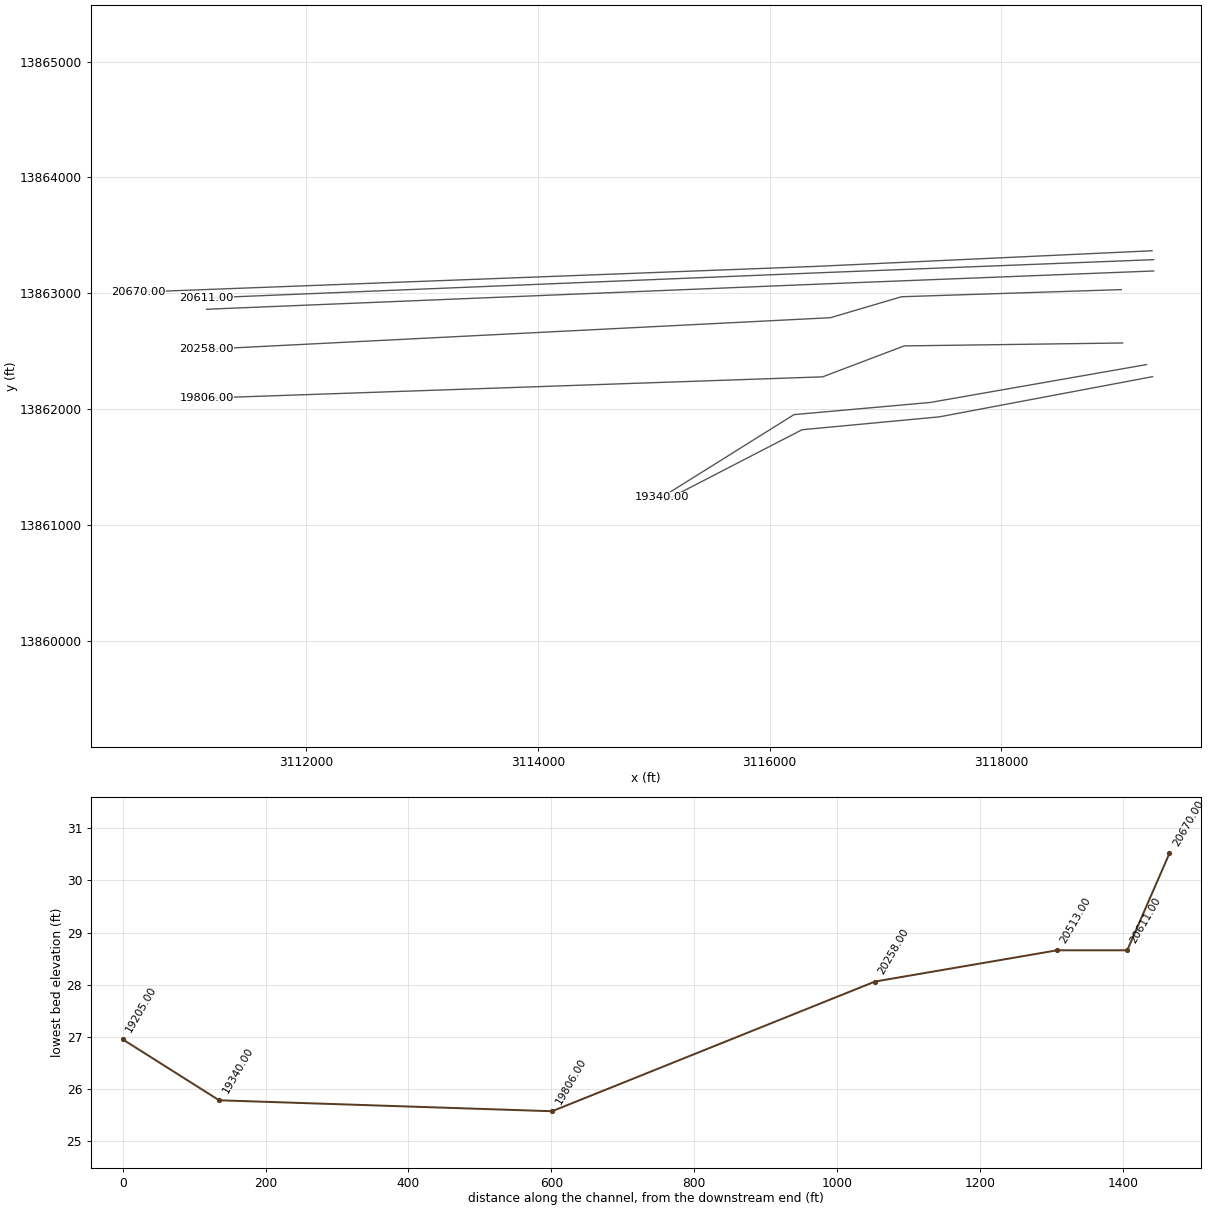
HEC-RAS study E101_00_00.prj: E101-00-00

--- E101_00_00.g01 (geometry) --- (continued)

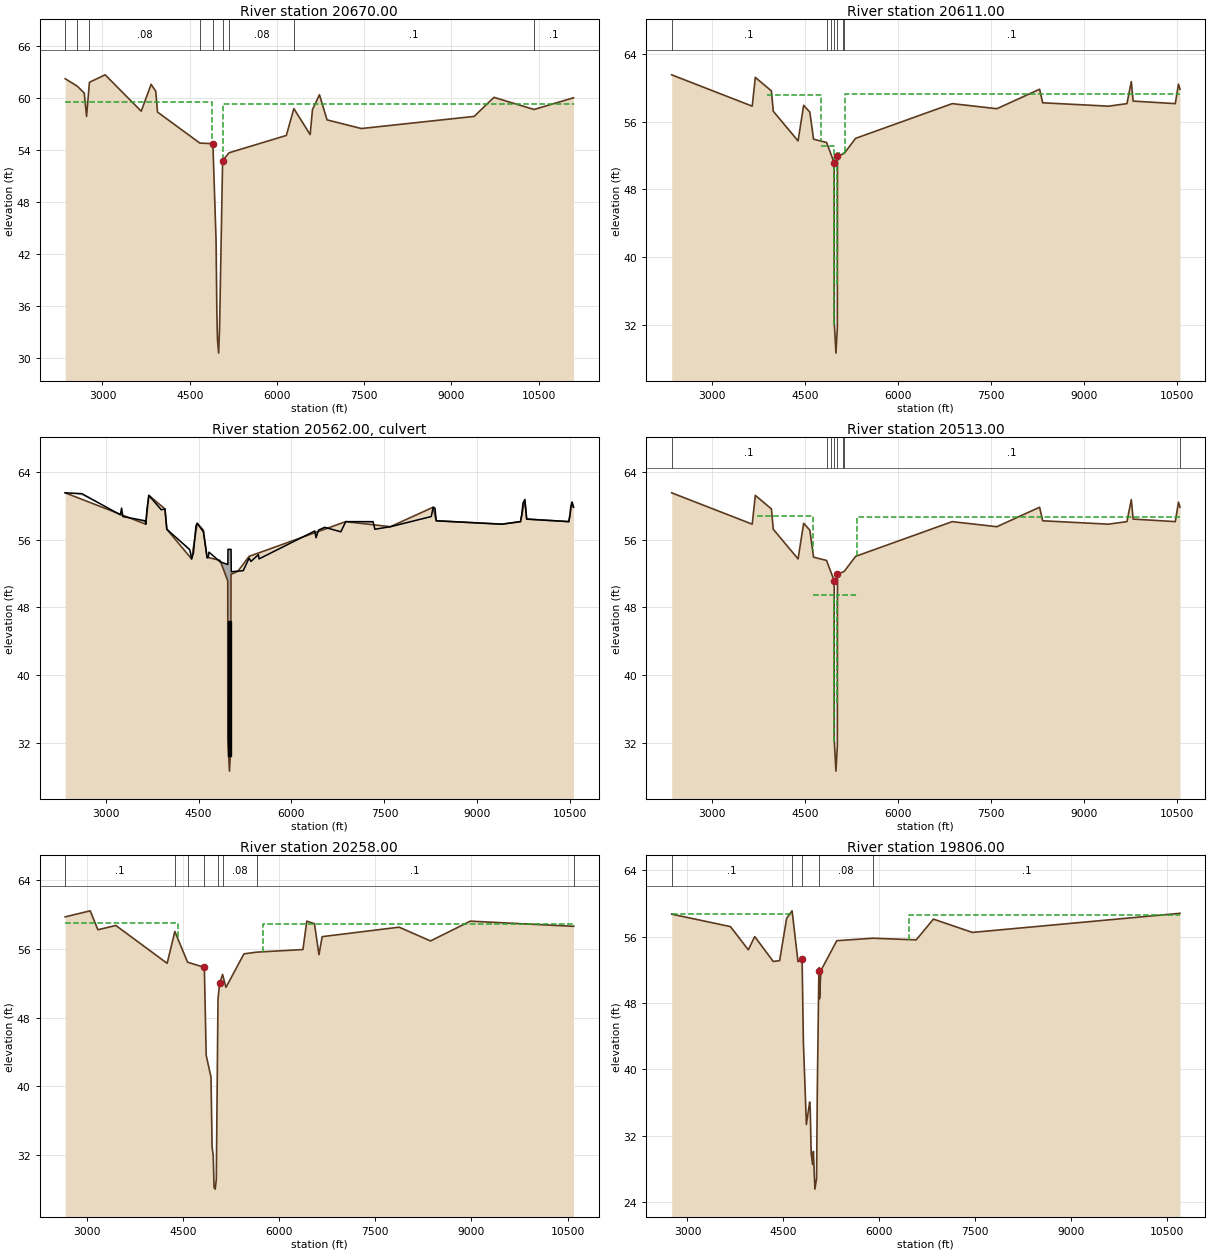
Type RM Length L Ch R = 1 ,20670.00,64.5,59,58.8
BEGIN DESCRIPTION:
HOUSTON BELT TERMINAL R.R
Downstream Section of Bridge/Culvert/Weir
END DESCRIPTION:
XS GIS Cut Line= 3
      3119300.15      13863366.9      3116388.23      13863231.6
      3110553.52      13863010.2
#Sta/Elev= 30
  2359.4    62.2  2567.1   61.34  2686.6   60.55  2726.6   57.85    2776   61.79
  3046.6   62.65  3666.6   58.45  3836.6   61.55  3916.6   60.75  3946.6   58.35
  4674.5   54.77  4899.1    54.7  4953.4   43.54  4966.8   35.42  4977.1   32.13
  4997.4   30.52  5013.6   33.39  5066.1   52.75  5176.6   53.65  6161.5   55.65
  6291.5   58.75  6571.5   55.75  6611.5   58.65  6731.5   60.35  6861.5   57.45
  7451.5   56.45  9391.5   57.85  9731.5   60.05 10421.4   58.65 11100.3      60
#Mann= 9 ,-1 , 0
  2359.4     .05       0  2567.1     .08       0    2776     .08       0
  4674.5     .05       0  4899.1     .04       0  5066.1     .04       0
  5176.6     .08       0  6291.5      .1       0 10421.4      .1       0
#XS Ineff= 2 , 0
       0 4889.92   59.47  5072.8       0    59.3
Permanent Ineff=
       F       F
Bank Sta=4899.1,5066.1
XS Rating Curve= 0
Exp/Cntr=.5,.3

Type RM Length L Ch R = 1 ,20611.00,97.6,98,101.7
BEGIN DESCRIPTION:
STOKES u/s
Upstream Section of Bridge/Culvert/Weir
END DESCRIPTION:
XS GIS Cut Line= 3
      3119313.39     13863290.11      3116487.31     13863179.35
      3111140.08     13862959.84
#Sta/Elev= 30
    2348   61.51    3648   57.81    3698   61.21    3958   59.61    3988   57.21
    4388   53.71    4478   57.91    4578   57.11    4638   53.91  4847.7   53.53
  4919.6   52.13  4971.8   51.11  4972.7   32.26  4999.2   28.66    5022   31.66
  5024.1   51.89  5120.9    52.2  5133.6   52.24  5316.2   54.01  6876.2   58.11
  7596.2   57.51  8286.2   59.81  8336.2   58.21  9396.2   57.81  9696.2   58.11
  9766.2   60.71  9796.2   58.41 10476.2   58.11   10528   60.41 10552.3   59.81
#Mann= 7 ,-1 , 0
    2348      .1       0  4847.7     .05       0  4919.6     .04       0
  4971.8    .045       0  5024.1     .04       0  5120.9     .08       0
  5133.6      .1       0
#XS Ineff= 4 ,-1
 5152.09 10552.3   59.26 3883.37  4750.2   59.12  4750.2  4974.7   53.07
 5022.52 5152.09   52.34
Permanent Ineff=
       F       F       F       F
Bank Sta=4971.8,5024.1
XS Rating Curve= 0
Exp/Cntr=.5,.3

Type RM Length L Ch R = 2 ,20562.00,,,
BEGIN DESCRIPTION:
STOKES
Structure ID: E101-00-00-14
END DESCRIPTION:
Bridge Culvert--1,0,-1,-1, 0
Deck Dist Width WeirC Skew NumUp NumDn MinLoCord MaxHiCord MaxSubmerge Is_Ogee
10,78,2.6,0, 60, 60, , , .95, 0, ,,,
    2348    2618    3238    3258    3278    3638    3648    3668    3698    3898
    3958    3988    4358    4388    4418    4458    4478    4578    4638    4658
    4668  4847.7  4971.8  4972.7    4975  4980.9  4999.2    5022  5024.1    5025
    5028  5220.9  5316.2  5346.2  5466.2  5476.2  6376.2  6396.2  6436.2  6536.8
  6796.2  6876.2  7316.2  7346.2  7596.2  8256.2  8286.2  8316.2  8336.2  9396.2
  9696.2  9716.2  9736.2  9766.2  9796.2 10476.2 10496.2 10506.2   10528 10552.3
   61.51   61.41   58.91   59.71   58.71   58.21   57.81   59.61   61.21   59.51
   59.61   57.21   54.81   53.71   54.41   57.61   57.91   56.91   53.82   53.91
   54.51   53.37   53.05   53.05   54.84   54.84   54.84   54.84   54.84   54.84
    52.2   52.32   53.81   53.41   54.21   53.71   57.01   56.21   57.11   57.44
   56.91   58.11   58.11   57.21   57.51   58.71   59.81   59.71   58.21   57.81
   58.11   58.91   60.31   60.71   58.41   58.11   58.91   59.81   60.41   59.81
    61.3    61.2    58.7    59.5    58.5      58    57.6    59.4      61    59.3
    59.4      57    54.6    53.5    54.2    57.4    57.7    56.9    53.7    53.9
    54.5   53.32    50.9   32.05   30.25   30.25   28.45   31.45   51.68   51.68
   51.86   52.31    53.8    53.4    54.2    53.7      57    56.2    57.1   57.23
    56.7    57.9    57.9      57    57.3    58.5    59.6    59.5      58    57.6
    57.9    58.7    60.1    60.5    58.2    57.9    58.7    59.6    60.2    59.6
    2348    2618    3238    3258    3278    3638    3648    3668    3698    3898
    3958    3988    4358    4388    4418    4458    4478    4578    4638    4658
    4668  4847.7  4971.8  4972.7    4975  4980.9  4999.2    5022  5024.1    5025
    5028  5220.9  5316.2  5346.2  5466.2  5476.2  6376.2  6396.2  6436.2  6536.8
  6796.2  6876.2  7316.2  7346.2  7596.2  8256.2  8286.2  8316.2  8336.2  9396.2
  9696.2  9716.2  9736.2  9766.2  9796.2 10476.2 10496.2 10506.2   10528 10552.3
   61.51   61.41   58.91   59.71   58.71   58.21   57.81   59.61   61.21   59.51
   59.61   57.21   54.81   53.71   54.41   57.61   57.91   56.91   53.82   53.91
   54.51   53.37   53.05   53.05   54.84   54.84   54.84   54.84   54.84   54.84
    52.2   52.32   53.81   53.41   54.21   53.71   57.01   56.21   57.11   57.44
   56.91   58.11   58.11   57.21   57.51   58.71   59.81   59.71   58.21   57.81
   58.11   58.91   60.31   60.71   58.41   58.11   58.91   59.81   60.41   59.81
    61.3    61.2    58.7    59.5    58.5      58    57.6    59.4      61    59.3
    59.4      57    54.6    53.5    54.2    57.4    57.7    56.9    53.7    53.9
    54.5   53.32    50.9   32.05   30.25   30.25   28.45   31.45   51.68   51.68
   51.86   52.31    53.8    53.4    54.2    53.7      57    56.2    57.1   57.23
    56.7    57.9    57.9      57    57.3    58.5    59.6    59.5      58    57.6
    57.9    58.7    60.1    60.5    58.2    57.9    58.7    59.6    60.2    59.6
BR Coef= 1 , 1 , 1 ,1.25, 0 ,,,.8,0,2,0,
WSPro=,,,, 1 ,,,, 0 ,,,, 0 ,,,,-1 ,-1 ,-1 , 0 , 0 , 0 , 0 , 0
Culvert=2,16,15,78,.015,.5,1,8,1,30.4,4982.1,30.31,4982.1,Culvert #1  , 0 ,10
Culvert Bottom n=.015
Culvert=2,16,15,78,.015,.5,1,8,1,30.4,4998.7,30.31,4998.7,Culvert #2  , 0 ,10
Culvert Bottom n=.015
Culvert=2,16,15,78,.015,.5,1,8,1,30.4,5014.9,30.31,5014.9,Culvert #3  , 0 ,10
Culvert Bottom n=.015
BC Design=,, 0 ,, 0 ,,,,,,
BC HTab HWMax=61.51

Type RM Length L Ch R = 1 ,20513.00,219.5,255,319.4
BEGIN DESCRIPTION:
STOKES
Downstream Section of Bridge/Culvert/Weir
END DESCRIPTION:
XS GIS Cut Line= 3
      3119314.18     13863192.47      3116488.22     13863081.71
      3111141.11     13862862.21
#Sta/Elev= 30
    2348   61.51    3648   57.81    3698   61.21    3958   59.61    3988   57.21
    4388   53.71    4478   57.91    4578   57.11    4638   53.91  4847.7   53.53
  4919.6   52.13  4971.8   51.11  4972.7   32.26  4999.2   28.66    5022   31.66
  5024.1   51.89  5120.9    52.2  5133.6   52.24  5316.2   54.01  6876.2   58.11
  7596.2   57.51  8286.2   59.81  8336.2   58.21  9396.2   57.81  9696.2   58.11
  9766.2   60.71  9796.2   58.41 10476.2   58.11   10528   60.41 10552.3   59.81
#Mann= 8 ,-1 , 0
    2348      .1       0  4847.7     .05       0  4919.6     .04       0
  4971.8    .045       0  5024.1     .04       0  5120.9     .08       0
  5133.6      .1       0 10552.3      .1       0
#XS Ineff= 4 ,-1
 3717.89 4624.11   58.78 5341.21 10552.3   58.68 5022.52 5341.21    49.4
 4624.11  4974.7    49.4
Permanent Ineff=
       F       F       F       F
Bank Sta=4971.8,5024.1
XS Rating Curve= 0
Exp/Cntr=.5,.3

Type RM Length L Ch R = 1 ,20258.00,346.6,452,276.3
BEGIN DESCRIPTION:
Cross Section Xsec 16a
END DESCRIPTION:
XS GIS Cut Line= 4
 3119034.797121813863031.6718398      3117138.67     13862970.28
       3116524.2     13862789.24       3111140.8     13862517.06
#Sta/Elev= 30
  2664.7    59.7  3054.7    60.4  3174.7    58.2  3454.7    58.7  4254.7    54.3
  4374.7      58  4573.4   54.43  4834.6   53.83  4863.7    43.6  4938.7   41.07
  4955.9   32.94  4972.9      32  4986.6   28.25  5004.1   28.06  5021.1   29.15
  5047.8   50.18  5073.7   51.96    5119   53.01  5171.8    51.5  5452.4    55.4
  5652.4    55.6  6372.4    55.9  6432.4    59.2  6552.4    58.9  6622.4    55.3
  6672.4    57.4  7872.4    58.5  8362.4    56.9  8982.4    59.2 10592.7    58.6
#Mann= 8 ,-1 , 0
  2664.7      .1       0  4374.7     .08       0  4573.4     .05       0
  4834.6     .08       0  5047.8     .04       0    5119     .08       0
  5652.4      .1       0 10592.7      .1       0
#XS Ineff= 2 , 0
         4427.11   58.97 5750.98           58.82
Permanent Ineff=
       F       F
Bank Sta=4834.6,5073.7
XS Rating Curve= 0
Exp/Cntr=.3,.1

Type RM Length L Ch R = 1 ,19806.00,555.1,466,748.9
BEGIN DESCRIPTION:
Cross Section x16
END DESCRIPTION:
XS GIS Cut Line= 4
 3119046.281360813862571.1847516      3117161.35     13862545.95
      3116457.69     13862279.06      3111140.85      13862095.8
#Sta/Elev= 30
  2752.5    58.7  3672.5    57.2  3952.5    54.4  4052.5      56  4342.5      53
  4442.5    53.1  4552.5    58.2  4637.6    59.1  4730.1   52.98  4794.5   53.26
  4814.6   43.26  4861.4   33.35  4912.6   36.07  4921.7   35.26  4936.1   29.92
  4958.3   28.54    4971   30.12  4994.3   25.57    5021   26.86  5032.2   37.33
  5057.1   51.85  5062.6   52.25  5067.6    48.5  5087.6    51.9  5337.6    55.5
  5900.2    55.8  6580.2    55.6  6850.2    58.1  7460.2    56.5 10710.2    58.8
#Mann= 5 ,-1 , 0
  2752.5      .1       0  4637.6     .05       0  4794.5    .045       0
  5062.6     .08       0  5900.2      .1       0
#XS Ineff= 2 , 0
         4639.87   58.71 6460.21           58.58
Permanent Ineff=
       F       F
Bank Sta=4794.5,5057.1
XS Rating Curve= 0
Exp/Cntr=.3,.1

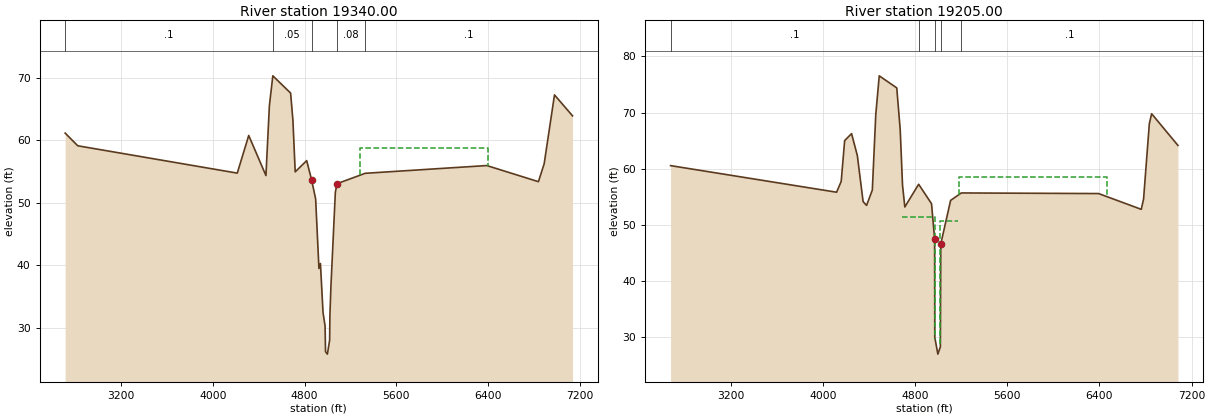
Type RM Length L Ch R = 1 ,19340.00,134.6,135,138.1
BEGIN DESCRIPTION:
Cross Section Xsec 15a
END DESCRIPTION:
XS GIS Cut Line= 4
      3119252.31     13862384.78      3117385.72     13862057.92
      3116210.55     13861953.08      3115068.28     13861238.94
#Sta/Elev= 30
  2713.7   61.13  2823.7    59.1  4213.7   54.73  4313.7   60.75  4463.7   54.34
  4493.7   65.52  4523.7   70.29  4678.7   67.53  4698.7   63.19  4718.7   54.93
  4818.7   56.73  4860.9    53.7  4896.8    50.6  4925.6   39.48  4938.6   40.27
  4961.2   32.43  4979.2   30.27  4982.9   26.18  4999.1   25.78  5018.8   28.02
  5021.1   31.97  5030.1   36.64  5068.6   51.68  5083.4   53.04  5328.7    54.7
  6388.5   55.94  6838.5   53.36  6888.5   56.22  6978.5   67.24  7135.7   63.89
#Mann= 5 ,-1 , 0
  2713.7      .1       0  4523.7     .05       0  4860.9     .04       0
  5083.4     .08       0  5328.7      .1       0
#XS Ineff= 2 ,-1
  2713.7 4690.31   59.49 5281.32 6401.89   58.82
Permanent Ineff=
       F       F
Bank Sta=4860.9,5083.4
XS Rating Curve= 0
Exp/Cntr=.5,.3

Type RM Length L Ch R = 1 ,19205.00,1429.4,1428,1416.6
BEGIN DESCRIPTION:
LOOP 610 / I-45 u/s
Upstream Section of Bridge/Culvert/Weir
END DESCRIPTION:
XS GIS Cut Line= 4
      3119304.39      13862280.6      3117464.88     13861933.88
      3116279.21     13861822.47      3115090.41     13861208.19
#Sta/Elev= 30
  2679.8   60.54  4119.8    55.8  4159.8   57.73  4189.8      65  4249.8   66.24
  4299.8   62.33  4349.8   54.13  4379.8   53.45  4429.8   56.19  4459.8   69.68
  4489.8   76.54  4641.7   74.39  4671.7   66.93  4691.7   57.06  4711.7   53.17
  4831.7   57.22  4943.4   53.75    4970   47.48  4971.5   29.95  4998.2   26.95
  5019.9   28.25  5023.8    46.6  5108.8   54.34  5201.7   55.67  6392.6   55.56
  6762.6   52.75  6782.6   54.59  6832.6   68.03  6852.6   69.78  7080.7   64.14
#Mann= 5 ,-1 , 0
  2679.8      .1       0  4831.7     .05       0    4970     .04       0
  5023.8     .05       0  5201.7      .1       0
#XS Ineff= 4 ,-1
  2679.8 4685.58   59.93 5177.31 6468.08   58.43 4685.58 4973.86   51.34
    5020 5172.58   50.71
Permanent Ineff=
       F       F       F       F
#Block Obstruct= 2 , 0
         4500.89   56.33
Bank Sta=4970,5023.8
XS Rating Curve= 0
Exp/Cntr=.5,.3