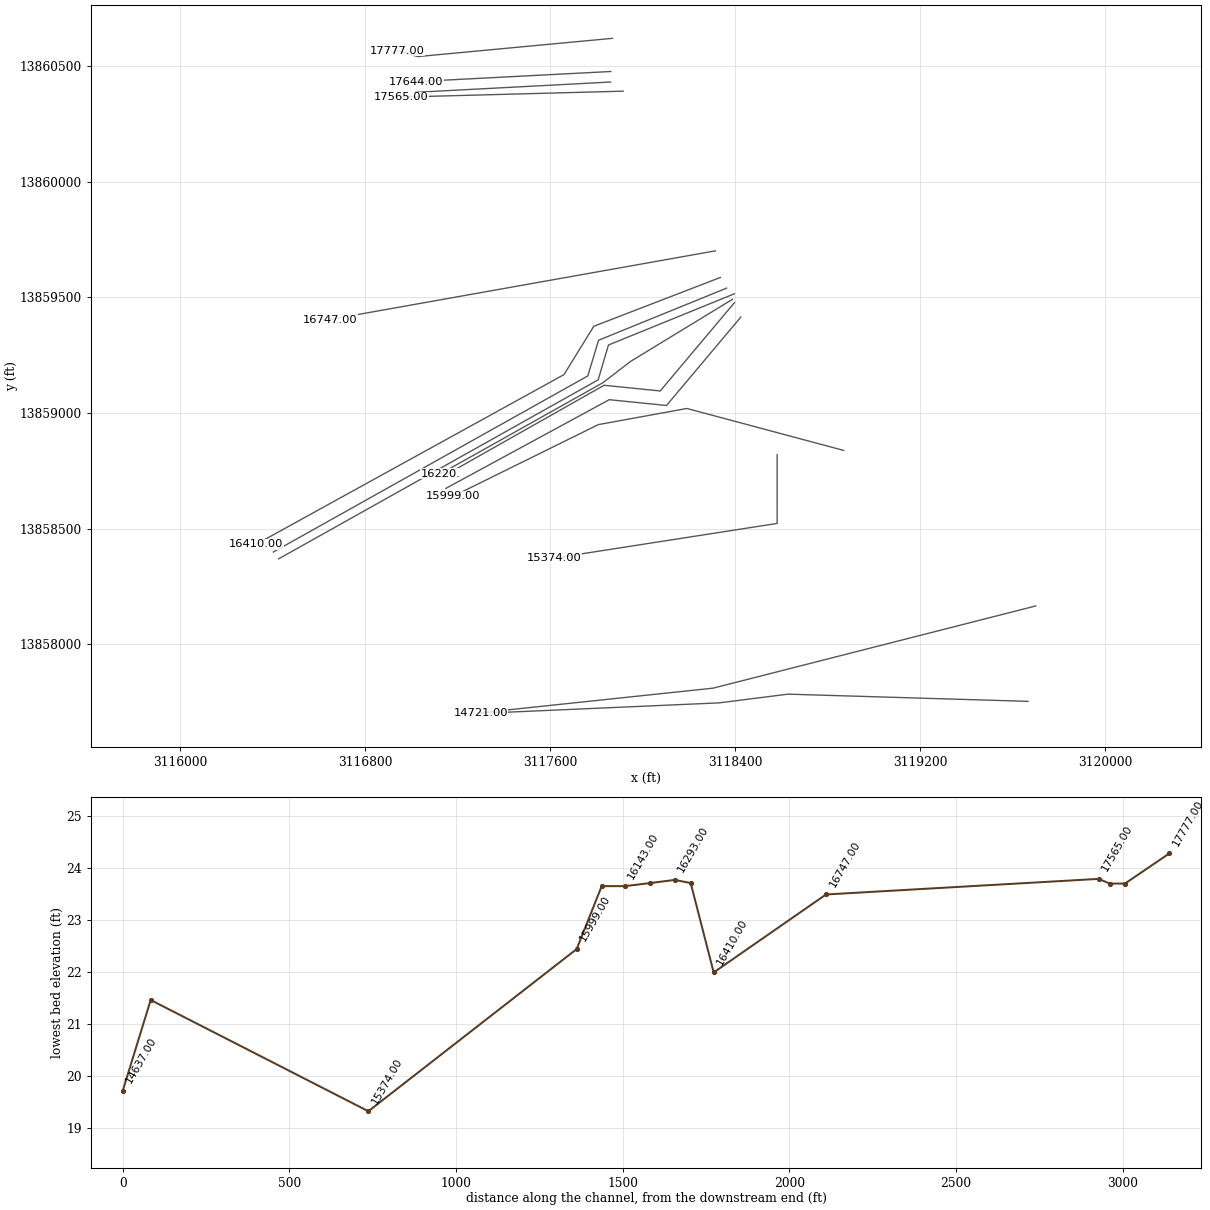
HEC-RAS study E101_00_00.prj: E101-00-00

--- E101_00_00.g01 (geometry) --- (continued)

Type RM Length L Ch R = 2 ,18492.00,,,
BEGIN DESCRIPTION:
LOOP 610/I45
Structure ID: E101-00-00-13
END DESCRIPTION:
Bridge Culvert--1,0,-1,-1, 0
Deck Dist Width WeirC Skew NumUp NumDn MinLoCord MaxHiCord MaxSubmerge Is_Ogee
10,1406,2.3,0, 36, 36, , , .95, 0, ,,,
  4506.3  4586.3  4616.3  4636.3  4805.4  4842.5  4912.5  5024.9  5074.9  5130.9
  5254.4    5373  5440.2  5530.2    5800    6150    6250  6490.7  6534.2  6544.2
  6554.2  6584.2  6594.2  6614.2  6634.2  6644.2  6744.2  6754.2  6764.2  6784.2
  6799.9    6825    6840    6930    7130    7200
   72.79   73.08   66.94    57.8   56.64   56.74   57.82   58.16   58.06   57.62
   57.06   56.95   56.84   56.98      58      60      62   70.16   70.27    70.2
   69.48   63.45   62.15   58.68   54.35   52.77   53.44   53.91    55.1   60.44
   64.05      68      69      68      60      58
                                                                                
                                                                                
                                                                                
                                                
  4506.3  4586.3  4616.3  4636.3  4805.4  4842.5  4912.5  5024.9  5074.9  5130.9
  5254.4    5373  5440.2  5530.2    5850    6200    6300  6540.7  6584.2  6594.2
  6604.2  6634.2  6644.2  6664.2  6684.2  6694.2  6794.2  6804.2  6814.2  6834.2
  6849.9    6875    6890    6980    7180    7250
   70.12   70.41   64.27   55.13   53.97   54.07   55.15   55.49   55.39   54.95
   54.39   54.28   54.17   54.31   55.33   57.33   59.33   67.49    67.6   67.53
   66.81   60.78   59.48   56.01   51.68    50.1   50.77   51.24   52.43   57.77
   61.38   65.33      69   65.33   57.33   55.33
                                                                                
                                                                                
                                                                                
                                                
BR Coef= 1 , 1 , 1 ,1.25, 0 ,,,.8,0,2,0,
WSPro=,,,, 1 ,,,, 0 ,,,, 0 ,,,,-1 ,-1 ,-1 , 0 , 0 , 0 , 0 , 0
Culvert=2,16,15,1406,.015,.4,1,8,1,28.41,4981.4,26.15,4981.4,Culvert #1  , 0 ,10
Culvert Bottom n=.015
Culvert=2,16,15,1406,.015,.4,1,8,1,28.41,4996.6,26.15,4996.6,Culvert #2  , 0 ,10
Culvert Bottom n=.015
Culvert=2,16,15,1406,.015,.4,1,8,1,28.41,5012.6,26.15,5012.6,Culvert #3  , 0 ,10
Culvert Bottom n=.015
BC Design=,, 0 ,, 0 ,,,,,,
BC HTab HWMax=76.54

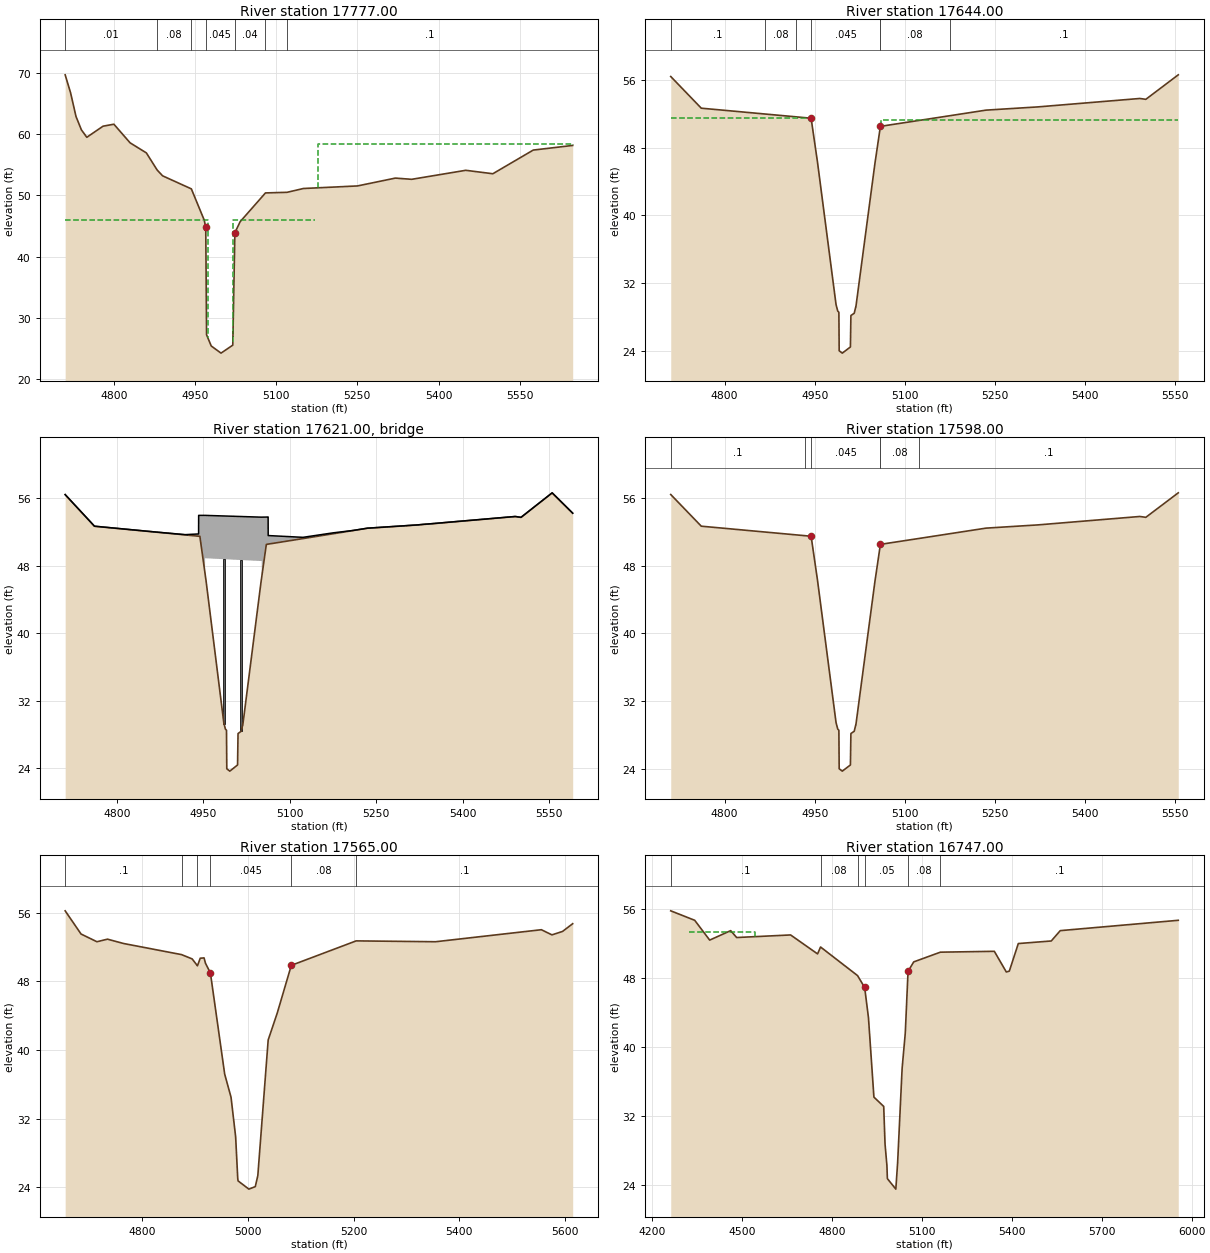
Type RM Length L Ch R = 1 ,17777.00,135,133,129
BEGIN DESCRIPTION:
LOOP 610 / I-45
Downstream Section of Bridge/Culvert/Weir
RASlevee: not a FEMA certified flood control levee
END DESCRIPTION:
XS GIS Cut Line= 3
      3117869.63      13860620.6       3117028.7      13860541.7
      3116939.22     13860566.44
#Sta/Elev= 30
  4710.3   69.69  4720.3   66.76  4730.3    62.9  4740.3   60.71  4750.3    59.5
  4780.3   61.31  4800.3   61.63  4830.3   58.59  4860.3   56.95  4880.3   54.15
  4890.3   53.21  4943.4   51.08  4967.1      46    4970   44.81  4971.5   27.28
  4980.1   25.45  4998.2   24.28  5019.9   25.58  5023.8   43.93  5033.5   45.72
  5080.3   50.42  5120.3   50.52  5150.3   51.14  5250.3   51.56  5320.3   52.84
  5350.3   52.64  5450.3   54.11  5500.3   53.55  5574.9   57.41  5647.8   58.17
#Mann= 7 ,-1 , 0
  4710.3     .01       0  4880.3     .08       0  4943.4     .04       0
    4970    .045       0  5023.8     .04       0  5080.3     .08       0
  5120.3      .1       0
#XS Ineff= 4 ,-1
                         5177.31  5647.8   58.43 4685.58 4973.86      46
    5020 5172.58      46
Permanent Ineff=
       F       F       F       F
Bank Sta=4970,5023.8
XS Rating Curve= 0
Exp/Cntr=.5,.3

Type RM Length L Ch R = 1 ,17644.00,45.9,46,46.5
BEGIN DESCRIPTION:
SYLVESTER u/s
Upstream Section of Bridge/Culvert/Weir
RASlevee: not a FEMA certified flood control levee
END DESCRIPTION:
XS GIS Cut Line= 2
 3117862.796956313860477.2439122 3117019.376310713860433.3286638
#Sta/Elev= 25
  4710.3   56.45  4761.1    52.7  4867.2   52.01  4918.2   51.68  4943.9   51.51
  4954.6   46.27  4985.4   29.44  4988.2   28.68  4990.1   28.54  4990.6   23.98
  4995.8    23.7  5009.3   24.43  5010.1   28.15  5015.6   28.42  5018.2   29.18
  5018.4   29.18  5049.9   46.06  5059.2   50.55  5059.3   50.55  5174.9   51.81
    5235   52.47  5320.9   52.85  5490.9   53.85  5500.9   53.75  5554.9   56.65
#Mann= 7 ,-1 , 0
  4710.3      .1       0  4867.2     .08       0  4918.2     .04       0
  4943.9    .045       0  5059.2     .04       0  5059.3     .08       0
  5174.9      .1       0
#XS Ineff= 2 , 0
       0    4943   51.58    5061       0   51.32
Permanent Ineff=
       F       F
Bank Sta=4943.9,5059.2
XS Rating Curve= 0
Exp/Cntr=.5,.3

Type RM Length L Ch R = 3 ,17621.00,,,
BEGIN DESCRIPTION:
SYLVESTER
Structure ID: E101-00-00-11
END DESCRIPTION:
Bridge Culvert--1,0,-1,-1, 0
Deck Dist Width WeirC Skew NumUp NumDn MinLoCord MaxHiCord MaxSubmerge Is_Ogee
10,26,2.6,0, 46, 46, , , .95, 0, ,,,
  4710.3  4730.3  4750.3  4761.1  4762.8  4799.3  4867.2  4918.2  4918.9 4941.69
  4941.8 4941.91  4943.9  4952.8 4952.91    4953  4953.1  5049.9  5051.1 5051.19
  5051.3  5051.4  5059.2  5059.3 5062.19  5062.3 5062.41  5122.8  5174.9  5210.3
    5235  5240.3  5320.9  5330.3  5350.3  5370.3  5380.3  5460.3  5480.3  5485.7
  5490.9  5500.9  5530.3  5554.9  5570.3  5590.5
    56.4   54.93   53.46   52.66   52.65   52.41   51.97   51.66   51.66   51.74
   53.94   53.94   53.94   53.94   53.94   53.94   53.94   53.73   53.73   53.73
   53.73   53.73   53.74   53.74   53.75   53.75   51.55   51.34   51.87   52.16
   52.43   52.45   52.81   52.87   52.98    53.1   53.16   53.63   53.75   53.78
   53.81   53.71   55.29   56.61   55.57    54.2
    56.4   54.92   53.45   52.65   52.64    52.4   51.96   51.63   51.62   51.47
   51.47   51.47   51.46    47.1   47.05   48.86   48.86   48.53   48.53   48.53
   46.69   46.73    50.5    50.5   50.53   50.53   50.54   51.19   51.76   52.15
   52.42   52.44    52.8   52.86   52.97   53.09   53.15   53.62   53.74   53.77
    53.8    53.7   55.28    56.6   55.56    54.2
  4710.3  4730.3  4750.3  4761.1  4762.8  4799.3  4867.2  4918.2  4918.9 4941.69
  4941.8 4941.91  4943.9  4952.8 4952.91    4953  4953.1  5049.9  5051.1 5051.19
  5051.3  5051.4  5059.2  5059.3 5062.19  5062.3 5062.41  5122.8  5174.9  5210.3
    5235  5240.3  5320.9  5330.3  5350.3  5370.3  5380.3  5460.3  5480.3  5485.7
  5490.9  5500.9  5530.3  5554.9  5570.3  5590.5
    56.4   54.93   53.46   52.66   52.65   52.41   51.97   51.66   51.66   51.74
   53.94   53.94   53.94   53.94   53.94   53.94   53.94   53.73   53.73   53.73
   53.73   53.73   53.74   53.74   53.75   53.75   51.55   51.34   51.87   52.16
   52.43   52.45   52.81   52.87   52.98    53.1   53.16   53.63   53.75   53.78
   53.81   53.71   55.29   56.61   55.57    54.2
    56.4   54.92   53.45   52.65   52.64    52.4   51.96   51.63   51.62   51.47
   51.47   51.47   51.46    47.1   47.05   48.86   48.86   48.53   48.53   48.53
   46.69   46.73    50.5    50.5   50.53   50.53   50.54   51.19   51.76   52.15
   52.42   52.44    52.8   52.86   52.97   53.09   53.15   53.62   53.74   53.77
    53.8    53.7   55.28    56.6   55.56    54.2
Pier Skew, UpSta & Num, DnSta & Num=  ,4986, 2 ,4986, 2 , 0 , 0 , 0 ,,
       3       3
   27.88    49.7
       3       3
   28.33   50.15
Pier Skew, UpSta & Num, DnSta & Num=  ,5015.6, 2 ,5015.6, 2 , 0 , 0 , 0 ,,
     2.5     2.5
   27.31   49.61
     2.5     2.5
   27.76   50.06
BR Coef= 1 , 1 , 1 ,.9, 0 ,,,.8,0,1.2,0,
WSPro=,,,, 1 ,,,, 0 ,,,, 0 ,,,,-1 ,-1 ,-1 , 0 , 0 , 0 , 0 , 0
BR U #Sta/Elev= 61
  4710.3    56.4  4730.3   54.92  4750.3   53.45  4761.1   52.65  4762.8   52.64
  4799.3    52.4  4867.2   51.96  4918.2   51.63  4918.9   51.62  4932.9   51.53
 4941.69   51.47  4941.8   51.47 4941.91   51.47  4943.9   51.46  4952.8    47.1
 4952.91   47.05    4953      47  4953.1   46.95  4954.6   46.22  4985.4   29.39
    4986   29.22  4988.2   28.63  4990.1   28.49  4990.6   23.93  4995.8   23.65
    4999   23.82  5009.3   24.38  5010.1    28.1  5015.6   28.37  5018.2   29.13
  5018.4   29.13  5049.9   46.01  5051.1   46.59 5051.19   46.63  5051.3   46.69
  5051.4   46.73  5059.2    50.5  5059.3    50.5 5062.19   50.53  5062.3   50.53
 5062.41   50.54  5071.3   50.63  5122.8   51.19  5174.9   51.76  5210.3   52.15
    5235   52.42  5240.3   52.44  5320.9    52.8  5330.3   52.86  5350.3   52.97
  5370.3   53.09  5380.3   53.15  5460.3   53.62  5480.3   53.74  5485.7   53.77
  5490.9    53.8  5500.9    53.7  5530.3   55.28  5554.9    56.6  5570.3   55.56
  5590.5    54.2
BR U #Mann= 7
  4710.3     .05  4762.8     .08  4918.2     .04  4943.9     .03  5059.2     .04
  5059.3     .08  5485.7     .05
BR U Banks=4943.9,5059.2
BR D #Sta/Elev= 61
  4710.3    56.4  4730.3   54.92  4750.3   53.45  4761.1   52.65  4762.8   52.64
  4799.3    52.4  4867.2   51.96  4918.2   51.63  4918.9   51.62  4932.9   51.53
 4941.69   51.47  4941.8   51.47 4941.91   51.47  4943.9   51.46  4952.8    47.1
 4952.91   47.05    4953      47  4953.1   46.95  4954.6   46.22  4985.4   29.39
    4986   29.22  4988.2   28.63  4990.1   28.49  4990.6   23.93  4995.8   23.65
    4999   23.82  5009.3   24.38  5010.1    28.1  5015.6   28.37  5018.2   29.13
  5018.4   29.13  5049.9   46.01  5051.1   46.59 5051.19   46.63  5051.3   46.69
  5051.4   46.73  5059.2    50.5  5059.3    50.5 5062.19   50.53  5062.3   50.53
 5062.41   50.54  5071.3   50.63  5122.8   51.19  5174.9   51.76  5210.3   52.15
    5235   52.42  5240.3   52.44  5320.9    52.8  5330.3   52.86  5350.3   52.97
  5370.3   53.09  5380.3   53.15  5460.3   53.62  5480.3   53.74  5485.7   53.77
  5490.9    53.8  5500.9    53.7  5530.3   55.28  5554.9    56.6  5570.3   55.56
  5590.5    54.2
BR D #Mann= 7
  4710.3     .05  4762.8     .08  4918.2     .04  4943.9     .03  5059.2     .04
  5059.3     .08  5485.7     .05
BR D Banks=4943.9,5059.2
BC Design=,, 0 ,, 0 ,,,,,,
BC HTab HWMax=56.65

Type RM Length L Ch R = 1 ,17598.00,36,33,31.2
BEGIN DESCRIPTION:
SYLVESTER
Downstream Section of Bridge/Culvert/Weir
RASlevee: not a FEMA certified flood control levee
END DESCRIPTION:
XS GIS Cut Line= 2
 3117861.522616213860431.6811585 3117018.080724513860387.1741635
#Sta/Elev= 24
  4710.3   56.45  4761.1    52.7  4932.9   51.58  4943.9   51.51  4954.6   46.27
  4985.4   29.44  4988.2   28.68  4990.1   28.54  4990.6   23.98  4995.8    23.7
  5009.3   24.43  5010.1   28.15  5015.6   28.42  5018.2   29.18  5018.4   29.18
  5049.9   46.06  5059.2   50.55  5059.3   50.55  5122.8   51.24    5235   52.47
  5320.9   52.85  5490.9   53.85  5500.9   53.75  5554.9   56.65
#Mann= 6 ,-1 , 0
  4710.3      .1       0  4932.9     .04       0  4943.9    .045       0
  5059.2     .04       0  5059.3     .08       0  5122.8      .1       0
#XS Ineff= 2 , 0
       0    4943    50.5    5061       0    50.5
Permanent Ineff=
       F       F
Bank Sta=4943.9,5059.2
XS Rating Curve= 0
Exp/Cntr=.5,.3

Type RM Length L Ch R = 1 ,17565.00,793.4,818,848
BEGIN DESCRIPTION:
Cross Section Xsec 14a
END DESCRIPTION:
XS GIS Cut Line= 3
 3117916.129935813860392.1778751      3117916.11     13860392.17
      3116957.26     13860366.61
#Sta/Elev= 30
  4654.9    56.2  4684.9    53.5  4714.9    52.6  4734.9    52.9  4764.9    52.4
  4874.9    51.1  4894.9    50.6  4903.7    49.9  4904.9    49.8  4910.2   50.68
  4917.4   50.72  4920.1   50.09  4929.4   48.97  4956.4   37.18  4968.4   34.49
  4977.1   29.88  4981.1      25  4981.7   24.75  5002.1   23.79  5014.2   24.08
    5019   25.36  5038.6   41.16  5055.8   44.31  5082.3   49.85  5204.9    52.7
  5354.9    52.6  5554.9      54  5574.9    53.4  5594.9    53.8  5614.1    54.7
#Mann= 6 ,-1 , 0
  4654.9      .1       0  4874.9     .08       0  4903.7     .04       0
  4929.4    .045       0  5082.3     .08       0  5204.9      .1       0
Bank Sta=4929.4,5082.3
XS Rating Curve= 0
Exp/Cntr=.3,.1

Type RM Length L Ch R = 1 ,16747.00,228.7,337,424.6
BEGIN DESCRIPTION:
Cross Section x14
END DESCRIPTION:
XS GIS Cut Line= 2
      3118314.68     13859701.63      3116647.06     13859404.66
#Sta/Elev= 30
  4261.5    55.8  4341.5    54.7  4391.5    52.4  4461.5    53.5  4481.5    52.7
  4661.5      53  4751.5    50.8  4761.5    51.6    4885   48.28  4908.7    46.9
  4921.4    43.4  4939.6   34.17  4972.3   33.09  4976.7   28.73    4983   26.23
  4984.5   24.71  5012.7   23.49  5018.7   26.54  5033.7   37.49  5044.3   41.62
  5053.5   48.77  5072.4   49.87  5161.5      51  5341.5    51.1  5381.5    48.7
  5391.5    48.8  5421.5      52  5531.5    52.3  5561.5    53.5  5955.4    54.7
#Mann= 6 ,-1 , 0
  4261.5      .1       0  4761.5     .08       0    4885     .04       0
  4908.7     .05       0  5053.5     .08       0  5161.5      .1       0
#XS Ineff= 1 ,-1
 4321.99 4541.84   53.38
Permanent Ineff=
       F
Bank Sta=4908.7,5053.5
XS Rating Curve= 0
Exp/Cntr=.3,.1

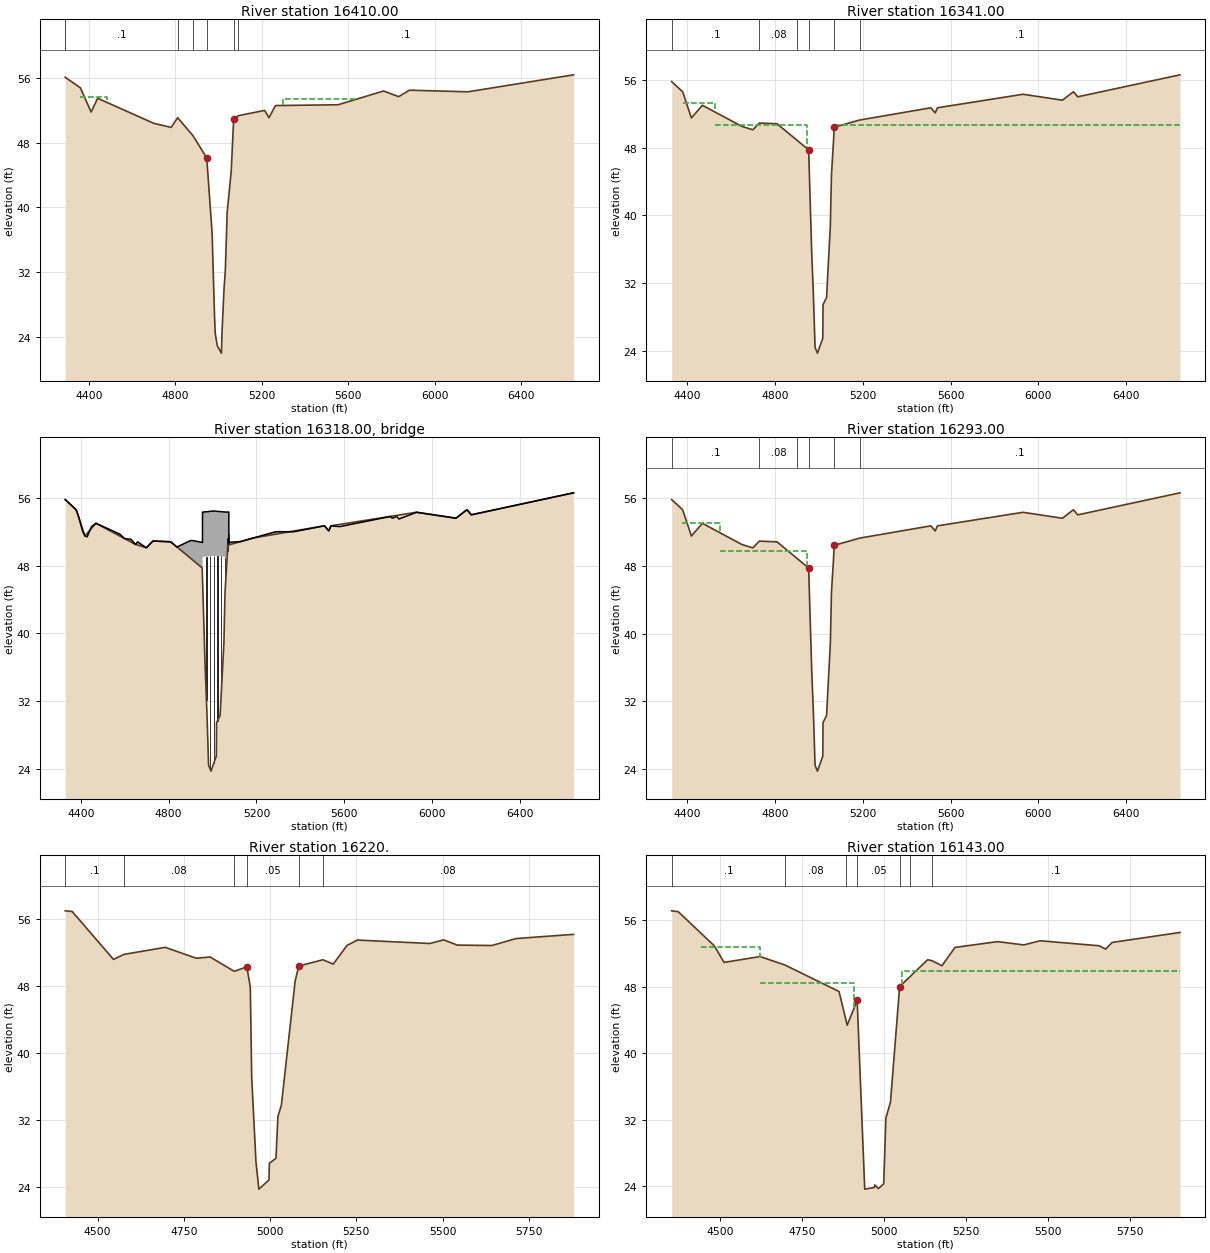
Type RM Length L Ch R = 1 ,16410.00,63.6,69,83.6
BEGIN DESCRIPTION:
Cross Section Xsec 13b
END DESCRIPTION:
XS GIS Cut Line= 4
      3118336.46     13859586.65      3117789.04     13859375.54
      3117660.14     13859166.45      3116330.19     13858433.53
#Sta/Elev= 30
  4290.6    56.1  4360.6    54.8  4410.6    51.8  4440.6    53.5  4700.6    50.4
  4780.6    49.9  4810.6    51.1  4882.2   48.85  4945.2   46.12  4970.1   36.79
    4981   26.71  4984.5   24.41    4994    22.9  5013.1   21.99  5015.5    24.4
  5025.1   29.91  5031.2   32.27  5039.7   39.41  5058.4   44.49  5069.6   50.88
  5091.5   51.35  5212.9      52  5232.9    51.1  5262.9    52.6  5552.9    52.7
  5762.9    54.4  5832.9    53.7  5882.9    54.5  6152.9    54.3  6641.5    56.4
#Mann= 7 ,-1 , 0
  4290.6      .1       0  4290.6      .1       0  4810.6     .08       0
  4882.2     .04       0  4945.2     .04       0  5069.6     .08       0
  5091.5      .1       0
#XS Ineff= 2 ,-1
 4359.34 4482.27   53.68 5297.87  5638.3   53.38
Permanent Ineff=
       F       F
Bank Sta=4945.2,5069.6
XS Rating Curve= 0
Exp/Cntr=.5,.3

Type RM Length L Ch R = 1 ,16341.00,36,48,37.7
BEGIN DESCRIPTION:
ENID ROAD u/s
Upstream Section of Bridge/Culvert/Weir
END DESCRIPTION:
XS GIS Cut Line= 4
 3118363.520745513859540.5046238      3117809.68     13859315.06
       3117763.2     13859160.83 3116403.352786313858399.3497868
#Sta/Elev= 30
  4328.4   55.83  4378.4   54.63  4418.4   51.53  4468.4   53.03  4648.4   50.53
  4698.4   50.13  4728.4   50.93  4808.8   50.84  4900.9   48.87  4952.9   47.75
  4966.8   35.71  4974.2   30.87  4982.2   24.39    4993   23.71  5017.5   25.48
  5018.5   29.44  5034.6   30.29    5052   38.88    5057   44.84  5066.3    48.8
  5069.5   50.43  5184.9   51.28    5510   52.73    5530   52.13    5540   52.73
    5930   54.33    6110   53.63    6160   54.63    6180   54.03    6646   56.63
#Mann= 6 ,-1 , 0
  4328.4      .1       0  4728.4     .08       0  4900.9     .04       0
  4952.9     .06       0  5066.3     .08       0  5184.9      .1       0
#XS Ineff= 3 ,-1
 4378.25 4527.19   53.24 4527.19  4944.5   50.75  5076.5    6646   50.75
Permanent Ineff=
       F       F       F
Bank Sta=4952.9,5069.5
XS Rating Curve= 0
Exp/Cntr=.5,.3

Type RM Length L Ch R = 3 ,16318.00,,,
BEGIN DESCRIPTION:
ENID ROAD
Structure ID: E101-00-00-10
END DESCRIPTION:
Bridge Culvert--1,0,-1,-1, 0
Deck Dist Width WeirC Skew NumUp NumDn MinLoCord MaxHiCord MaxSubmerge Is_Ogee
10,26,2.6,0, 91, 91, , , .95, 0, ,,,
  4328.4  4377.5  4378.4  4388.4  4407.5  4408.4  4417.5  4418.4  4428.4  4447.5
  4448.4  4457.5  4467.5  4468.4  4487.5  4507.5  4578.4  4598.4  4628.4  4648.4
  4658.4  4667.5  4687.5  4698.4  4728.4  4737.5  4807.5  4808.8  4837.5  4900.9
  4913.1  4952.9 4954.29  4954.4 4954.51  4954.8 4954.91    4955  4955.1  4966.8
  4974.2  4982.2  4983.9    4993  5000.7  5006.5  5006.9  5017.5  5018.5  5034.6
  5040.7    5052    5057  5061.2  5062.4  5066.3  5069.5 5074.29  5074.4 5074.51
  5074.9  5075.7 5075.79  5075.9  5128.8  5184.9  5239.4  5250.8  5287.6    5370
  5380.8  5410.8  5470.8    5508    5510    5530    5540    5580  5610.8  5630.8
  5650.8  5806.9    5810    5820    5840    5850    5930    6110    6160    6180
    6646
   55.83   54.65   54.63   53.93   52.12   52.03   51.57   51.53   51.43   52.58
   52.63   52.81   53.01   53.03    52.8   52.57   51.73   51.23   51.13   50.53
   50.83   50.67   50.32   50.13   50.93   50.92   50.84   50.84   50.22   50.99
   50.97   50.76   50.75   54.35   54.35   54.35   54.35   54.35   54.35   54.38
    54.4   54.42   54.42   54.45   54.47   54.48   54.48   54.45   54.45   54.41
    54.4   54.37   54.36   54.35   54.35   54.35   54.36   54.36   54.36   50.76
   50.76   50.76   50.76   50.77   50.87   51.28   51.68   51.76   52.03   52.03
   52.08   52.23   52.53   52.72   52.73   52.13   52.73   52.63   52.79    52.9
      53   53.81   53.83   53.63   53.83   53.53   54.33   53.63   54.63   54.03
   56.63
                                                                                
                                                                                
                                                                                
                                                           49.05   49.05   49.08
    49.1   49.12   49.12   49.15   49.17   49.18   49.18   49.15   49.15   49.11
    49.1   49.07   49.06   49.05   49.05   49.07
                                                                                
                                                                                
                                                                                
        
  4328.4  4377.5  4378.4  4388.4  4407.5  4408.4  4417.5  4418.4  4428.4  4447.5
  4448.4  4457.5  4467.5  4468.4  4487.5  4507.5  4578.4  4598.4  4628.4  4648.4
  4658.4  4667.5  4687.5  4698.4  4728.4  4737.5  4807.5  4808.8  4837.5  4900.9
  4913.1  4952.9 4954.29  4954.4 4954.51  4954.8 4954.91    4955  4955.1  4966.8
  4974.2  4982.2  4983.9    4993  5000.7  5006.5  5006.9  5017.5  5018.5  5034.6
  5040.7    5052    5057  5061.2  5062.4  5066.3  5066.4 5074.29  5074.4 5074.51
  5074.9  5075.7 5075.79  5075.9  5128.8  5184.9  5239.4  5250.8  5287.6    5370
  5380.8  5410.8  5470.8    5508    5510    5530    5540    5580  5610.8  5630.8
  5650.8  5806.9    5810    5820    5840    5850    5930    6110    6160    6180
    6646
    56.1    56.3   56.28   56.05    55.6   55.55      55    54.9   53.84   52.86
   52.91   53.09   53.29   53.31   53.08    53.3    52.5   52.28   51.94   51.71
    51.6    51.5    50.6   50.95   51.91    52.2   51.12   51.12    50.5   50.99
   50.97   50.76   50.75   54.35   54.35   54.35   54.35   54.35   54.35   54.38
    54.4   54.42   54.42   54.45   54.47   54.48   54.48   54.45   54.45   54.41
    54.4   54.37   54.36   54.35   54.35   54.35   54.36   54.36   54.36   50.76
   50.76   50.76   50.76   50.77   51.15   51.56   51.98    53.4    53.4    53.4
    53.4    52.7    53.5   53.39   53.39   53.33    53.3   53.19    53.1   53.18
   53.28   54.09    54.1    53.9    54.1    53.8    54.6    53.9    54.9    54.3
    56.9
                                                                                
                                                                                
                                                                                
                                                           49.05   49.05   49.08
    49.1   49.12   49.12   49.15   49.17   49.18   49.18   49.15   49.15   49.11
    49.1   49.07   49.06   49.05   49.05   49.07
                                                                                
                                                                                
                                                                                
        
Pier Skew, UpSta & Num, DnSta & Num=  ,4972.2, 2 ,4972.2, 2 , 0 , 0 , 0 ,,
       1       1
   31.12    50.1
       1       1
   30.92    49.9
Pier Skew, UpSta & Num, DnSta & Num=  ,4989.3, 2 ,4989.3, 2 , 0 , 0 , 0 ,,
       1       1
    23.1   50.14
       1       1
    22.9   49.94
Pier Skew, UpSta & Num, DnSta & Num=  ,5006.1, 2 ,5006.1, 2 , 0 , 0 , 0 ,,
       1       1
   23.72   50.18
       1       1
   23.52   49.98
Pier Skew, UpSta & Num, DnSta & Num=  ,5022.9, 2 ,5022.9, 2 , 0 , 0 , 0 ,,
       1       1
   28.92   50.14
       1       1
   28.72   49.94
Pier Skew, UpSta & Num, DnSta & Num=  ,5040, 2 ,5040, 2 , 0 , 0 , 0 ,,
       1       1
   31.87    50.1
       1       1
   31.67    49.9
Pier Skew, UpSta & Num, DnSta & Num=  ,5057.4, 2 ,5057.4, 2 , 0 , 0 , 0 ,,
       1       1
   43.99   50.06
       1       1
   43.79   49.86
Pier Skew, UpSta & Num, DnSta & Num=  ,5068.2, 2 ,5068.2, 2 , 0 , 0 , 0 ,,
       1       1
   48.78   51.29
       1       1
   48.58   51.09
Pier Skew, UpSta & Num, DnSta & Num=  ,5074.2, 2 ,5074.2, 2 , 0 , 0 , 0 ,,
       1       1
   49.74   51.74
       1       1
   49.54   51.54
BR Coef= 1 , 1 , 1 ,1.25, 0 ,,,.8,0,2,0,
WSPro=,,,, 1 ,,,, 0 ,,,, 0 ,,,,-1 ,-1 ,-1 , 0 , 0 , 0 , 0 , 0
BC Design=,, 0 ,, 0 ,,,,,,
BC HTab HWMax=56.63

Type RM Length L Ch R = 1 ,16293.00,109.1,73,21.4
BEGIN DESCRIPTION:
ENID ROAD
Downstream Section of Bridge/Culvert/Weir
END DESCRIPTION:
XS GIS Cut Line= 4
      3118396.86     13859515.96      3117852.46     13859294.46
      3117808.09     13859143.93      3116426.12      13858369.7
#Sta/Elev= 30
  4328.4   55.83  4378.4   54.63  4418.4   51.53  4468.4   53.03  4648.4   50.53
  4698.4   50.13  4728.4   50.93  4808.8   50.84  4900.9   48.87  4952.9   47.75
  4966.8   35.77  4974.2   30.93  4982.2   24.45    4993   23.77  5017.5   25.54
  5018.5    29.5  5034.6   30.35    5052   38.94    5057    44.9  5066.3    48.8
  5069.5   50.43  5184.9   51.28    5510   52.73    5530   52.13    5540   52.73
    5930   54.33    6110   53.63    6160   54.63    6180   54.03    6646   56.63
#Mann= 6 ,-1 , 0
  4328.4      .1       0  4728.4     .08       0  4900.9     .04       0
  4952.9     .06       0  5066.3     .08       0  5184.9      .1       0
#XS Ineff= 3 ,-1
 4373.52 4550.83   53.09 4550.83  4944.5    49.8  5076.5    6646    49.8
Permanent Ineff=
       F       F       F
Bank Sta=4952.9,5069.5
XS Rating Curve= 0
Exp/Cntr=.5,.3

Type RM Length L Ch R = 1 ,16220.  ,144.3,77,12.6
BEGIN DESCRIPTION:
struct 09 u/s of Link st-XS4
END DESCRIPTION:
XS GIS Cut Line= 4
      3118388.91     13859492.17      3117947.78     13859223.31
      3117828.65     13859131.54      3117125.09      13858737.1
#Sta/Elev= 30
  4406.1   56.93  4426.1   56.86  4546.1   51.13  4576.1   51.73  4696.1   52.57
  4786.1   51.27  4826.1   51.42  4896.1   49.71  4932.7   50.24  4942.7   47.81
 4946.75   37.08 4958.98   27.03 4967.55   23.71 4996.75    24.8 4997.94    26.8
 5017.06   27.39 5022.73   32.38  5032.7   33.71  5072.7   48.55  5083.1   50.34
  5153.1   51.09  5183.1   50.57  5223.1    52.8  5253.1   53.44  5463.1   53.03
  5503.1   53.46  5543.1   52.84  5643.1   52.79  5713.1   53.62  5879.7   54.12
#Mann= 6 ,-1 , 0
  4406.1      .1       0  4576.1     .08       0  4896.1     .06       0
  4932.7     .05       0  5083.1     .05       0  5153.1     .08       0
Bank Sta=4932.7,5083.1
XS Rating Curve= 0
Exp/Cntr=.5,.3

Type RM Length L Ch R = 1 ,16143.00,88,69,66.6
BEGIN DESCRIPTION:
LINK ROAD (deck skewed 35°, overbanks not skewed) u/s
Upstream Section of Bridge/Culvert/Weir
END DESCRIPTION:
XS GIS Cut Line= 4
 3118397.6053181 13859478.017799      3118076.23     13859095.75
      3117833.64     13859120.43 3117129.247177713858721.8162894
#Sta/Elev= 30
    4351   57.11    4371   57.01    4481   52.91    4511   50.91    4621   51.61
  4696.7    50.6  4862.2   47.41  4883.3   43.98  4887.1   43.36  4917.6   46.33
  4940.7   23.654969.698   23.844971.582   24.154982.067   23.714998.614   24.28
 5005.25   32.195019.338   34.125047.354      485077.454   49.145132.854   51.23
5146.454   51.115176.454   50.515216.454   52.715346.454   53.415426.454   53.01
5476.454   53.515656.454   52.915676.454   52.515696.454   53.315903.654   54.51
#Mann= 7 ,-1 , 0
    4351      .1       0  4696.7     .08       0  4883.3     .04       0
  4917.6     .05       05047.354     .04       05077.454     .08       0
5146.454      .1       0
#XS Ineff= 3 ,-1
 4441.13 4619.86   52.795053.3325903.654   49.91 4619.864908.583   48.43
Permanent Ineff=
       F       F       F
Bank Sta=4917.6,5047.354
XS Rating Curve= 0
Skew Angle= 35
Exp/Cntr=.5,.3

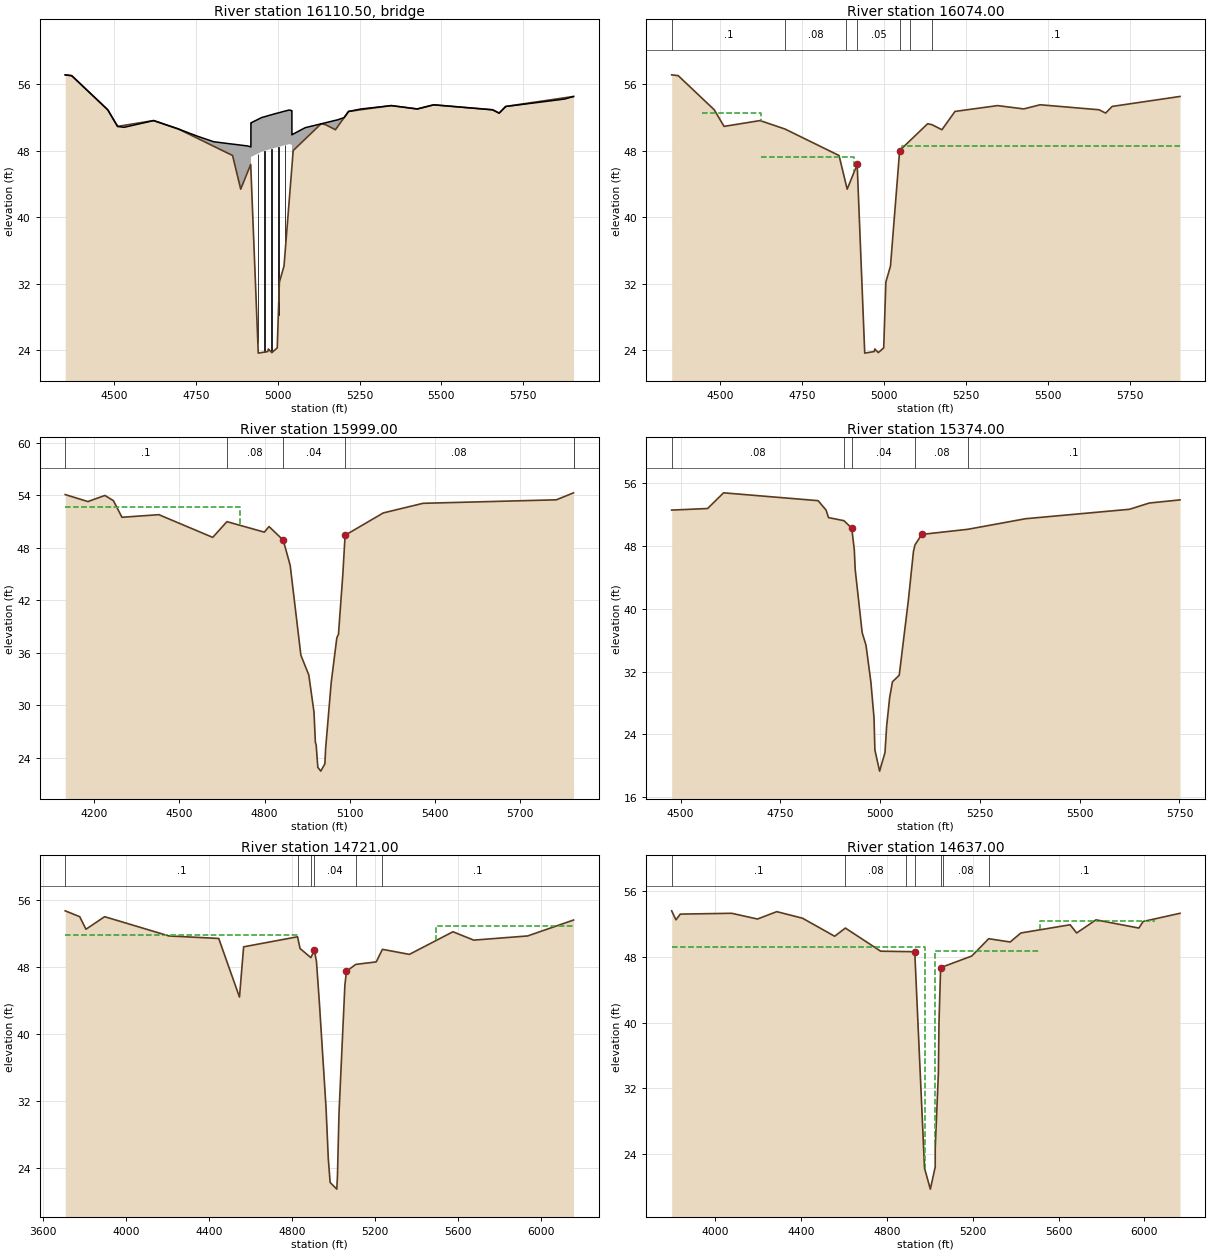
Type RM Length L Ch R = 3 ,16110.50,,,
BEGIN DESCRIPTION:
LINK ROAD (deck skewed 35°, overbanks not skewed)
Structure ID: E101-00-00-09
END DESCRIPTION:
Bridge Culvert--1,0,-1,-1, 0
Deck Dist Width WeirC Skew NumUp NumDn MinLoCord MaxHiCord MaxSubmerge Is_Ogee
10,45,2.6,35, 64, 64, , , .95, 0, ,,,
    4351    4371    4481    4511    4531  4596.7    4621  4696.6  4696.7    4752
  4804.1  4851.4  4862.2  4883.3  4887.1  4907.9  4917.64918.1654918.2554918.345
4918.4194918.5094918.583  4940.74943.1584951.5134969.698 4969.784971.5824982.067
 4993.294998.614 5005.255019.3385035.1495043.3325043.4225043.5125043.5785043.668
 5043.755047.3545077.4545084.4545132.8545146.4545176.4545183.2545203.2545213.254
5216.4545223.2545253.2545343.2545346.4545351.2545426.4545476.4545548.1545656.454
5676.4545696.4545876.4545903.654
    57.1      57    52.9    50.9    50.8   51.39   51.61    50.6    50.6   49.77
   49.07   48.83   48.78   48.68   48.66   48.56   48.45   48.44   51.34   51.34
   51.34   51.34   51.34   51.77   51.82   51.98   52.18   52.19   52.21   52.32
   52.45    52.5   52.57   52.72   52.88    52.8    52.8    49.9    49.9    49.9
    49.9   49.99   50.62   50.76   51.22   51.35   51.64    51.7   51.98   52.53
   52.71   52.75      53   53.39   53.41   53.39      53    53.5   53.26    52.9
    52.5    53.3    54.2    54.5
                                                                                
                                                                   45.68   45.59
   45.52   45.43   47.24   47.67   47.72   47.88   48.08   48.09   48.11   48.22
   48.35    48.4   48.47   48.62   48.78    48.7    48.7    48.7    48.7   46.16
    46.2   47.99   49.13   49.39   51.22    51.1    50.5   50.87   51.97   52.52
    52.7   52.74    52.9   53.38    53.4   53.38      53    53.5   53.26    52.9
    52.5    53.3    54.2    54.5
    4351    4371    4481    4511    4531  4596.7    4621  4696.6  4696.7    4752
  4804.1  4851.4  4862.2  4883.3  4887.1  4907.9  4917.64918.1654918.2554918.345
4918.4194918.5094918.583  4940.74943.1584951.5134969.698 4969.784971.5824982.067
 4993.294998.614 5005.255019.3385035.1495043.3325043.4225043.5125043.5785043.668
 5043.755047.3545077.4545084.4545132.8545146.4545176.4545183.2545203.2545213.254
5216.4545223.2545253.2545343.2545346.4545351.2545426.4545476.4545548.1545656.454
5676.4545696.4545876.4545903.654
    57.1      57    52.9    50.9    50.8   51.39   51.61    50.6    50.6   49.77
   49.07   48.83   48.78   48.68   48.66   48.56   48.45   48.44   51.34   51.34
   51.34   51.34   51.34   51.77   51.82   51.98   52.18   52.19   52.21   52.32
   52.45    52.5   52.57   52.72   52.88    52.8    52.8    49.9    49.9    49.9
    49.9   49.99   50.62   50.76   51.22   51.35   51.64    51.7   51.98   52.53
   52.71   52.75      53   53.39   53.41   53.39      53    53.5   53.26    52.9
    52.5    53.3    54.2    54.5
                                                                                
                                                                   45.68   45.59
   45.52   45.43   47.24   47.67   47.72   47.88   48.08   48.09   48.11   48.22
   48.35    48.4   48.47   48.62   48.78    48.7    48.7    48.7    48.7   46.16
    46.2   47.99   49.13   49.39   51.22    51.1    50.5   50.87   51.97   52.52
    52.7   52.74    52.9   53.38    53.4   53.38      53    53.5   53.26    52.9
    52.5    53.3    54.2    54.5
Pier Skew, UpSta & Num, DnSta & Num=  ,4939.414, 2 ,4939.414, 2 , 0 , 0 , 0 ,,
     1.4     1.4
   40.01   48.33
     1.4     1.4
   40.01   48.33
Pier Skew, UpSta & Num, DnSta & Num=  ,4960.245, 2 ,4960.245, 2 , 0 , 0 , 0 ,,
     1.4     1.4
   22.65   48.73
     1.4     1.4
   21.41   48.73
Pier Skew, UpSta & Num, DnSta & Num=  ,4981.076, 2 ,4981.076, 2 , 0 , 0 , 0 ,,
     1.4     1.4
   22.79   49.03
     1.4     1.4
   22.79   49.03
Pier Skew, UpSta & Num, DnSta & Num=  ,5001.907, 2 ,5001.907, 2 , 0 , 0 , 0 ,,
     1.4     1.4
   22.78   49.26
     1.4     1.4
   22.78   49.26
Pier Skew, UpSta & Num, DnSta & Num=  ,5022.738, 2 ,5022.738, 2 , 0 , 0 , 0 ,,
     1.4     1.4
   30.89   49.48
     1.4     1.4
   30.89   49.48
BR Coef= 1 , 1 , 1 ,1.25, 0 ,,,.8,0,2,0,
WSPro=,,,, 1 ,,,, 0 ,,,, 0 ,,,,-1 ,-1 ,-1 , 0 , 0 , 0 , 0 , 0
BC Design=,, 0 ,, 0 ,,,,,,
BC HTab HWMax=57.11

Type RM Length L Ch R = 1 ,16074.00,41.1,75,108
BEGIN DESCRIPTION:
LINK ROAD (deck skewed 35°, overbanks not skewed)
Downstream Section of Bridge/Culvert/Weir
END DESCRIPTION:
XS GIS Cut Line= 4
 3118424.891235313859415.2709922      3118103.41     13859032.93
      3117856.01      13859058.1 3117149.055937413858674.3285778
#Sta/Elev= 30
    4351   57.11    4371   57.01    4481   52.91    4511   50.91    4621   51.61
  4696.7    50.6  4862.2   47.41  4883.3   43.98  4887.1   43.36  4917.6   46.33
  4940.7   23.654969.698   23.844971.582   24.154982.067   23.714998.614   24.28
 5005.25   32.195019.338   34.125047.354      485077.454   49.145132.854   51.23
5146.454   51.115176.454   50.515216.454   52.715346.454   53.415426.454   53.01
5476.454   53.515656.454   52.915676.454   52.515696.454   53.315903.654   54.51
#Mann= 7 ,-1 , 0
    4351      .1       0  4696.7     .08       0  4883.3     .04       0
  4917.6     .05       05047.354     .04       05077.454     .08       0
5146.454      .1       0
#XS Ineff= 3 ,-1
 4443.97 4622.69    52.55053.3325903.654    48.6 4622.694908.583    47.2
Permanent Ineff=
       F       F       F
Bank Sta=4917.6,5047.354
XS Rating Curve= 0
Skew Angle= 35
Exp/Cntr=.5,.3

Type RM Length L Ch R = 1 ,15999.00,598.6,625,582
BEGIN DESCRIPTION:
Cross Section Xsec 13a
RASlevee: not a FEMA certified flood control levee
END DESCRIPTION:
XS GIS Cut Line= 4
       3118869.8     13858838.69      3118191.75     13859020.08
      3117808.78     13858950.32      3117180.57     13858640.38
#Sta/Elev= 30
  4097.5    54.1  4177.5    53.3  4237.5      54  4267.5    53.4  4297.5    51.5
  4427.5    51.8  4617.5    49.2  4667.5      51  4799.4    49.8  4815.9   50.44
  4865.9   48.89  4890.5      46  4928.2   35.71  4956.1   33.45  4974.4    29.2
  4979.3   25.73  4982.1   25.45  4987.9   22.88  4998.3   22.44  5012.8   23.28
  5015.3   24.99    5035   32.56  5054.9   37.71  5060.7   38.11  5076.1   44.99
    5084   49.44  5218.7      52  5358.7    53.1  5828.7    53.5  5889.2    54.3
#Mann= 6 ,-1 , 0
  4097.5      .1       0  4667.5     .08       0  4865.9     .04       0
    5084     .08       0  5889.2     .08       0  5889.2      .1       0
#XS Ineff= 2 , 0
         4713.95   52.68
Permanent Ineff=
       F       F
Bank Sta=4865.9,5084
XS Rating Curve= 0
Exp/Cntr=.3,.1

Type RM Length L Ch R = 1 ,15374.00,645.7,653,660.6
BEGIN DESCRIPTION:
Cross Section x13
END DESCRIPTION:
XS GIS Cut Line= 3
      3118581.87     13858819.89      3118581.94     13858523.01
      3117616.71      13858372.9
#Sta/Elev= 30
  4477.7    52.6  4567.7    52.8  4607.7    54.8  4844.6    53.8  4864.6    52.6
  4870.7   51.64  4909.3   51.25  4928.9    50.3  4935.3   47.56  4937.6   45.01
    4955   36.98  4964.6   35.38  4976.9   30.66  4984.7   26.13  4986.9   22.02
  4998.7   19.32  5012.2   21.69  5016.4   25.08  5023.9    28.7  5030.9   30.71
  5047.9   31.55  5070.8   41.11  5083.6   47.36  5087.5   48.18  5104.6    49.5
  5219.7   50.15  5364.6    51.5  5624.6    52.7  5674.6    53.5  5751.4    53.9
#Mann= 5 ,-1 , 0
  4477.7     .08       0  4909.3     .04       0  4928.9     .04       0
  5087.5     .08       0  5219.7      .1       0
Bank Sta=4928.9,5104.6
XS Rating Curve= 0
Exp/Cntr=.3,.1

Type RM Length L Ch R = 1 ,14721.00,91.8,84,65.4
BEGIN DESCRIPTION:
Cross Section Xsec 12b
END DESCRIPTION:
XS GIS Cut Line= 3
      3119699.62      13858166.1      3118305.11     13857810.73
      3117299.58     13857704.31
#Sta/Elev= 30
    3706    54.7    3776      54    3806    52.5    3896      54    4206    51.7
    4446    51.4    4546    44.4    4566    50.4    4826    51.6    4838    50.2
  4890.1   49.11  4906.8   49.97  4917.2   48.64  4931.3   43.67  4963.2   31.22
  4974.1   25.13    4983   22.26  5015.1   21.46  5018.4   23.11  5025.9   30.65
  5054.1   45.83  5061.6   47.47    5106    48.3  5205.1    48.6  5235.1    50.1
  5365.1    49.5  5575.1    52.2  5675.1    51.2  5935.1    51.7  6156.2    53.6
#Mann= 6 ,-1 , 0
    3706      .1       0    4826      .1       0  4890.1     .04       0
  4906.8     .04       0    5106      .1       0  5235.1      .1       0
#XS Ineff= 2 , 0
         4823.88   51.78 5492.91           52.94
Permanent Ineff=
       F       F
Bank Sta=4906.8,5061.6
XS Rating Curve= 0
Exp/Cntr=.5,.3

Type RM Length L Ch R = 1 ,14637.00,163.2,155,145.9
BEGIN DESCRIPTION:
CAVALCADE u/s
Upstream Section of Bridge/Culvert/Weir
END DESCRIPTION:
XS GIS Cut Line= 4
 3119666.597631713857753.6433492      3118628.58     13857784.77
      3118331.49     13857747.14 3117300.444657813857701.6690935
#Sta/Elev= 30
  3796.2   53.64  3816.2   52.54  3836.2   53.24  4076.2   53.34  4196.2   52.64
  4286.2   53.54  4406.2   52.74  4556.2   50.54    4606   51.54  4770.6   48.72
    4890   48.67  4929.5   48.65  4975.1   22.26  5002.2   19.71  5024.9   22.42
    5025   24.76  5039.7   33.84  5042.6   40.11  5050.2   46.72  5059.9   46.81
  5195.3   48.13  5274.4   50.24  5374.4   49.84  5424.4   50.94    5654   51.94
  5684.4   50.94  5774.4   52.54  5974.4   51.54  5994.4   52.34  6166.2   53.34
#Mann= 7 ,-1 , 0
  3796.2      .1       0    4606     .08       0    4890     .04       0
  4929.5     .04       0  5050.2     .04       0  5059.9     .08       0
  5274.4      .1       0
#XS Ineff= 3 ,-1
 5514.18 6050.83   52.34  3796.2  4978.5   49.23  5025.5 5514.18   48.72
Permanent Ineff=
       F       F       F
Bank Sta=4929.5,5050.2
XS Rating Curve= 0
Exp/Cntr=.5,.3