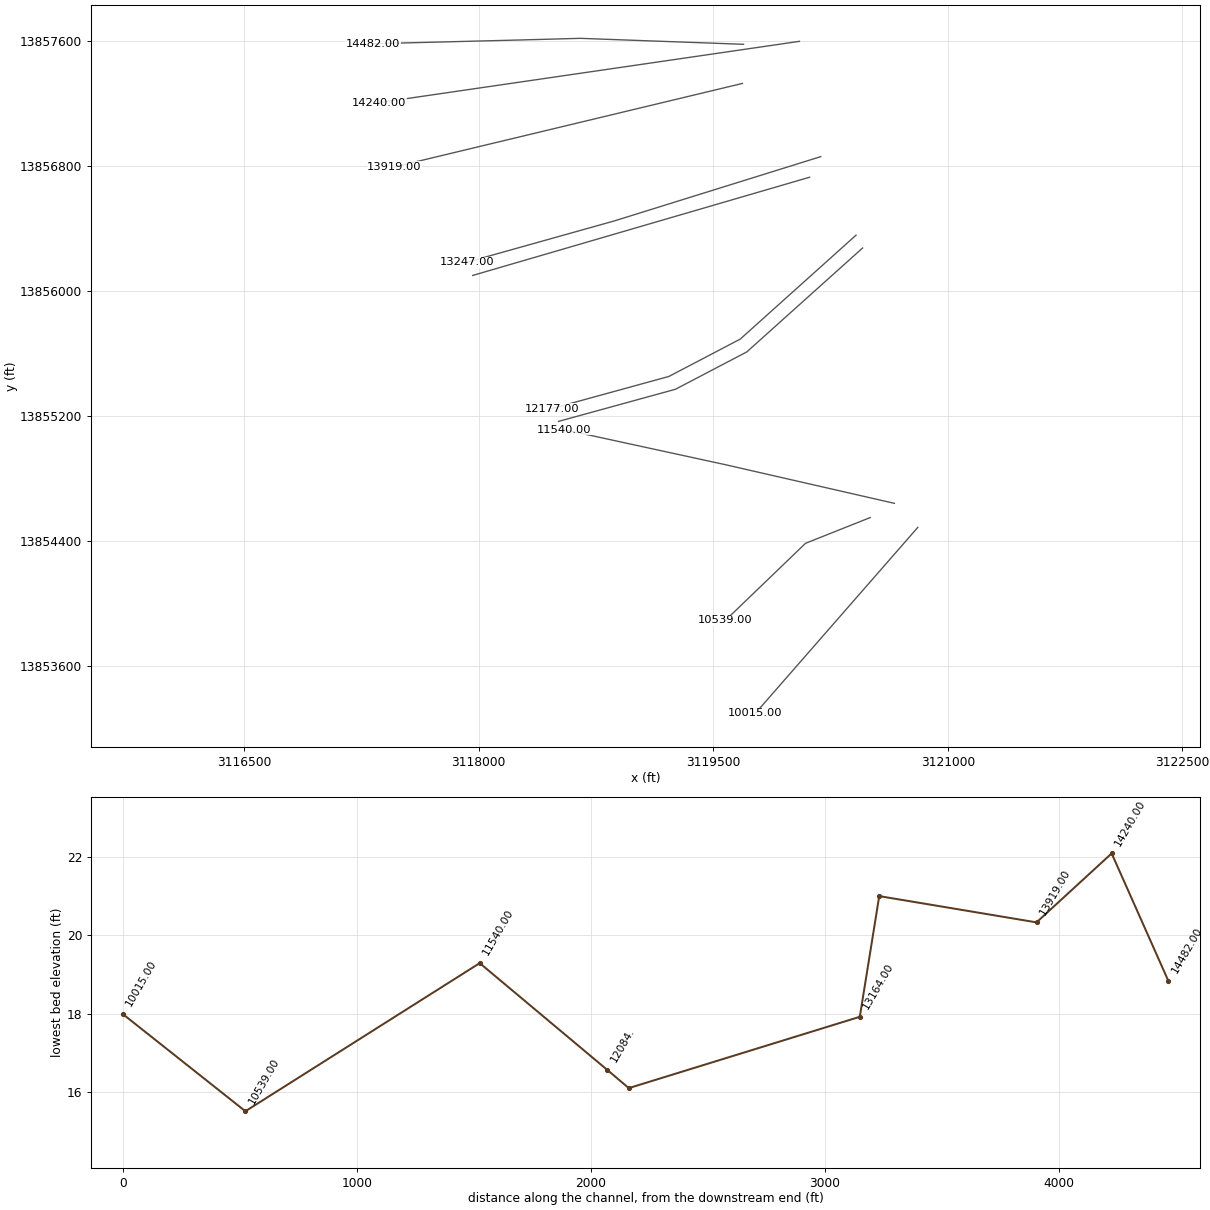
HEC-RAS study E101_00_00.prj: E101-00-00

--- E101_00_00.g01 (geometry) --- (continued)

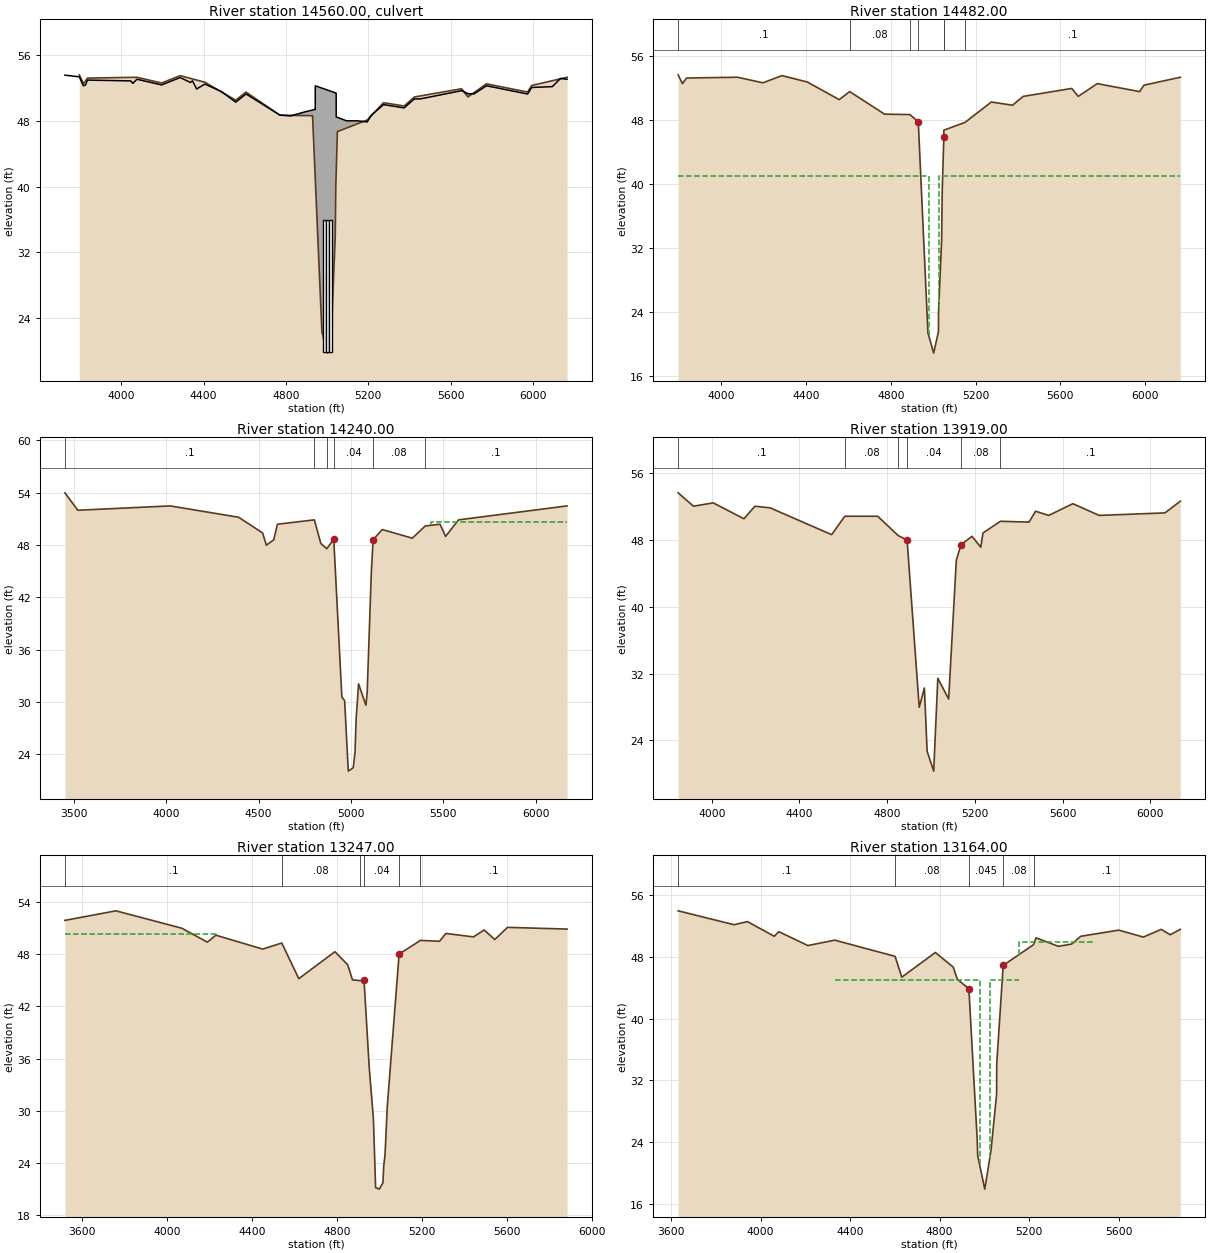
Type RM Length L Ch R = 2 ,14560.00,,,
BEGIN DESCRIPTION:
CAVALCADE
Structure ID: E101-00-00-08
END DESCRIPTION:
Bridge Culvert--1,0,-1,-1, 0
Deck Dist Width WeirC Skew NumUp NumDn MinLoCord MaxHiCord MaxSubmerge Is_Ogee
10,134,2.6,0, 51, 51, , , .95, 0, ,,,
  3726.2  3796.2  3816.2  3826.2  3836.2  4046.2  4056.2  4076.2  4196.2  4286.2
  4336.2  4346.2  4366.2  4406.2  4486.2  4556.2  4606.2  4770.6  4822.4  4887.6
  4940.9 4942.69  4942.8  4951.1  4975.1  5001.1  5002.2  5024.9    5025  5039.7
  5042.6  5044.4 5044.51  5050.2  5093.8  5150.1  5195.3  5214.4  5274.4  5374.4
  5424.4  5454.4    5654  5684.4  5714.4  5774.4  5974.4  5994.4  6094.4  6134.4
  6166.2
    53.6    53.4    52.3    52.4      53    52.9    52.6    53.1   52.41   53.31
   52.71   52.91   51.91   52.51   51.61   50.31   51.31   48.74   48.63   49.09
   49.42    49.4    52.3   52.23   52.02   51.79   51.78   51.58   51.58   51.45
   51.42   51.41   48.51   48.46   48.04   48.03    47.9   48.71   50.01   49.61
   50.71   50.71   51.71   51.34   51.32   52.31    51.3    52.1    52.2    53.2
    53.1
    53.6    53.4    52.3    52.4      53    52.9    52.6    53.1    52.4    53.3
    52.7    52.9    51.9    52.5    51.6    50.3    51.3   48.48   48.46   48.43
   41.71   40.66    40.6   35.72   22.02   19.84   19.47   22.18   24.52    33.6
   39.87   41.44   41.53   46.48    46.9   46.69   47.89    48.7      50    49.6
    50.7    50.7    51.7    50.7    51.3    52.3    51.3    52.1    52.2    53.2
    53.1
  3726.2  3796.2  3816.2  3826.2  3836.2  4046.2  4056.2  4076.2  4196.2  4286.2
  4336.2  4346.2  4366.2  4406.2  4486.2  4556.2  4606.2  4770.6  4822.4  4887.6
  4940.9 4942.69  4942.8  4951.1  4975.1  5001.1  5002.2  5024.9    5025  5039.7
  5042.6  5044.4 5044.51  5050.2  5093.8  5150.1  5195.3  5214.4  5274.4  5374.4
  5424.4  5454.4    5654  5684.4  5714.4  5774.4  5974.4  5994.4  6094.4  6134.4
  6166.2
    53.6    53.4    52.3    52.4      53    52.9    52.6    53.1   52.41   53.31
   52.71   52.91   51.91   52.51   51.61   50.31   51.31   48.74   48.63   49.09
   49.42    49.4    52.3   52.23   52.02   51.79   51.78   51.58   51.58   51.45
   51.42   51.41   48.51   48.46   48.04   48.03    47.9   48.71   50.01   49.61
   50.71   50.71   51.71   51.34   51.32   52.31    51.3    52.1    52.2    53.2
    53.1
   52.84   52.64   51.54   51.64   52.24   52.14   51.84   52.34   51.64   52.54
   51.94   52.14   51.14   51.74   50.84   49.54   50.54   47.72    47.7   47.67
   40.95    39.9   39.84   34.96   21.26   19.08   18.71   21.42   23.76   32.84
   39.11   40.68   40.77   45.72   46.14   46.69   47.13   47.94   49.24   48.84
   49.94   49.94   50.94   49.94   50.54   51.54   50.54   51.34   51.44   52.44
   52.34
BR Coef= 1 , 1 , 1 ,1.25, 0 ,,,.8,0,2,0,
WSPro=,,,, 1 ,,,, 0 ,,,, 0 ,,,,-1 ,-1 ,-1 , 0 , 0 , 0 , 0 , 0
Culvert=2,16,15,134,.015,.4,1,8,1,19.9,4986,19.78,4986,Culvert #1  , 0 ,10
Culvert Bottom n=.015
Culvert=2,16,15,134,.015,.4,1,8,1,19.9,5001.5,19.78,5001.5,Culvert #2  , 0 ,10
Culvert Bottom n=.015
Culvert=2,16,15,134,.015,.4,1,8,1,19.9,5018,19.78,5018,Culvert #3  , 0 ,10
Culvert Bottom n=.015
BC Design=,, 0 ,, 0 ,,,,,,
BC HTab HWMax=53.84

Type RM Length L Ch R = 1 ,14482.00,232.8,242,265.1
BEGIN DESCRIPTION:
CAVALCADE
Downstream Section of Bridge/Culvert/Weir
END DESCRIPTION:
XS GIS Cut Line= 4
  3119693.66819113857577.7862213      3118649.74     13857616.02
      3118267.79     13857605.61 3117324.7971615 13857581.514565
#Sta/Elev= 30
  3796.2   53.64  3816.2   52.54  3836.2   53.24  4076.2   53.34  4196.2   52.64
  4286.2   53.54  4406.2   52.74  4556.2   50.54    4606   51.54  4770.6   48.72
    4890   48.67  4929.5   47.78  4975.1   21.39  5002.2   18.84  5024.9   21.55
    5025   23.89  5039.7   32.97  5042.6   39.24  5050.2   45.85  5050.2   46.72
  5150.1   47.69  5274.4   50.24  5374.4   49.84  5424.4   50.94    5654   51.94
  5684.4   50.94  5774.4   52.54  5974.4   51.54  5994.4   52.34  6166.2   53.34
#Mann= 7 ,-1 , 0
  3796.2      .1       0    4606     .08       0    4890     .04       0
  4929.5     .04       0  5050.2     .04       0  5050.2     .08       0
  5150.1      .1       0
#XS Ineff= 2 ,-1
  3796.2  4978.5      41  5025.5  6166.2      41
Permanent Ineff=
       F       F
Bank Sta=4929.5,5050.2
XS Rating Curve= 0
Exp/Cntr=.5,.3

Type RM Length L Ch R = 1 ,14240.00,312.2,321,330.5
BEGIN DESCRIPTION:
Cross Section Xsec 12a
END DESCRIPTION:
XS GIS Cut Line= 2
  3120051.31221413857596.8217911      3117362.41     13857204.82
#Sta/Elev= 30
    3452      54    3522      52    4022    52.5    4392    51.2    4522    49.4
    4542      48    4582    48.6    4602    50.4    4802    50.9  4836.7    48.2
  4868.7   47.59  4906.9   48.67  4950.7   30.58  4965.7   30.17  4985.6   22.09
  5012.3   22.48  5021.9   24.26  5028.1   28.12  5041.1    32.1  5080.9   29.65
  5087.7   31.09  5110.2   44.92  5119.9   48.63  5169.4   49.79    5332    48.8
    5402    50.2    5482    50.4    5512      49    5582    50.9  6169.3    52.5
#Mann= 6 ,-1 , 0
    3452      .1       0    4802     .08       0  4868.7     .04       0
  4906.9     .04       0  5119.9     .08       0    5402      .1       0
#XS Ineff= 2 , 0
                         5432.62           50.62
Permanent Ineff=
       F       F
Bank Sta=4906.9,5119.9
XS Rating Curve= 0
Exp/Cntr=.3,.1

Type RM Length L Ch R = 1 ,13919.00,669.2,672,676.1
BEGIN DESCRIPTION:
Cross Section x12
END DESCRIPTION:
XS GIS Cut Line= 2
 3119686.6019421 13857327.601837      3117459.79      13856793.3
#Sta/Elev= 30
  3846.6    53.6  3916.6      52  4006.6    52.4  4146.6    50.5  4196.6      52
  4266.6    51.8  4546.6    48.6  4606.6    50.8  4756.6    50.8  4850.2   48.49
  4890.7   47.95  4945.9   27.97  4969.5   30.27    4982   22.71  5012.1   20.33
  5030.7   31.43  5080.2   28.95  5115.2   45.55  5136.6    47.4  5186.6    48.4
  5226.6    47.1  5236.6    48.8  5316.6    50.2  5446.6    50.1  5476.6    51.4
  5536.6    50.9  5646.6    52.3  5766.6    50.9  6066.6    51.2  6136.6    52.6
#Mann= 6 ,-1 , 0
  3846.6      .1       0  4606.6     .08       0  4850.2     .04       0
  4890.7     .04       0  5136.6     .08       0  5316.6      .1       0
Bank Sta=4890.7,5136.6
XS Rating Curve= 0
Exp/Cntr=.3,.1

Type RM Length L Ch R = 1 ,13247.00,89,83,82.8
BEGIN DESCRIPTION:
Cross Section Xsec 11b
END DESCRIPTION:
XS GIS Cut Line= 3
      3120187.52     13856859.19      3118868.26     13856448.33
      3117924.72     13856183.86
#Sta/Elev= 30
  3521.1    51.9  3761.1      53  4071.1      51  4191.1    49.4  4231.1    50.2
  4451.1    48.6  4541.1    49.3  4621.1    45.2  4791.1    48.3  4851.1    46.8
  4873.5   45.07  4909.6   44.97    4928   45.02  4952.2   35.05  4972.1   29.06
  4982.4   21.18  4999.8      21    5017   21.73  5020.6   23.67  5026.7   24.95
  5037.3    30.5  5092.9   48.02  5192.9    49.6  5282.9    49.5  5312.9    50.4
  5442.9      50  5492.9    50.8  5542.9    49.7  5602.9    51.1  5882.8    50.9
#Mann= 6 ,-1 , 0
  3521.1      .1       0  4541.1     .08       0  4909.6     .04       0
    4928     .04       0  5092.9     .08       0  5192.9      .1       0
#XS Ineff= 2 , 0
         4230.89   50.37
Permanent Ineff=
       F       F
Bank Sta=4928,5092.9
XS Rating Curve= 0
Exp/Cntr=.5,.3

Type RM Length L Ch R = 1 ,13164.00,1000.2,987,1153.7
BEGIN DESCRIPTION:
CORONADO/PATTON u/s
Upstream Section of Bridge/Culvert/Weir
END DESCRIPTION:
XS GIS Cut Line= 2
      3120116.33      13856727.5      3117961.32     13856099.28
#Sta/Elev= 30
    3631   53.99  3880.9   52.19  3940.9   52.59  4060.9   50.69  4080.9   51.29
  4210.9   49.49  4330.9   50.19  4600.9   48.09  4630.9   45.39  4780.9   48.59
  4860.9   46.69  4879.3   45.11  4930.8   43.89  4967.8   24.43  4970.2   22.26
  5001.9   17.92  5029.9   22.98  5054.8   30.23  5055.2   34.14  5084.3   46.92
  5219.7    49.6  5230.9   50.49  5330.9   49.39  5390.9   49.69  5430.9   50.69
  5600.9   51.49  5710.9   50.59  5790.9   51.59  5830.9   50.89    5876   51.59
#Mann= 5 ,-1 , 0
    3631      .1       0  4600.9     .08       0  4930.8    .045       0
  5084.3     .08       0  5219.7      .1       0
#XS Ineff= 4 ,-1
 3832.94 4331.36   50.15 5154.85 5489.76   49.99 5023.88 5154.85      45
 4331.36  4978.5      45
Permanent Ineff=
       F       F       F       F
Bank Sta=4930.8,5084.3
XS Rating Curve= 0
Exp/Cntr=.5,.3

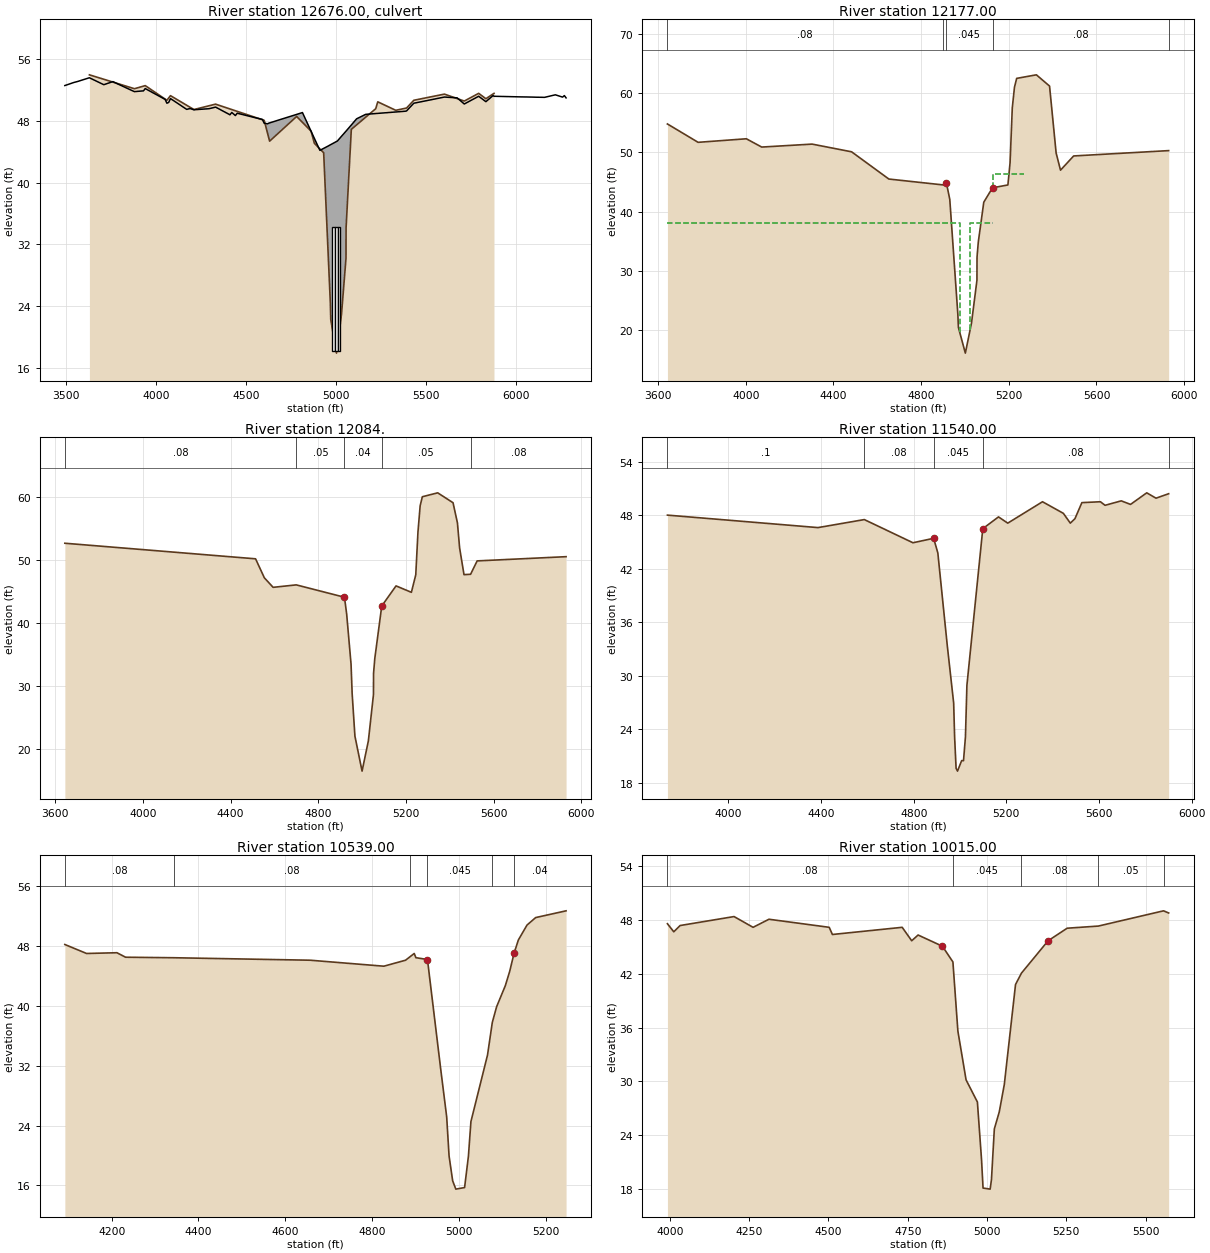
Type RM Length L Ch R = 2 ,12676.00,,,
BEGIN DESCRIPTION:
CORONADO/PATTON
Structure ID: E101-00-00-07
END DESCRIPTION:
Bridge Culvert--1,0,-1,-1, 0
Deck Dist Width WeirC Skew NumUp NumDn MinLoCord MaxHiCord MaxSubmerge Is_Ogee
10,956,2.6,0, 94, 64, , , .95, 0, ,,,
  3494.8  3544.8  3564.8  3630.9  3694.8  3710.9  3754.8  3760.9  3864.8  3880.9
  3924.8  3930.9  3940.9  3954.8  4014.8  4050.9  4060.9  4070.9  4080.9  4124.8
  4154.8  4170.9  4184.8  4190.9  4210.9  4294.8  4324.8  4330.9  4410.9  4414.8
  4420.9  4440.9  4444.8  4450.9  4454.8  4484.8  4494.8  4544.8  4590.9  4600.9
  4620.9  4623.1  4630.9  4660.9  4680.9  4780.9  4813.1  4860.9  4879.3    4910
  4930.8  4930.9  4938.5  4957.9  4967.8  4970.2  5001.9  5007.2  5029.9  5054.8
  5055.2    5061  5084.3  5113.6    5164  5383.1  5390.9  5393.1  5403.1  5416.3
  5430.9  5546.3  5600.9  5626.3  5670.9  5677.1  5710.9  5790.9  5806.3  5826.3
  5830.9  5870.9  5875.6  6026.3  6056.3  6076.3  6096.3  6106.3  6136.3  6156.3
  6216.3  6256.3  6266.3  6275.8
    52.6      53   53.12   53.61   52.89   52.71   53.06   53.11   51.98   51.81
    51.9   51.91   52.21   52.03   51.27   50.81   50.31   50.41   50.91   50.23
   49.76   49.51    49.6   49.61   49.46    49.6   49.77   49.81   48.81   48.93
   49.11   48.71   48.83   49.01   48.99   48.82   48.76   48.47   48.21   47.71
   47.64    47.7   47.76   47.98   48.13   48.86    49.1   46.68   45.75    44.2
   44.46   44.46   44.55   44.79   44.92   44.95   45.35   45.42   46.03   46.69
    46.7   46.86   47.49   48.29   48.87   49.27   49.31   49.37   49.62   49.95
   50.31   50.85   51.11   51.07   51.01   50.89   50.21   51.21   50.94   50.59
   50.51   51.31   51.21   51.13   51.12   51.11    51.1   51.09   51.08   51.07
    51.4    51.1    51.3      51
                                                                                
                                                                                
                                                                                
                                                                                
                                                                                
                                                                                
                                                                                
                                                                                
                                                                                
                                
  3494.8  3544.8  3564.8  3630.9  3694.8  3710.9  3864.8  3880.9  3924.8  3930.9
  3940.9  3954.8  4014.8  4050.9  4060.9  4070.9  4080.9  4124.8  4154.8  4170.9
  4184.8  4190.9  4210.9  4294.8  4324.8  4330.9  4410.9  4414.8  4420.9  4440.9
  4444.8  4450.9  4454.8  4484.8  4494.8  4544.8  4600.9  4620.9  4623.1    4910
  4930.8  4930.9  4938.5  4957.9  4967.8  4970.2  5001.9  5007.2  5029.9  5054.8
  5055.2    5061  5084.3  5113.6    5164  5383.1  5710.9  5826.3  5830.9  6156.3
  6216.3  6256.3  6266.3  6275.8
    52.6      53   53.12   53.61   52.89      50      50      50      50      50
      50      50      50   50.81   50.31   50.41   50.91   50.23   49.76   49.51
    49.6   49.61   49.46    49.6   49.77   49.81   48.81   48.93   49.11   48.71
   48.83   49.01   48.99   48.82   48.76      40      40      40      40    44.2
   44.46   44.46   44.55   44.79   44.92   44.95   45.35   45.42   46.03   46.69
    46.7   46.86   47.49   48.29   48.87   49.27   50.21   50.59   50.51   51.07
    51.4    51.1    51.3      51
                                                                                
                                                                                
                                                                                
                                                                                
                                                                                
                                                                                
                                
BR Coef= 1 , 1 , 1 ,1.25, 0 ,,,.8,0,2,0,
WSPro=,,,, 1 ,,,, 0 ,,,, 0 ,,,,-1 ,-1 ,-1 , 0 , 0 , 0 , 0 , 0
Culvert=2,16,15,956,.015,.5,1,8,2,18.23,4986,16.1,4986,Culvert #1  , 0 ,10
Culvert Bottom n=.015
Culvert=2,16,15,956,.015,.5,1,8,2,18.23,5001.1,16.1,5001.1,Culvert #2  , 0 ,10
Culvert Bottom n=.015
Culvert=2,16,15,956,.015,.5,1,8,2,18.23,5016.4,16.1,5016.4,Culvert #3  , 0 ,10
Culvert Bottom n=.015
BC Design=,, 0 ,, 0 ,,,,,,
BC HTab HWMax=53.99

Type RM Length L Ch R = 1 ,12177.00,93.7,93,92.5
BEGIN DESCRIPTION:
CORONADO/PATTON  **see note**
Cross Section Xsec 11a
The levee at this cross section is used to correctly model low flows not spilling into the low area in the overbank.  It does not represent a certified levee.
END DESCRIPTION:
XS GIS Cut Line= 4
 3120413.4399712 13856356.879524      3119672.57       13855692.
      3119216.09     13855453.05      3118468.19     13855247.72
#Sta/Elev= 30
    3643    54.8    3783    51.7    4003    52.3    4073    50.9    4303    51.4
    4483    50.1    4653    45.5  4900.1   44.51  4915.3   44.87  4930.9   42.07
  4967.8   22.61  4970.2   20.44  5001.9    16.1  5029.9   21.16  5054.8   28.41
  5055.2   32.32    5061   34.87    5086   41.59  5125.8   44.02    5196    44.5
    5206    48.3    5216    57.5    5226      61    5236    62.5    5326    63.1
    5386    61.2    5416    49.9    5436      47    5496    49.4  5929.3    50.3
#Mann= 5 ,-1 , 0
    3643     .08       0  4900.1     .04       0  4915.3    .045       0
  5125.8     .08       0  5929.3      .1       0
#XS Ineff= 3 ,-1
 5127.27 5269.11    46.4 5023.88 5127.27      38    3643  4978.5      38
Permanent Ineff=
       F       F       F
Bank Sta=4915.3,5125.8
XS Rating Curve= 0
Exp/Cntr=.5,.3

Type RM Length L Ch R = 1 ,12084.  ,577.5,544,500.3
BEGIN DESCRIPTION:
U/S Structure 7 at I45 S and Coronado-XS1
END DESCRIPTION:
XS GIS Cut Line= 4
      3120455.29     13856274.76      3119714.43     13855609.89
      3119257.95     13855370.94      3118510.05     13855165.61
#Sta/Elev= 30
  3644.3   52.69  4514.3   50.22  4554.3   47.21  4594.3    45.7  4699.8   46.09
  4919.8   44.13  4929.8   41.46  4949.8   33.52 4954.82   28.85 4967.46   22.11
 5000.05   16.57 5028.83   21.38 5052.02   28.71 5052.42   32.06 5058.12   34.43
  5089.8   42.74    5155   45.93    5225   44.91    5245   47.69    5255   54.48
    5265   58.63    5275   60.06    5345   60.68    5415   59.11    5435   55.92
    5445   51.94    5465   47.71    5495   47.77    5525   49.89  5930.6   50.56
#Mann= 5 ,-1 , 0
  3644.3     .08       0  4699.8     .05       0  4919.8     .04       0
  5089.8     .05       0    5495     .08       0
Bank Sta=4919.8,5089.8
XS Rating Curve= 0
Exp/Cntr=.3,.1

Type RM Length L Ch R = 1 ,11540.00,894.3,1001,1017.4
BEGIN DESCRIPTION:
Cross Section x11
END DESCRIPTION:
XS GIS Cut Line= 3
      3120658.68      13854641.3      3119577.32     13854888.59
      3118546.72     13855112.64
#Sta/Elev= 30
  3736.8      48  4386.8    46.6  4586.8    47.5  4796.8    44.9  4886.1    45.4
  4904.2   43.76    4945   33.36  4972.5   26.93  4976.7   23.08    4983   19.61
  4989.2   19.29    5007   20.47    5015   20.46  5023.4   23.13  5029.7   28.91
  5098.3   46.48  5166.1    47.8  5206.1    47.1  5356.1    49.5  5446.1    48.2
  5476.1    47.1  5496.1    47.6  5526.1    49.4  5606.1    49.5  5626.1    49.1
  5696.1    49.6  5736.1    49.2  5806.1    50.5  5846.1    49.9  5900.7    50.4
#Mann= 5 ,-1 , 0
  3736.8      .1       0  4586.8     .08       0  4886.1    .045       0
  5098.3     .08       0  5900.7     .08       0
Bank Sta=4886.1,5098.3
XS Rating Curve= 0
Exp/Cntr=.3,.1

Type RM Length L Ch R = 1 ,10539.00,514.6,524,524.8
BEGIN DESCRIPTION:
Cross Section x10
END DESCRIPTION:
XS GIS Cut Line= 3
      3120503.83      13854550.3       3120090.1     13854385.55
  3119578.47799313853893.2647169
#Sta/Elev= 30
  4092.1    48.2  4142.1      47  4212.1    47.1  4232.1    46.5  4344.2   46.43
  4657.4    46.1  4827.4    45.3  4877.4    46.1  4887.4   46.55  4897.4      47
  4901.2   46.44  4927.9   46.19  4958.1   31.71  4972.2   25.17  4977.7   19.94
    4986   16.62  4993.3   15.51  5013.5   15.72  5022.3   19.91  5028.1   24.54
  5066.3   33.42  5077.4    37.8  5087.4    39.9  5107.4    42.7  5117.4    44.6
  5127.4      47  5137.4    48.8  5157.4    50.8  5177.4    51.8  5247.4    52.7
#Mann= 6 ,-1 , 0
  4092.1     .08       0  4344.2     .08       0  4887.4     .04       0
  4927.9    .045       0  5077.4     .04       0  5127.4     .04       0
Bank Sta=4927.9,5127.4
XS Rating Curve= 0
Exp/Cntr=.3,.1

Type RM Length L Ch R = 1 ,10015.00,110.2,110,109.3
BEGIN DESCRIPTION:
Cross Section Xsec 5b
END DESCRIPTION:
XS GIS Cut Line= 2
      3120808.55      13854487.5 3119769.040551913853297.6555824
#Sta/Elev= 30
  3992.5    47.6  4012.5    46.7  4032.5    47.4  4202.5    48.4  4262.5    47.2
  4312.5    48.1  4502.5    47.2  4512.5    46.4  4732.5    47.2  4762.5    45.7
  4782.7   46.34  4859.3   45.09  4892.4   43.34  4908.1   35.62  4933.9   30.18
  4969.6   27.71  4982.7   21.25  4987.4   18.11  5009.8   17.99  5013.9   19.04
    5023   24.71  5038.5    26.6  5054.4   29.66  5089.8   40.82  5108.5   42.09
  5192.5    45.7  5252.5    47.1  5350.9   47.34  5556.4   49.04  5572.5    48.8
#Mann= 5 ,-1 , 0
  3992.5     .08       0  4892.4    .045       0  5108.5     .08       0
  5350.9     .05       0  5556.4     .08       0
Bank Sta=4859.3,5192.5
XS Rating Curve= 0
Exp/Cntr=.5,.3