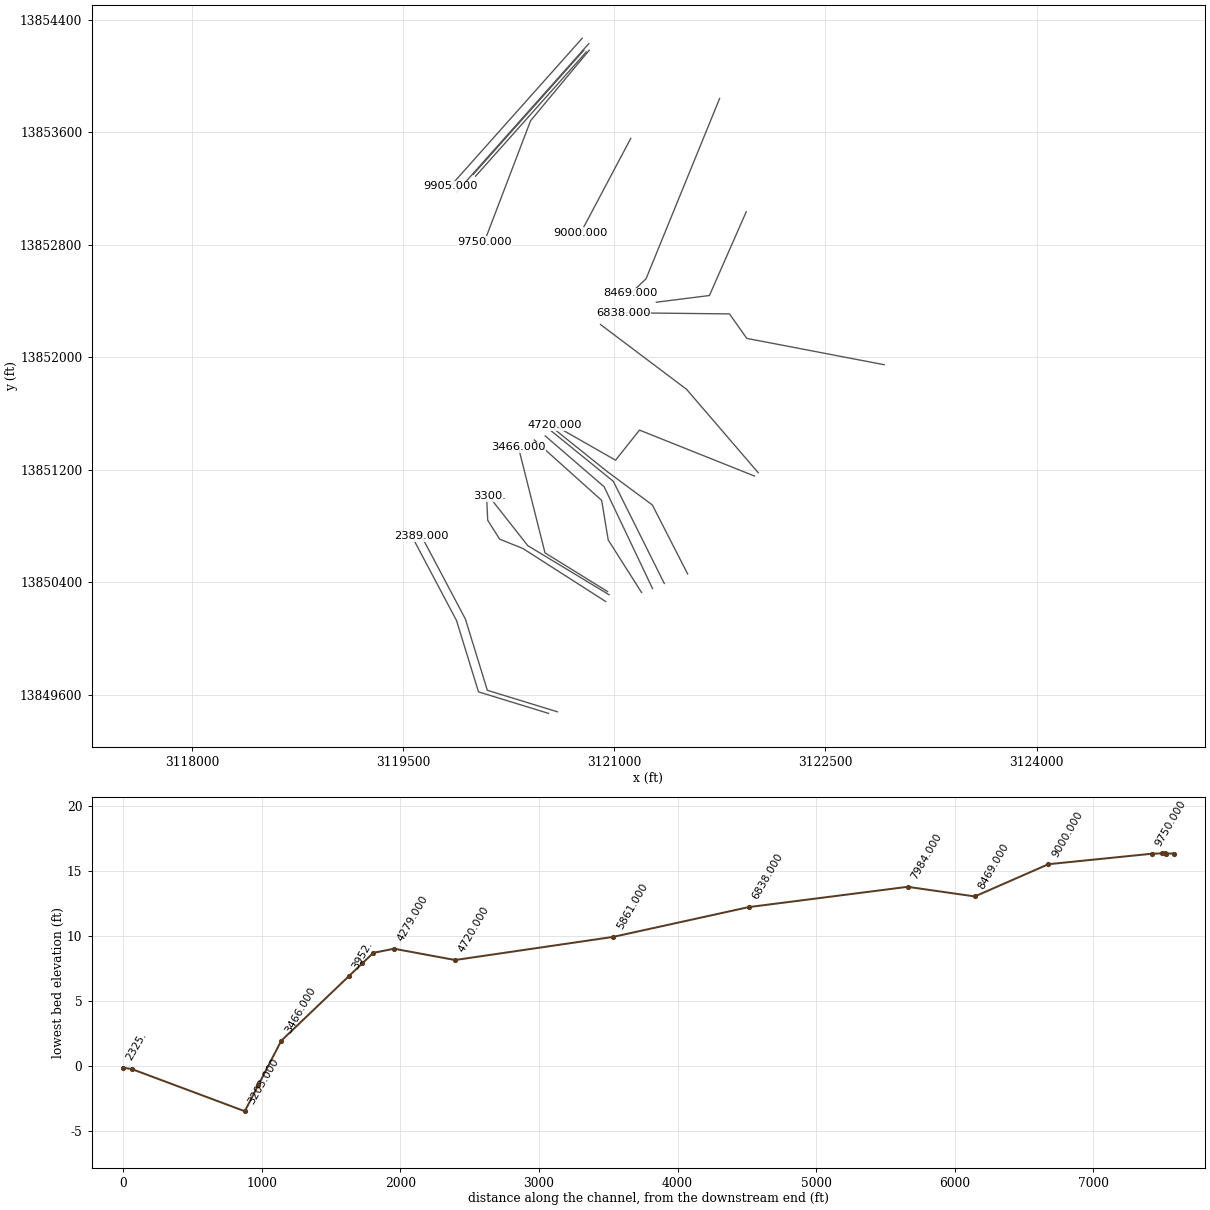
HEC-RAS study E101_00_00.prj: E101-00-00

--- E101_00_00.g01 (geometry) --- (continued)

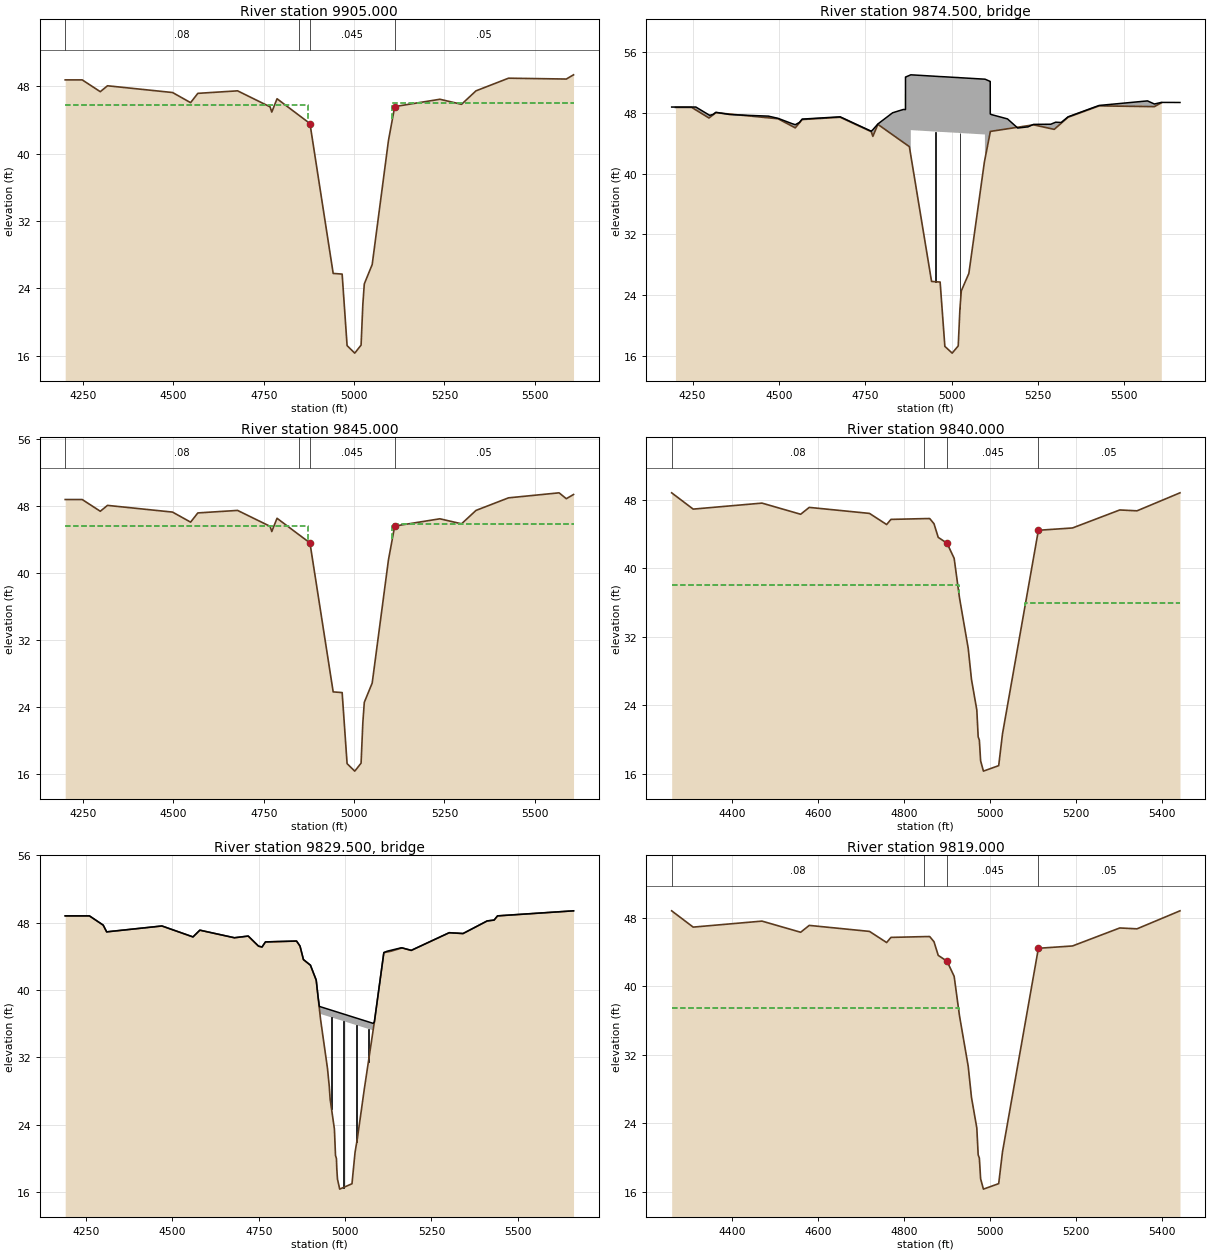
Type RM Length L Ch R = 1 ,9905.000,64.3,60,59.8
BEGIN DESCRIPTION:
TRIMBLE u/s
Upstream Section of Bridge/Culvert/Weir
END DESCRIPTION:
XS GIS Cut Line= 2
      3120771.44     13854268.73 3119834.275699513853215.3038355
#Sta/Elev= 30
  4200.3   48.75  4247.4   48.75  4297.4   47.35  4317.4   48.05  4497.4   47.25
  4547.4   46.05  4567.4   47.15  4677.4   47.45  4767.4   45.55  4772.1   44.93
  4786.7   46.51  4846.7   44.57  4877.8   43.57  4942.1   25.78  4966.9    25.7
  4980.6   17.21  5001.8   16.32  5019.3   17.27  5024.2   22.11  5028.2   24.53
  5050.1   26.84  5095.1   41.55 5112.11   45.51  5112.4   45.58  5237.4   46.45
  5297.4   45.85  5337.4   47.45  5427.4   48.95  5587.4   48.85  5607.4   49.35
#Mann= 4 ,-1 , 0
  4200.3     .08       0  4846.7     .04       0  4877.8    .045       0
  5112.4     .05       0
#XS Ineff= 2 , 0
       0    4872   45.72    5106       0   45.97
Permanent Ineff=
       F       F
Bank Sta=4877.8,5112.11
XS Rating Curve= 0
Exp/Cntr=.5,.3

Type RM Length L Ch R = 3 ,9874.500,,,
BEGIN DESCRIPTION:
TRIMBLE
Structure ID: E101-00-00-05
END DESCRIPTION:
Bridge Culvert--1,0,-1,-1, 0
Deck Dist Width WeirC Skew NumUp NumDn MinLoCord MaxHiCord MaxSubmerge Is_Ogee
10,41,2.6,0, 75, 75, , , .95, 0, ,,,
  4189.4  4197.4  4247.4  4259.4  4297.4  4299.4  4309.4  4317.4  4357.4  4407.4
  4469.4  4497.4  4537.4  4547.4  4559.4  4567.4  4579.4  4677.4  4679.4  4719.4
  4749.4  4759.4  4767.4  4769.4  4772.1  4786.7  4829.2  4846.7  4860.5 4866.49
  4866.6 4866.71  4877.8  4881.8 4881.91    4882  4883.1  4942.1  4952.8  4966.9
  4980.6  4980.7  5001.8  5019.2  5019.3  5024.2  5028.2  5050.1  5095.1 5096.59
  5096.7  5096.8 5111.89    5112 5112.11  5112.4  5115.8  5162.1  5191.6  5221.1
  5237.4  5287.4  5297.4  5301.6  5317.4  5337.4  5341.6  5411.6  5427.4  5431.6
  5441.6  5567.4  5587.4  5607.4  5661.6
    48.8    48.8    48.8    48.8   47.76    47.7   47.83   48.11   47.81   47.71
    47.6   47.31   46.62   46.47   46.77   47.21   47.24   47.51   47.47   46.62
   45.99   45.78   45.61    45.7   45.81   46.57   48.04   48.29   48.48   48.46
   52.76   52.76   52.97   53.05   53.05   53.05   53.05   52.89   52.86   52.82
   52.79   52.79   52.73   52.69   52.69   52.67   52.66    52.6   52.48   52.48
   52.48   52.48   52.18   52.18   47.88   47.87    47.8   47.23   46.03   46.18
   46.51   46.53   46.72    46.8   46.76   47.51   47.58   48.75   49.01   49.03
   49.07   49.61    49.2   49.41    49.4
                                                                                
                                                                                
                                                                                
                                   42.57   45.75   45.75   45.59   45.56   45.52
   45.49   45.49   45.43   45.39   45.39   45.37   45.36    45.3   45.18   45.18
   41.97
                                                                                
                                        
  4189.4  4197.4  4247.4  4259.4  4297.4  4299.4  4309.4  4317.4  4357.4  4407.4
  4469.4  4497.4  4537.4  4547.4  4559.4  4567.4  4579.4  4677.4  4679.4  4719.4
  4749.4  4759.4  4767.4  4769.4  4772.1  4786.7  4829.2  4846.7  4860.5 4866.49
  4866.6 4866.71  4877.8  4881.8 4881.91    4882  4883.1  4942.1  4952.8  4966.9
  4980.6  4980.7  5001.8  5019.2  5019.3  5024.2  5028.2  5050.1  5095.1 5096.59
  5096.7  5096.8 5111.89    5112 5112.11  5112.4  5115.8  5162.1  5191.6  5221.1
  5237.4  5287.4  5297.4  5301.6  5317.4  5337.4  5341.6  5411.6  5427.4  5431.6
  5441.6  5567.4  5587.4  5607.4  5661.6
    48.8    48.8    48.8    48.8   47.76    47.7   47.83   48.11   47.81   47.71
    47.6   47.31   46.62   46.47   46.77   47.21   47.24   47.51   47.47   46.62
   45.99   45.78   45.61    45.7   45.81   46.57   48.04   48.29   48.48   48.46
   52.76   52.76   52.97   53.05   53.05   53.05   53.05   52.89   52.86   52.82
   52.79   52.79   52.73   52.69   52.69   52.67   52.66    52.6   52.48   52.48
   52.48   52.48   52.18   52.18   47.88   47.87    47.8   47.23   46.03   46.18
   46.51   46.53   46.72    46.8   46.76   47.51   47.58   48.75   49.01   49.03
   49.07   49.61    49.2   49.41    49.4
                                                                                
                                                                                
                                                                                
                                   42.57   45.75   45.75   45.59   45.56   45.52
   45.49   45.49   45.43   45.39   45.39   45.37   45.36    45.3   45.18   45.18
   41.97
                                                                                
                                        
Pier Skew, UpSta & Num, DnSta & Num=  ,4952.8, 2 ,4952.8, 2 , 0 , 0 , 0 ,,
     1.5     1.5
   26.07   46.56
     1.5     1.5
   26.07   46.56
Pier Skew, UpSta & Num, DnSta & Num=  ,5024.2, 2 ,5024.2, 2 , 0 , 0 , 0 ,,
     1.5     1.5
   22.65   46.37
     1.5     1.5
   22.65   46.37
BR Coef= 1 , 1 , 1 ,1.25, 0 ,,,.8,-1,2,0,
WSPro=,,,, 1 ,,,, 0 ,,,, 0 ,,,,-1 ,-1 ,-1 , 0 , 0 , 0 , 0 , 0
BC Design=,, 0 ,, 0 ,,,,,,
BC HTab HWMax=49.55

Type RM Length L Ch R = 1 ,9845.000,5.2,5,5
BEGIN DESCRIPTION:
TRIMBLE
Downstream Section of Bridge/Culvert/Weir
END DESCRIPTION:
XS GIS Cut Line= 2
      3120818.74      13854230.9 3119883.514293513853179.7194672
#Sta/Elev= 30
  4200.3   48.75  4247.4   48.75  4297.4   47.35  4317.4   48.05  4497.4   47.25
  4547.4   46.05  4567.4   47.15  4677.4   47.45  4767.4   45.55  4772.1   44.93
  4786.7   46.51  4846.7   44.57  4877.8   43.57  4942.1   25.78  4966.9    25.7
  4980.6   17.21  5001.8   16.32  5019.3   17.27  5024.2   22.11  5028.2   24.53
  5050.1   26.84  5095.1   41.55  5112.4   45.58  5237.4   46.45  5297.4   45.85
  5337.4   47.45  5427.4   48.95  5567.4   49.55  5587.4   48.85  5607.4   49.35
#Mann= 4 ,-1 , 0
  4200.3     .08       0  4846.7     .04       0  4877.8    .045       0
  5112.4     .05       0
#XS Ineff= 2 , 0
       0    4872   45.55    5106       0   45.77
Permanent Ineff=
       F       F
Bank Sta=4877.8,5112.4
XS Rating Curve= 0
Exp/Cntr=.5,.3

Type RM Length L Ch R = 1 ,9840.000,21.3,21,21
BEGIN DESCRIPTION:
PL1_E101-00-00-05 u/s
Upstream Section of Bridge/Culvert/Weir
END DESCRIPTION:
XS GIS Cut Line= 2
 3120783.5953143 13854183.893808  3119997.78288213853300.6445697
#Sta/Elev= 30
  4259.3    48.8  4309.3    46.9  4469.4    47.6  4559.3    46.3  4579.3    47.1
  4719.4    46.4  4759.3    45.1  4769.3    45.7  4846.7   45.79  4859.4    45.8
  4869.4    45.2  4879.3    43.6 4899.61   42.93 4916.31   41.16 4928.81   36.53
 4949.01   30.66 4956.61   27.03 4969.01   23.47 4972.21   20.32 4974.91   19.96
 4977.91   17.52 4984.41   16.33 5019.91   16.97 5028.81    20.7  5111.5   44.22
 5112.21   44.43  5191.6    44.7  5301.5    46.8  5341.6    46.7  5441.6    48.8
#Mann= 4 ,-1 , 0
  4259.3     .08       0  4846.7     .04       0 4899.61    .045       0
  5111.5     .05       0
#XS Ineff= 2 , 0
       0 4927.22      38  5081.1       0      36
Permanent Ineff=
       F       F
Bank Sta=4899.61,5112.21
XS Rating Curve= 0
Exp/Cntr=.5,.3

Type RM Length L Ch R = 3 ,9829.500,,,
BEGIN DESCRIPTION:
PL1_E101-00-00-05
END DESCRIPTION:
Bridge Culvert--1,0,-1,-1, 0
Deck Dist Width WeirC Skew NumUp NumDn MinLoCord MaxHiCord MaxSubmerge Is_Ogee
1,1,2.6,0, 34, 34, , , .95, 0, ,,,
  4189.3  4259.4  4299.4  4309.4  4469.4  4559.3  4579.3  4679.3  4719.4  4749.3
  4759.3  4769.3  4859.4  4869.4  4879.4 4899.61 4916.31  4921.5 4925.51 4927.12
  5081.1 5084.81 5112.21  5121.5  5161.6 5164.91  5191.6  5301.5  5341.6  5411.5
  5431.6  5441.5  5661.5  5661.6
    48.8    48.8    47.7    46.9    47.6    46.3    47.1    46.2    46.4    45.2
    45.1   45.71   45.81   45.21    43.6   42.94   41.17   39.25   38.04   38.02
   36.03   36.21   44.44    44.6      45      45    44.7    46.8    46.7    48.2
    48.3    48.8    49.4    49.4
    48.8    48.8   47.69    46.9    47.6    46.3    47.1    46.2    46.4    45.2
    45.1    45.7    45.8    45.2    43.6   42.93   41.16   39.24   37.75   37.16
    35.2    36.2   44.43   44.51   44.95   44.99    44.7    46.8    46.7    48.2
    48.3    48.8    49.4    49.4
  4189.3  4259.4  4299.4  4309.4  4469.4  4559.3  4579.3  4679.3  4719.4  4749.3
  4759.3  4769.3  4859.4  4869.4  4879.4 4899.61 4916.31  4921.5 4925.51 4927.12
  5081.1 5084.81 5112.21  5121.5  5161.6 5164.91  5191.6  5301.5  5341.6  5411.5
  5431.6  5441.5  5661.5  5661.6
    48.8    48.8    47.7    46.9    47.6    46.3    47.1    46.2    46.4    45.2
    45.1   45.71   45.81   45.21    43.6   42.94   41.17   39.25   38.04   38.02
   36.03   36.21   44.44    44.6      45      45    44.7    46.8    46.7    48.2
    48.3    48.8    49.4    49.4
    48.8    48.8   47.69    46.9    47.6    46.3    47.1    46.2    46.4    45.2
    45.1    45.7    45.8    45.2    43.6   42.93   41.16   39.24   37.75   37.16
    35.2    36.2   44.43   44.51   44.95   44.99    44.7    46.8    46.7    48.2
    48.3    48.8    49.4    49.4
Pier Skew, UpSta & Num, DnSta & Num=  ,4960.7, 2 ,4960.7, 2 , 0 , 0 , 0 ,,
     1.5     1.5
   24.64   37.77
     1.5     1.5
   24.64   37.77
Pier Skew, UpSta & Num, DnSta & Num=  ,4995.1, 2 ,4995.1, 2 , 0 , 0 , 0 ,,
     1.5     1.5
   15.51   37.32
     1.5     1.5
   15.51   37.32
Pier Skew, UpSta & Num, DnSta & Num=  ,5033.6, 2 ,5033.6, 2 , 0 , 0 , 0 ,,
     1.5     1.5
    20.7   36.83
     1.5     1.5
    20.7   36.83
Pier Skew, UpSta & Num, DnSta & Num=  ,5067.4, 2 ,5067.4, 2 , 0 , 0 , 0 ,,
     1.5     1.5
   30.24   36.39
     1.5     1.5
   30.24   36.39
BR Coef= 1 , 1 , 1 ,1.25, 0 ,,,.8,-1,2,0,
WSPro=,,,, 1 ,,,, 0 ,,,, 0 ,,,,-1 ,-1 ,-1 , 0 , 0 , 0 , 0 , 0
BR U #Sta/Elev= 78
  4189.3    48.8  4189.4    48.8  4259.3    48.8  4259.4    48.8  4299.3    47.7
  4299.4   47.69  4309.3    46.9  4309.4    46.9  4469.3    47.6  4469.4    47.6
  4559.3    46.3  4559.4    46.3  4579.3    47.1  4579.4    47.1  4679.3    46.2
  4679.4    46.2  4719.3    46.4  4719.4    46.4  4749.3    45.2  4749.4    45.2
  4759.3    45.1  4759.4    45.1  4769.3    45.7  4769.4    45.7  4846.7   45.79
  4859.3    45.8  4859.4    45.8  4869.3   45.21  4869.4    45.2  4879.3    43.6
  4879.4    43.6  4899.4   42.94 4899.61   42.93 4916.31   41.16  4921.5   39.24
 4925.51   37.75 4927.12   37.16 4927.21   37.12 4928.81   36.53 4949.01   30.66
 4954.31   28.46 4956.61   27.03 4969.01   23.47 4972.21   20.32 4974.91   19.96
 4975.91   18.77 4977.91   17.52 4984.41   16.33 5019.91   16.97 5024.11   18.74
 5028.81    20.7 5035.71    22.4 5055.71   28.25  5065.6   30.95  5081.1   35.19
 5081.21   35.22 5084.81    36.2 5102.81   41.61  5111.5   44.22 5112.21   44.43
  5121.5   44.51 5132.91    44.6  5161.6   44.95 5164.91   44.99  5191.5    44.7
  5191.6    44.7  5301.5    46.8  5301.6    46.8  5341.5    46.7  5341.6    46.7
  5411.5    48.2  5411.6    48.2  5431.5    48.3  5431.6    48.3  5441.5    48.8
  5441.6    48.8  5661.5    49.4  5661.6    49.4
BR U #Mann= 4
  4189.3     .08  4846.7     .04 4916.31    .045  5111.5     .05
BR D #Sta/Elev= 78
  4189.3    48.8  4189.4    48.8  4259.3    48.8  4259.4    48.8  4299.3    47.7
  4299.4   47.69  4309.3    46.9  4309.4    46.9  4469.3    47.6  4469.4    47.6
  4559.3    46.3  4559.4    46.3  4579.3    47.1  4579.4    47.1  4679.3    46.2
  4679.4    46.2  4719.3    46.4  4719.4    46.4  4749.3    45.2  4749.4    45.2
  4759.3    45.1  4759.4    45.1  4769.3    45.7  4769.4    45.7  4846.7   45.79
  4859.3    45.8  4859.4    45.8  4869.3   45.21  4869.4    45.2  4879.3    43.6
  4879.4    43.6  4899.4   42.94 4899.61   42.93 4916.31   41.16  4921.5   39.24
 4925.51   37.75 4927.12   37.16 4927.21   37.12 4928.81   36.53 4949.01   30.66
 4954.31   28.46 4956.61   27.03 4969.01   23.47 4972.21   20.32 4974.91   19.96
 4975.91   18.77 4977.91   17.52 4984.41   16.33 5019.91   16.97 5024.11   18.74
 5028.81    20.7 5035.71    22.4 5055.71   28.25  5065.6   30.95  5081.1   35.19
 5081.21   35.22 5084.81    36.2 5102.81   41.61  5111.5   44.22 5112.21   44.43
  5121.5   44.51 5132.91    44.6  5161.6   44.95 5164.91   44.99  5191.5    44.7
  5191.6    44.7  5301.5    46.8  5301.6    46.8  5341.5    46.7  5341.6    46.7
  5411.5    48.2  5411.6    48.2  5431.5    48.3  5431.6    48.3  5441.5    48.8
  5441.6    48.8  5661.5    49.4  5661.6    49.4
BR D #Mann= 4
  4189.3     .08  4846.7     .04 4916.31    .045  5111.5     .05
BC Design=,, 0 ,, 0 ,,,,,,
BC HTab HWMax=49.4

Type RM Length L Ch R = 1 ,9819.000,47.4,69,89.6
BEGIN DESCRIPTION:
PL1_E101-00-00-05
Downstream Section of Bridge/Culvert/Weir
END DESCRIPTION:
XS GIS Cut Line= 2
 3120800.549655313854171.4125853  3120014.73165513853288.1083006
#Sta/Elev= 30
  4259.3    48.8  4309.3    46.9  4469.4    47.6  4559.3    46.3  4579.3    47.1
  4719.4    46.4  4759.3    45.1  4769.3    45.7  4846.7   45.79  4859.4    45.8
  4869.4    45.2  4879.3    43.6 4899.61   42.93 4916.31   41.16 4928.81   36.53
 4949.01   30.66 4956.61   27.03 4969.01   23.47 4972.21   20.32 4974.91   19.96
 4977.91   17.52 4984.41   16.33 5019.91   16.97 5028.81    20.7  5111.5   44.22
 5112.21   44.43  5191.6    44.7  5301.5    46.8  5341.6    46.7  5441.6    48.8
#Mann= 4 ,-1 , 0
  4259.3     .08       0  4846.7     .04       0 4899.61    .045       0
  5111.5     .05       0
#XS Ineff= 2 , 0
       0 4927.22    37.5  5081.1       0    35.5
Permanent Ineff=
       F       F
Bank Sta=4899.61,5112.21
XS Rating Curve= 0
Exp/Cntr=.5,.3

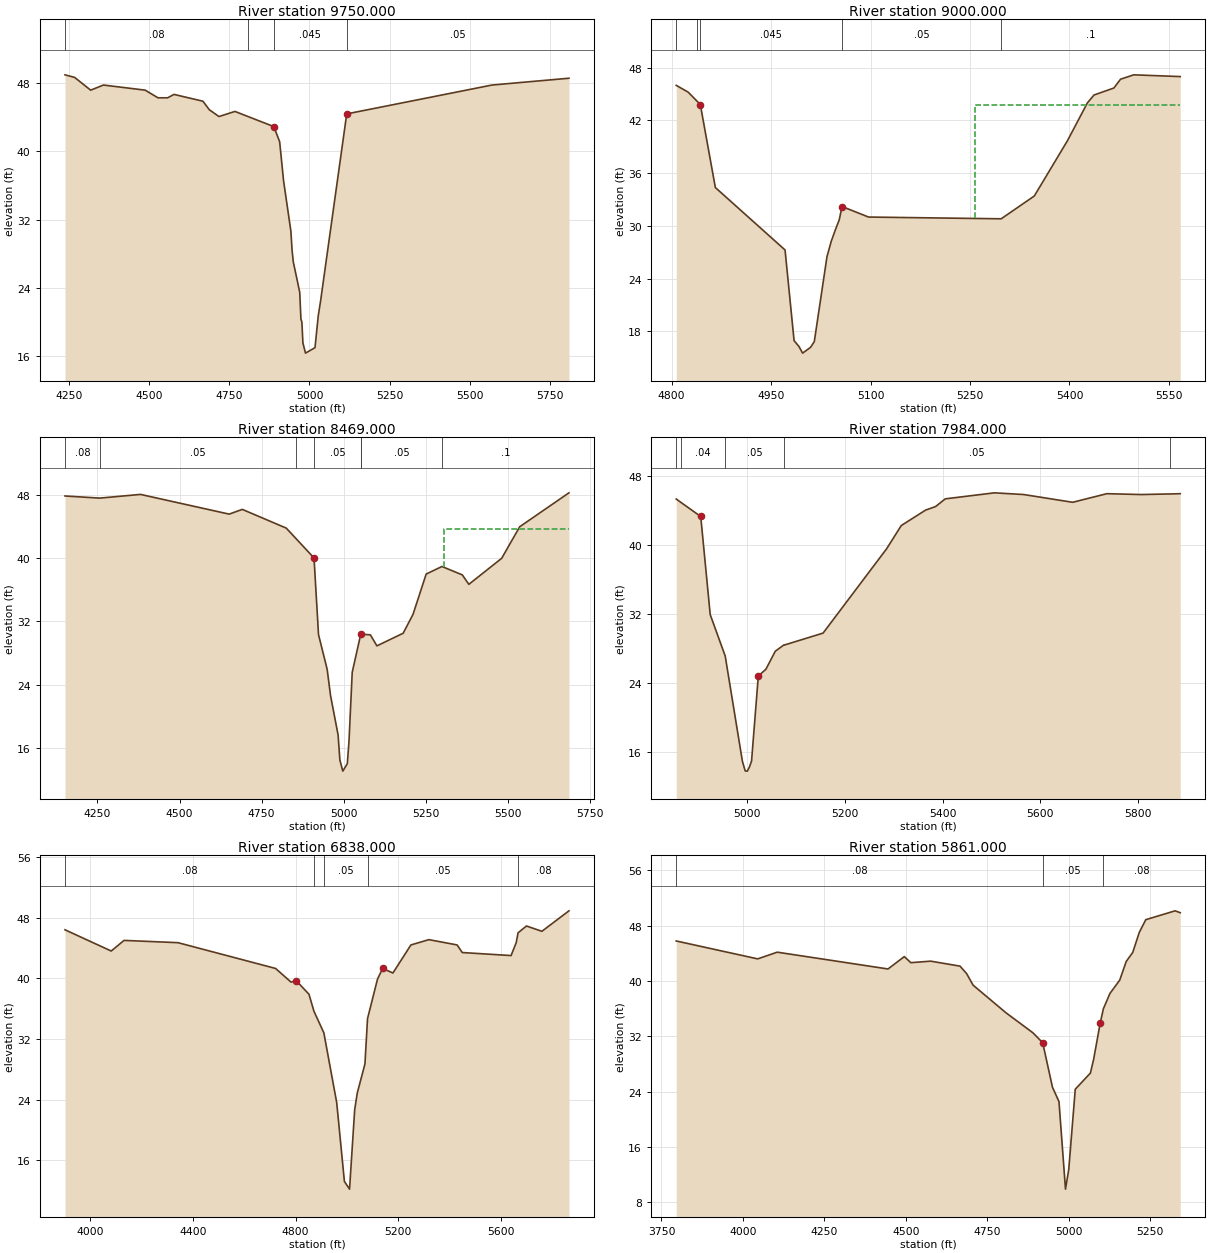
Type RM Length L Ch R = 1 ,9750.000,736.4,750,722.6
BEGIN DESCRIPTION:
Cross Section Xsec 5a
END DESCRIPTION:
XS GIS Cut Line= 3
  3120821.43722613854183.9661632      3120405.34     13853682.87
 3120077.621656213852823.2225405
#Sta/Elev= 30
  4237.8      49  4267.8    48.7  4317.8    47.2  4357.8    47.8  4487.8    47.2
  4527.8    46.3  4557.8    46.3  4577.8    46.7  4667.8    45.9  4687.8    44.9
  4717.8    44.1  4767.8    44.7  4809.8   44.08  4888.9   42.92  4907.1   41.14
  4919.4   36.52  4942.1   30.64  4945.7   28.45  4949.7   27.01  4969.7   23.46
  4973.4   20.31  4976.4   19.95  4979.6   17.51  4987.6   16.31  5017.3   16.95
  5027.4   20.69  5034.5   22.38  5116.2   44.41  5569.1    47.8  5809.1    48.6
#Mann= 4 ,-1 , 0
  4237.8     .08       0  4809.8     .04       0  4888.9    .045       0
  5116.2     .05       0
Bank Sta=4888.9,5116.2
XS Rating Curve= 0
Exp/Cntr=.3,.1

Type RM Length L Ch R = 1 ,9000.000,525.4,531,551.4
BEGIN DESCRIPTION:
Cross Section x9
END DESCRIPTION:
XS GIS Cut Line= 2
 3121116.619313613853556.4529517 3120760.968186613852884.8053817
#Sta/Elev= 26
    4807      46  4825.1   45.22    4839   44.15  4843.3   43.82    4866   34.36
  4971.1   27.25  4984.7   16.93  4992.1   16.25  4997.6    15.5  5009.4   16.15
  5015.2   16.81  5034.3   26.48  5040.8   28.25  5047.4   29.63  5052.8   30.68
    5057    32.2    5097      31    5297    30.8    5347    33.4    5397    39.7
    5427      44    5437    44.9    5467    45.7    5477    46.7    5497    47.2
    5567      47
#Mann= 5 ,-1 , 0
    4807     .05       0    4839     .04       0  4843.3    .045       0
    5057     .05       0    5297      .1       0
#XS Ineff= 2 , 0
                         5257.68           43.82
Permanent Ineff=
       F       F
Bank Sta=4843.3,5057
XS Rating Curve= 0
Exp/Cntr=.3,.1

Type RM Length L Ch R = 1 ,8469.000,480.2,485,498.4
BEGIN DESCRIPTION:
Cross Section x8
END DESCRIPTION:
XS GIS Cut Line= 3
      3121747.83     13853840.36      3121225.22     13852557.85
 3121117.7810518 13852456.010736
#Sta/Elev= 30
  4151.1    47.9  4256.9   47.63  4381.1    48.1  4651.1    45.6  4691.1    46.2
  4824.9   43.83  4854.2   42.52  4909.6   40.04  4923.2   30.34  4949.6   25.92
  4959.9   22.59  4982.9    17.6  4988.3   14.43  4997.2   13.02  5010.9   13.96
    5016   16.74  5025.9   25.55  5051.9   30.38    5052   30.38  5081.1    30.3
  5101.1    28.9  5181.1    30.5  5211.1    32.9  5251.1      38  5299.1   38.96
  5361.1    37.9  5381.1    36.7  5481.1      40    5536      44    5686    48.3
#Mann= 7 ,-1 , 0
  4151.1     .08       0  4256.9     .05       0  4854.2     .04       0
  4909.6     .05       0  5051.9     .04       0    5052     .05       0
  5299.1      .1       0
#XS Ineff= 2 , 0
                         5304.96           43.68
Permanent Ineff=
       F       F
Bank Sta=4909.6,5051.9
XS Rating Curve= 0
Exp/Cntr=.3,.1

Type RM Length L Ch R = 1 ,7984.000,1207.3,1146,884
BEGIN DESCRIPTION:
Cross Section x7
END DESCRIPTION:
XS GIS Cut Line= 3
  3121937.173139 13853035.378165      3121675.58     13852439.29
  3121298.53580213852391.6866545
#Sta/Elev= 29
  4855.3   45.38  4865.8   44.95  4905.4   43.35  4924.8   31.95  4955.5   27.13
  4990.6   14.92  4996.4   13.78  5000.7   13.76    5005   14.23  5009.4   14.94
  5023.2   24.82  5038.6   25.59  5043.4   26.11  5057.9   27.69  5075.4   28.42
  5075.7    28.4  5155.7    29.8  5285.7    39.6  5315.7    42.3  5365.7    44.1
  5385.7    44.5  5405.7    45.4  5506.3    46.1  5566.3    45.9  5666.3      45
  5736.3      46  5806.3    45.9  5866.1   45.97  5886.3      46
#Mann= 5 ,-1 , 0
  4855.3     .05       0  4865.8     .04       0  4955.5     .05       0
  5075.4     .05       0  5866.1     .08       0
Bank Sta=4905.4,5023.2
XS Rating Curve= 0
Exp/Cntr=.3,.1

Type RM Length L Ch R = 1 ,6838.000,931.1,977,867.9
BEGIN DESCRIPTION:
Cross Section x6
END DESCRIPTION:
XS GIS Cut Line= 4
      3122916.97     13851947.04      3121940.92      13852134.3
      3121818.29     13852308.45        3121063.     13852316.78
#Sta/Elev= 30
  3902.1    46.4  4082.1    43.6  4132.1      45  4342.1    44.7  4722.1    41.3
  4782.1    39.5  4802.1    39.7  4852.1    37.9  4871.3   35.67    4910   32.81
    4960   23.62    4990   13.21    5010    12.2    5030   22.66    5040   24.86
    5070   28.71    5080   34.68  5118.9    39.9  5138.9    41.3  5178.9    40.7
  5248.9    44.4  5318.9    45.1  5428.9    44.4  5448.9    43.4  5638.9      43
  5658.9    44.7  5666.1      46  5698.9    46.9  5758.9    46.2  5864.3    48.9
#Mann= 5 ,-1 , 0
  3902.1     .08       0  4871.3     .04       0    4910     .05       0
    5080     .05       0  5666.1     .08       0
Bank Sta=4802.1,5138.9
XS Rating Curve= 0
Exp/Cntr=.3,.1

Type RM Length L Ch R = 1 ,5861.000,579.8,1141,863.2
BEGIN DESCRIPTION:
Cross Section x5
END DESCRIPTION:
XS GIS Cut Line= 3
      3122022.06     13851178.89      3121513.52     13851771.75
      3120902.21     13852232.87
#Sta/Elev= 30
  3795.3    45.8  4045.3   43.21  4105.3   44.18  4445.3   41.75  4495.3   43.54
  4515.3   42.66  4576.4   42.88  4666.4   42.16  4686.4   41.09  4706.4   39.41
  4806.4   35.45    4890   32.52    4920   31.09    4950   24.65    4970   22.57
    4990    9.91    5000   12.75    5020   24.36  5066.4   26.69  5076.4   28.68
  5096.4   33.89  5106.4   36.01  5126.4   38.21  5156.4   40.13  5176.4   42.84
  5196.4   44.14  5216.4   47.03  5236.4   48.88  5326.4   50.16  5342.1   49.89
#Mann= 3 ,-1 , 0
  3795.3     .08       0    4920     .05       0  5106.4     .08       0
Bank Sta=4920,5096.4
XS Rating Curve= 0
Exp/Cntr=.3,.1

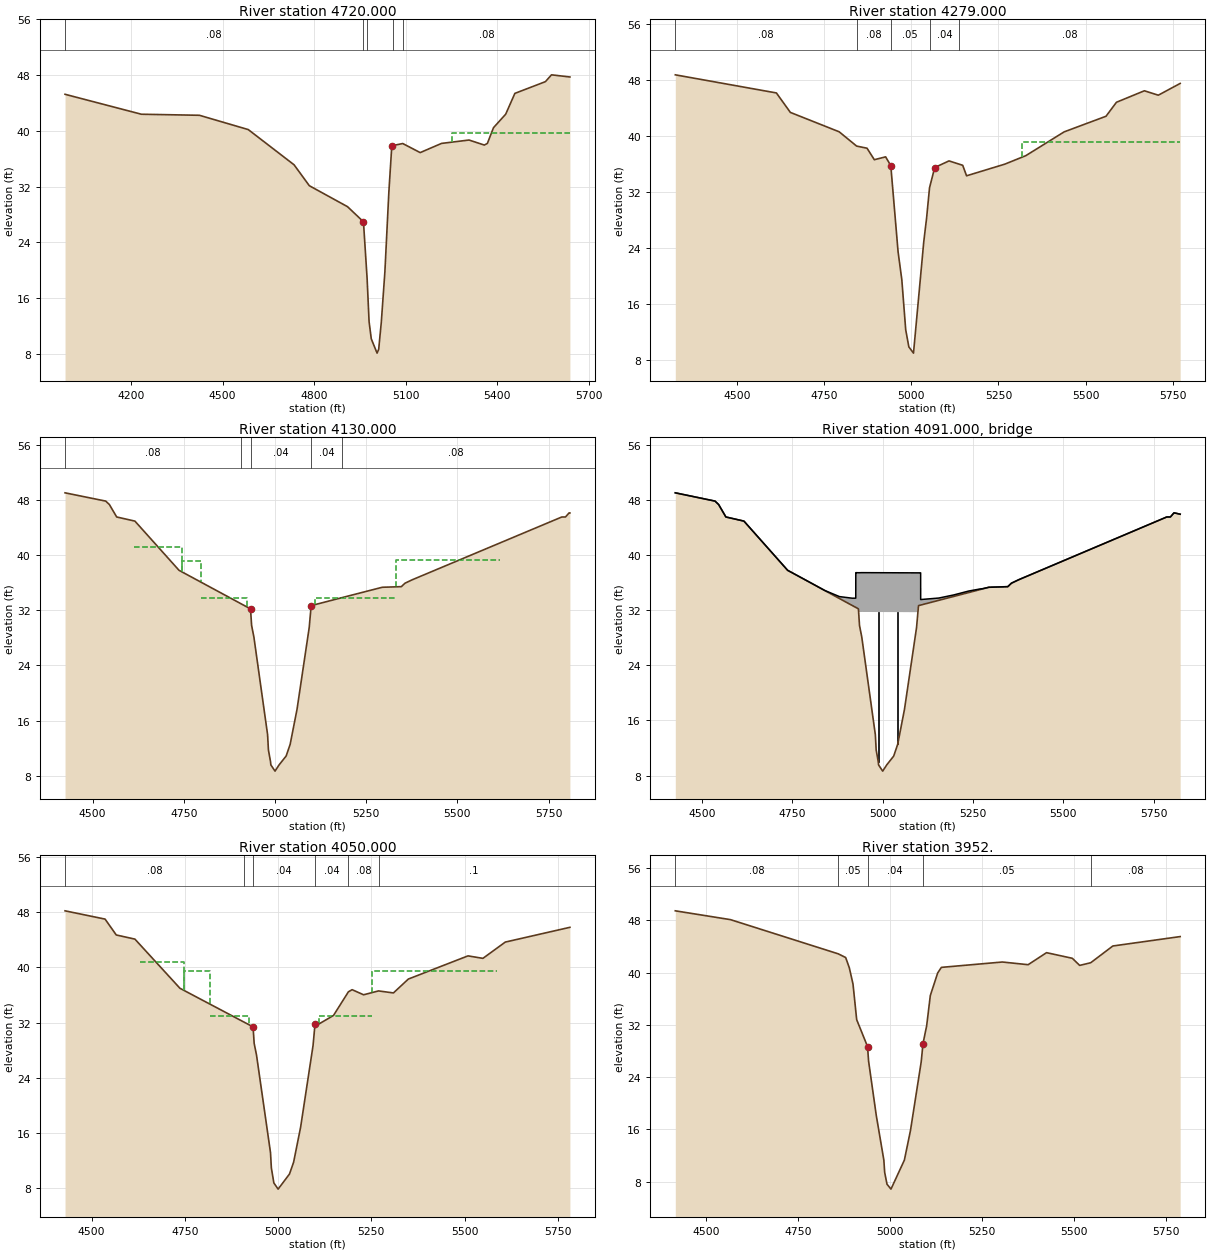
Type RM Length L Ch R = 1 ,4720.000,557.3,441,181.2
BEGIN DESCRIPTION:
Cross Section x4
END DESCRIPTION:
XS GIS Cut Line= 4
      3121995.71     13851155.17      3121178.88     13851481.91
      3121008.82       13851268.      3120574.46     13851515.97
#Sta/Elev= 30
  3984.3   45.24  4234.3   42.38  4424.3   42.23  4584.3   40.18  4734.3   35.13
  4784.3   32.13  4909.2   29.13  4961.5   26.96  4973.5   18.79  4979.9   12.64
  4987.1   10.18  5006.1    8.13  5011.4    8.68    5020   12.61  5031.7   19.81
  5044.7   31.24  5054.3   37.86    5059    37.9  5090.1   38.18  5147.3   36.88
  5217.3    38.2  5307.3   38.68  5357.3   37.96  5367.3    38.2  5387.3   40.45
  5427.3   42.39  5457.3   45.37  5557.3   47.05  5577.3   48.03  5637.5   47.72
#Mann= 5 ,-1 , 0
  3984.3     .08       0  4961.5     .04       0  4973.5     .05       0
    5059     .04       0  5090.1     .08       0
#XS Ineff= 2 , 0
                         5251.54           39.71
Permanent Ineff=
       F       F
Bank Sta=4961.5,5054.3
XS Rating Curve= 0
Exp/Cntr=.3,.1

Type RM Length L Ch R = 1 ,4279.000,204.7,149,72
BEGIN DESCRIPTION:
Cross Section Xsec 3a
END DESCRIPTION:
XS GIS Cut Line= 4
      3121520.73     13850459.04      3121269.95     13850949.61
      3120952.94     13851184.38      3120561.06     13851499.23
#Sta/Elev= 30
    4323   48.77    4613   46.18    4653    43.4    4793   40.63    4843   38.59
    4873   38.28  4893.9   36.64  4926.3   37.05  4941.1   35.78    4962   23.48
  4972.7    19.5  4983.9   12.33  4992.9    9.89  5006.2       9  5035.7   24.94
  5043.8    28.3  5052.2   32.63    5067   35.52  5108.1   36.47  5137.5      36
  5147.4   35.84  5158.4   34.34  5268.4   36.01  5328.4   37.22  5438.4   40.62
  5558.4   42.85  5588.4   44.85  5668.4   46.49  5708.4   45.86  5771.1   47.54
#Mann= 5 ,-1 , 0
    4323     .08       0    4843     .08       0  4941.1     .05       0
  5052.2     .04       0  5137.5     .08       0
#XS Ineff= 2 , 0
                          5317.1           39.15
Permanent Ineff=
       F       F
Bank Sta=4941.1,5067
XS Rating Curve= 0
Exp/Cntr=.5,.3

Type RM Length L Ch R = 1 ,4130.000,92.1,80,110.2
BEGIN DESCRIPTION:
N.MAIN u/s
Upstream Section of Bridge/Culvert/Weir
END DESCRIPTION:
XS GIS Cut Line= 3
      3121354.91     13850391.01      3120993.13      13851117.4
 3120548.964583313851478.6938602
#Sta/Elev= 30
  4424.4   49.02    4536   47.82    4546   47.32    4566   45.52    4616   44.92
  4736.9   37.79  4907.6   32.92  4932.9    32.2  4935.9   29.79  4942.1   28.14
  4979.7   13.97    4982   11.75  4987.8   10.04  4988.7    9.58  5000.1    8.68
  5011.3    9.59  5030.6   10.87  5041.6   12.57  5060.4   17.64  5093.8   29.49
  5099.2   32.67  5183.9   33.83    5294   35.33  5346.4   35.42  5356.4   35.92
  5376.4   36.42  5786.4   45.52  5796.4   45.52  5806.4   46.12  5808.5    46.1
#Mann= 5 ,-1 , 0
  4424.4     .08       0  4907.6     .04       0  4932.9     .04       0
  5099.2     .04       0  5183.9     .08       0
#XS Ineff= 5 ,-1
 4613.08 4745.47   41.18 5331.76 5617.97   39.33 4745.47  4795.9   39.15
  5109.2 5331.76   33.77  4795.9  4922.9   33.77
Permanent Ineff=
       F       F       F       F       F
Bank Sta=4932.9,5099.2
XS Rating Curve= 0
Exp/Cntr=.5,.3

Type RM Length L Ch R = 3 ,4091.000,,,
BEGIN DESCRIPTION:
N.MAIN
Structure ID: E101-00-00-04
END DESCRIPTION:
Bridge Culvert--1,0,-1,-1, 0
Deck Dist Width WeirC Skew NumUp NumDn MinLoCord MaxHiCord MaxSubmerge Is_Ogee
10,58,2.6,0, 43, 43, , , .95, 0, ,,,
    4426    4536    4546    4566    4616  4736.9  4791.3    4840  4880.3  4907.6
  4915.8 4925.49  4925.6 4925.71  4932.9    4934 4934.11  4934.2  4935.9  4942.1
  5093.8 5096.39  5096.5  5096.6  5099.2 5104.99  5105.1 5105.21  5155.6  5183.9
  5196.8  5237.8  5270.1  5275.8    5294  5346.4  5356.4  5376.4  5786.4  5796.4
  5806.4  5808.5  5823.5
      49    47.8    47.3    45.5    44.9   37.77   36.23   34.84   33.96   33.78
   33.73   33.73   37.43   37.43   37.42   37.42   37.42   37.42   37.42   37.43
    37.4    37.4    37.4    37.4    37.4    37.4    37.4   33.53   33.75   34.06
    34.2   34.76   35.07    35.1   35.31    35.4    35.9    36.4    45.5    45.5
    46.1   46.08    45.9
      49    47.8    47.3    45.5    44.9   37.77   36.22   34.83   33.68    32.9
   32.67   32.39   32.39   32.39   32.18    31.3   31.21   31.72   31.72   31.73
    31.7    31.7   31.06   31.12   32.65   32.73   32.73   32.73   33.42   33.81
   33.98   34.54   34.98   35.06   35.31    35.4    35.9    36.4    45.5    45.5
    46.1   46.08    45.9
    4426    4536    4546    4566    4616  4736.9  4791.3    4840  4880.3  4907.6
  4915.8 4925.49  4925.6 4925.71  4932.9    4934 4934.11  4934.2  4935.9  4942.1
  5093.8 5096.39  5096.5  5096.6  5099.2 5104.99  5105.1 5105.21  5155.6  5183.9
  5196.8  5237.8  5270.1  5275.8    5294  5346.4  5356.4  5376.4  5786.4  5796.4
  5806.4  5808.5  5823.5
      49    47.8    47.3    45.5    44.9   37.77   36.23   34.84   33.96   33.78
   33.73   33.73   37.43   37.43   37.42   37.42   37.42   37.42   37.42   37.43
    37.4    37.4    37.4    37.4    37.4    37.4    37.4   33.53   33.75   34.06
    34.2   34.76   35.07    35.1   35.31    35.4    35.9    36.4    45.5    45.5
    46.1   46.08    45.9
   48.32   47.12   46.62   44.82   44.22   37.09   35.54   34.15      33   32.22
   31.99   31.71   31.71   31.71    31.5    31.3   31.21   31.72   31.72   31.73
    31.7    31.7   31.08   31.08   31.08   31.08   31.07   31.07   31.07   31.07
   31.04   31.02   30.99   30.97   31.02   31.02   30.38   30.44   31.97   32.05
   32.05   32.05   32.74
Pier Skew, UpSta & Num, DnSta & Num=  ,4987.8, 2 ,4987.8, 2 , 0 , 0 , 0 ,,
     1.5     1.5
    8.64   32.76
     1.5     1.5
    7.96   32.08
Pier Skew, UpSta & Num, DnSta & Num=  ,5041.6, 2 ,5041.6, 2 , 0 , 0 , 0 ,,
     1.5     1.5
   11.43    32.7
     1.5     1.5
   10.75   32.02
BR Coef= 1 , 1 , 1 ,1.25, 0 ,,,.8,0,2,0,
WSPro=,,,, 1 ,,,, 0 ,,,, 0 ,,,,-1 ,-1 ,-1 , 0 , 0 , 0 , 0 , 0
BR U #Sta/Elev= 57
    4426      49    4536    47.8    4546    47.3    4566    45.5    4616    44.9
  4736.9   37.77  4791.3   36.22    4840   34.83  4880.3   33.68  4907.6    32.9
  4915.8   32.67 4925.49   32.39  4925.6   32.39 4925.71   32.39  4932.9   32.18
    4934    31.3 4934.11   31.21  4934.2   31.14  4935.9   29.77  4942.1   28.12
  4965.9   19.15  4979.7   13.95    4982   11.73  4987.8   10.02  4988.7    9.56
  4988.8    9.55  5000.1    8.66  5011.2    9.56  5011.3    9.57    5018   10.01
  5030.6   10.85  5041.6   12.55  5060.4   17.62  5068.1   20.35  5093.8   29.47
 5096.39      31  5096.5   31.06  5096.6   31.12  5099.2   32.65 5104.99   32.73
  5105.1   32.73 5105.21   32.73  5155.6   33.42  5183.9   33.81  5196.8   33.98
  5237.8   34.54  5270.1   34.98  5275.8   35.06    5294   35.31  5346.4    35.4
  5356.4    35.9  5376.4    36.4  5786.4    45.5  5796.4    45.5  5806.4    46.1
  5808.5   46.08  5823.5    45.9
BR U #Mann= 5
    4426     .08  4907.6     .04  4932.9     .04  5099.2     .04  5183.9     .08
BR U Banks=4932.9,5099.2
BR D #Sta/Elev= 57
    4426   48.32    4536   47.12    4546   46.62    4566   44.82    4616   44.22
  4736.9   37.09  4791.3   35.54    4840   34.15  4880.3      33  4907.6   32.22
  4915.8   31.99 4925.49   31.71  4925.6   31.71 4925.71   31.71  4932.9    31.5
    4934   30.62 4934.11   30.53  4934.2   30.46  4935.9   29.09  4942.1   27.44
  4965.9   18.47  4979.7   13.27    4982   11.05  4987.8    9.34  4988.7    8.88
  4988.8    8.87  5000.1    7.98  5011.2    8.88  5011.3    8.89    5018    9.33
  5030.6   10.17  5041.6   11.87  5060.4   16.94  5068.1   19.67  5093.8   28.79
 5096.39   30.32  5096.5   30.38  5096.6   30.44  5099.2   31.97 5104.99   32.05
  5105.1   32.05 5105.21   32.05  5155.6   32.74  5183.9   33.13  5196.8    33.3
  5237.8   33.86  5270.1    34.3  5275.8   34.38    5294   34.63  5346.4   34.72
  5356.4   35.22  5376.4   35.72  5786.4   44.82  5796.4   44.82  5806.4   45.42
  5808.5    45.4  5823.5   45.22
BR D #Mann= 5
    4426     .08  4907.6     .04  4932.9     .04  5099.2     .04  5183.9     .08
BR D Banks=4932.9,5099.2
BC Design=,, 0 ,, 0 ,,,,,,
BC HTab HWMax=49.02

Type RM Length L Ch R = 1 ,4050.000,113.7,98,92.3
BEGIN DESCRIPTION:
N.MAIN
Downstream Section of Bridge/Culvert/Weir
END DESCRIPTION:
XS GIS Cut Line= 3
      3121271.13      13850355.4      3120927.82     13851078.88
      3120509.14     13851440.61
#Sta/Elev= 30
  4428.6   48.21    4536   47.01    4566   44.71    4616   44.11  4736.9   36.98
  4907.6   32.11  4932.9   31.39  4935.9   28.98  4942.1   27.33  4979.7   13.16
    4982   10.94  4988.7    8.77  5000.1    7.87  5030.6   10.06  5041.6   11.76
  5060.4   16.83  5093.8   28.68  5099.2   31.86  5108.6   31.78  5148.6   33.04
  5188.6   36.47  5198.6   36.78  5229.4   36.04  5269.4    36.6  5309.4   36.31
  5349.4   38.32  5509.4   41.68  5549.4   41.32  5609.4   43.68  5782.7   45.82
#Mann= 6 ,-1 , 0
  4428.6     .08       0  4907.6     .04       0  4932.9     .04       0
  5099.2     .04       0  5188.6     .08       0  5269.4      .1       0
#XS Ineff= 5 ,-1
 4629.47  4748.7    40.8  4748.7 4818.72   39.52 4818.72  4922.9      33
  5109.2 5250.59      33 5252.29 5587.58   39.55
Permanent Ineff=
       F       F       F       F       F
Bank Sta=4932.9,5099.2
XS Rating Curve= 0
Exp/Cntr=.5,.3

Type RM Length L Ch R = 1 ,3952.   ,472,486,505.2
BEGIN DESCRIPTION:
struct 04 d/s of Main st-XS1
END DESCRIPTION:
XS GIS Cut Line= 4
      3121193.85     13850326.42      3120956.79     13850700.19
       3120910.1     13850981.94      3120431.86     13851411.63
#Sta/Elev= 30
  4416.8   49.44  4566.8   48.09  4859.4   42.86  4879.4    42.3  4889.4   40.73
  4899.4   38.24  4909.4   32.79 4938.87   28.68 4941.72   26.45 4962.53   18.17
  4983.2    11.3 4985.37    9.45 4991.72    7.63 5002.52    6.87 5038.91   11.31
 5055.39   15.81 5084.68   26.36 5089.42   29.12  5099.4   31.84  5109.4   36.49
  5129.4   39.94  5139.4   40.79    5305   41.61    5375    41.2    5425   43.04
    5495   42.18    5515   41.09    5545    41.5    5605   44.06  5787.9    45.5
#Mann= 5 ,-1 , 0
  4416.8     .08       0  4859.4     .05       0 4938.87     .04       0
 5089.42     .05       0    5545     .08       0
Bank Sta=4938.87,5089.42
XS Rating Curve= 0
Exp/Cntr=.3,.1

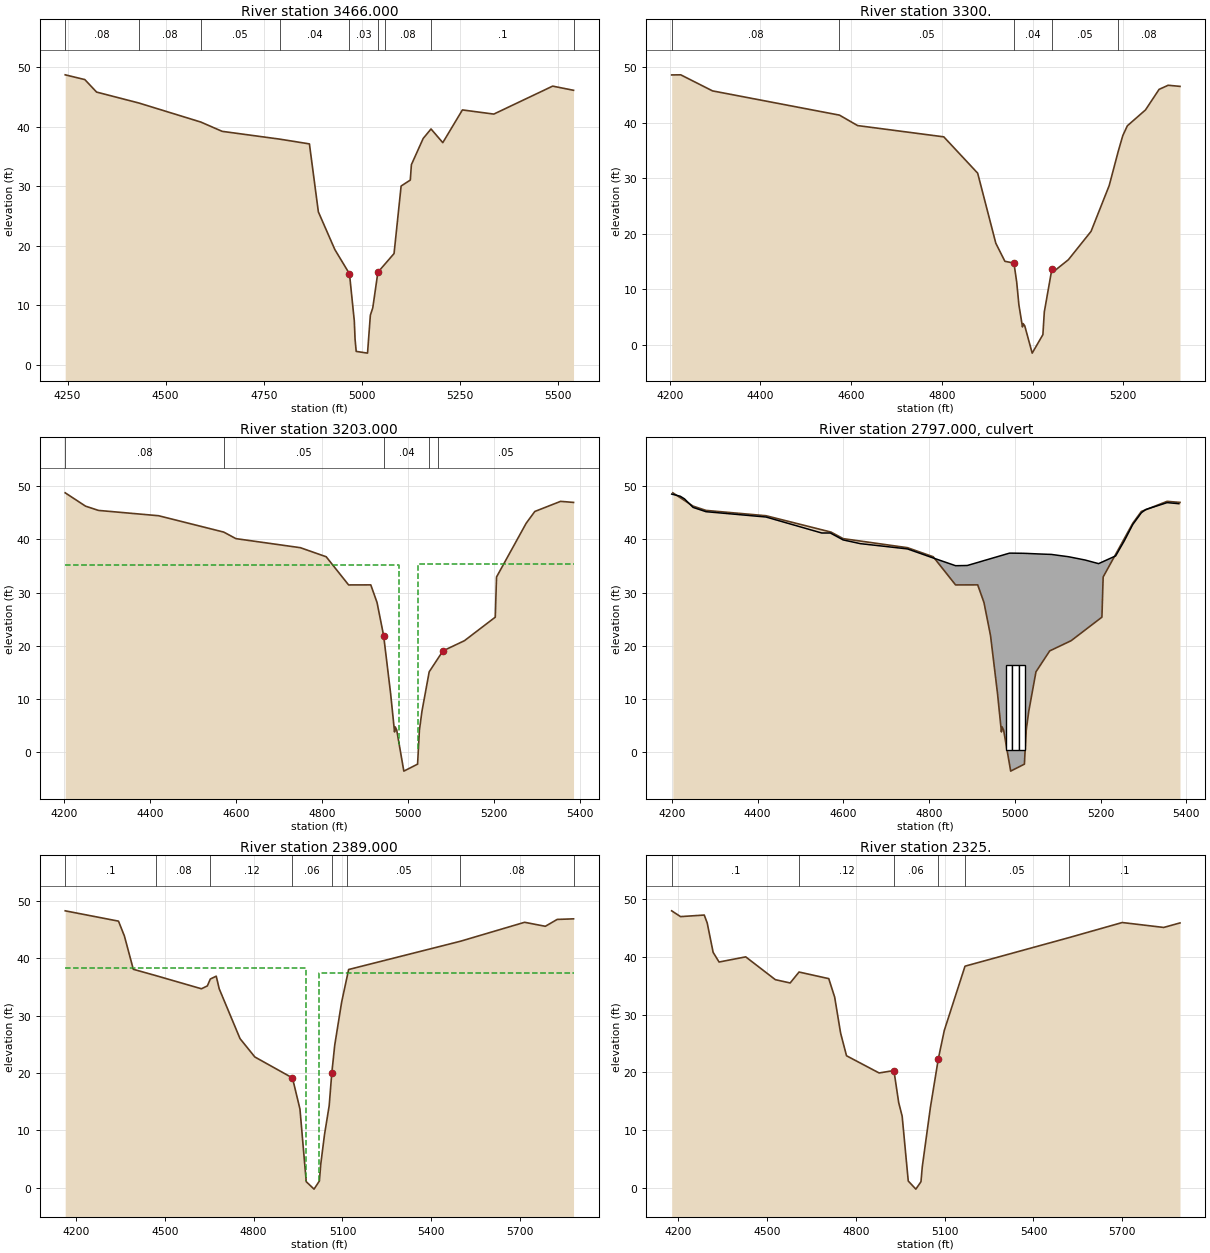
Type RM Length L Ch R = 1 ,3466.000,93,166,193.6
BEGIN DESCRIPTION:
Cross Section Xsec 2a
END DESCRIPTION:
XS GIS Cut Line= 3
       3120951.8     13850333.72      3120507.71     13850608.63
       3120319.2     13851358.46
#Sta/Elev= 30
    4244    48.7    4294    47.9    4324    45.8  4431.9   43.96  4589.7   40.76
    4644    39.2  4790.7   37.89  4866.4   37.09  4889.2   25.66  4931.2   19.33
  4968.5   15.25  4980.8    7.32  4982.7    4.29  4985.6    2.21  5014.5    1.92
  5021.7    8.29  5027.9    9.55  5040.9   15.52  5058.4   16.85  5082.1   18.66
  5100.1   30.01  5123.5   31.01  5126.3    33.6  5156.3      38  5176.3    39.6
  5206.3    37.3  5256.3    42.8  5336.3    42.1  5486.3    46.8  5539.5    46.1
#Mann= 9 ,-1 , 0
    4244     .08       0  4431.9     .08       0  4589.7     .05       0
  4790.7     .04       0  4968.5     .03       0  5040.9     .04       0
  5058.4     .08       0  5176.3      .1       0  5539.5      .1       0
#XS Ineff= 2 , 0
                         5176.36           39.52
Permanent Ineff=
       F       F
Bank Sta=4968.5,5040.9
XS Rating Curve= 0
Exp/Cntr=.3,.1

Type RM Length L Ch R = 1 ,3300.   ,37.1,97,132.5
BEGIN DESCRIPTION:
U/S Structure 3 at I45 N-XS4
END DESCRIPTION:
XS GIS Cut Line= 3
      3120962.75       13850311.      3120385.26     13850659.94
      3120109.95     13851010.92
#Sta/Elev= 30
  4204.2    48.6  4224.2   48.62  4294.2   45.73  4574.2   41.36  4614.2   39.48
  4804.2   37.45  4878.9   30.91  4918.9   18.29  4938.9   15.04  4958.9   14.71
 4964.94    11.3  4969.8    7.19 4977.67    3.22 4979.26    3.81 4982.73    3.41
  4999.1    -1.5 5022.72    1.83 5025.82    5.92 5042.65    13.7  5048.9   13.36
  5078.9   15.32  5128.9   20.43  5168.9   28.68  5188.9   34.86  5198.9   37.68
  5208.9   39.44  5248.9    42.3  5278.9      46  5298.9   46.74    5325   46.54
#Mann= 5 ,-1 , 0
  4204.2     .08       0  4574.2     .05       0  4958.9     .04       0
 5042.65     .05       0  5188.9     .08       0
Bank Sta=4958.9,5042.65
XS Rating Curve= 0
Exp/Cntr=.5,.3

Type RM Length L Ch R = 1 ,3203.000,956.3,814,720.8
BEGIN DESCRIPTION:
I45 EAST & WEST ENDS u/s
Upstream Section of Bridge/Culvert/Weir
END DESCRIPTION:
XS GIS Cut Line= 5
       3120938.6      13850262.7      3120351.41      13850639.4
      3120185.56     13850706.36      3120100.73     13850840.85
      3120093.81      13850988.1
#Sta/Elev= 30
  4202.1   48.74  4249.4   46.24  4279.4   45.44  4419.4   44.44    4571   41.37
  4599.4   40.14  4749.4   38.44  4809.4   36.74  4861.6   31.45  4913.2   31.46
  4927.8   28.14  4943.1   21.93  4959.3   11.11  4968.5    3.85  4970.1     4.8
  4973.6    4.19  4990.1    -3.5  5022.1   -2.19  5026.3    4.15  5032.2    7.69
  5049.1   15.14  5070.3   17.74  5081.2   19.07  5131.1   20.98  5202.9    25.4
  5205.8   32.94  5274.9   43.04  5294.9   45.24  5354.9   47.14    5385   46.94
#Mann= 5 ,-1 , 0
  4202.1     .08       0    4571     .05       0  4943.1     .04       0
  5049.1     .08       0  5070.3     .05       0
#XS Ineff= 2 ,-1
    5024    5385   35.46  4202.1  4979.5   35.11
Permanent Ineff=
       F       F
Bank Sta=4943.1,5081.2
XS Rating Curve= 0
Exp/Cntr=.5,.3

Type RM Length L Ch R = 2 ,2797.000,,,
BEGIN DESCRIPTION:
I45 EAST & WEST ENDS
Structure ID: E101-00-00-03
END DESCRIPTION:
Bridge Culvert--1,0,-1,-1, 0
Deck Dist Width WeirC Skew NumUp NumDn MinLoCord MaxHiCord MaxSubmerge Is_Ogee
10,792,2.6,0, 47, 8, , , .95, 0, ,,,
  4199.4  4219.4  4229.4  4235.1  4249.4  4279.4  4419.4  4549.4  4569.4    4571
  4599.4  4639.4  4690.9  4749.4  4809.4  4861.6  4888.8  4913.2  4927.8  4943.1
  4947.3  4959.3  4968.5  4970.1  4973.6  4987.4  4990.1  5019.4  5022.1  5026.3
  5032.2  5049.1  5051.8  5070.3  5081.2  5084.8  5125.4  5131.1  5163.6  5195.1
  5234.9  5254.9  5274.9  5294.9  5304.9  5354.9  5382.3
    48.5    48.1    47.6   47.14      46    45.2    44.2    41.2    41.2   41.13
    39.9    39.2   38.74   38.21   36.51   35.06    35.1   35.67   36.02   36.38
   36.48   36.76   36.98   37.01    37.1   37.42   37.42   37.39   37.38   37.37
   37.35   37.29   37.28   37.22   37.19   37.18   36.74   36.65   36.13   35.45
    36.9    39.7    42.8      45    45.6    46.9    46.7
                                                                                
                                                                                
                                                                                
                                                                                
                                                        
    4140    4365    4439    4573    4730    5046    5305    5392
      46      46      44      42      40      38      36      36
                                                                
BR Coef= 1 , 1 , 1 ,1.25, 0 ,,,.8,0,2,0,
WSPro=,,,, 1 ,,,, 0 ,,,, 0 ,,,,-1 ,-1 ,-1 , 0 , 0 , 0 , 0 , 0
Culvert=2,16,14.1,792,.015,.5,1,8,2,.45,4986.7,-.37,4984.7,Culvert #1  , 0 ,10
Culvert Bottom n=.015
Culvert=2,16,15,792,.015,.5,1,8,2,.45,5001.8,-.37,4999.8,Culvert #2  , 0 ,10
Culvert Bottom n=.015
Culvert=2,16,14.1,792,.015,.5,1,8,2,.45,5017,-.37,5015,Culvert #3  , 0 ,10
Culvert Bottom n=.015
BC Design=,, 0 ,, 0 ,,,,,,
BC HTab HWMax=48.74

Type RM Length L Ch R = 1 ,2389.000,63.2,64,65.2
BEGIN DESCRIPTION:
I45 EAST & WEST ENDS
Cross Section x2
END DESCRIPTION:
XS GIS Cut Line= 4
       3120595.4      13849478.2      3120098.11     13849631.24
      3119942.02     13850138.52      3119631.18     13850726.42
#Sta/Elev= 30
    4164    48.3  4343.9    46.5  4363.9    43.9  4393.9    38.1  4471.9   36.97
  4623.9    34.7  4643.9    35.2  4653.9    36.4  4673.9    36.9  4683.9    34.7
  4754.2      26  4804.2    22.8  4931.2   19.14  4956.5   13.72  4977.7    1.04
  5004.1    -.26  5022.1    1.16  5026.7    4.08  5039.5    9.29  5055.2    14.3
  5063.9   19.94    5074    24.9  5097.2   32.36  5114.2   36.45  5120.9   38.06
  5498.2   42.99  5714.9    46.3  5784.9    45.6  5824.9    46.8  5880.1    46.9
#Mann= 8 ,-1 , 0
    4164      .1       0  4471.9     .08       0  4653.9     .12       0
  4931.2     .06       0  5063.9     .12       0  5114.2     .05       0
  5498.2     .08       0  5880.1      .1       0
#XS Ineff= 2 , 0
       0  4977.6    38.4 5022.12       0   37.37
Permanent Ineff=
       F       F
Bank Sta=4931.2,5063.9
XS Rating Curve= 0
Exp/Cntr=.5,.3

Type RM Length L Ch R = 1 ,2325.   ,171.3,470,448.8
BEGIN DESCRIPTION:
D/S Structure 3 at I45 N-XS1
END DESCRIPTION:
XS GIS Cut Line= 4
      3120532.61     13849466.93      3120035.32     13849619.97
      3119879.23     13850127.25      3119568.39     13850715.15
#Sta/Elev= 30
  4178.6   47.91  4208.6   46.91  4288.6   47.18  4298.6   45.81  4318.6   40.74
  4338.6   39.07  4428.6   39.96  4528.6   36.02  4578.6   35.45  4608.6   37.34
  4708.9    36.2  4728.9      33  4748.9    26.8  4768.9   22.88  4878.9   19.91
  4928.9   20.33 4945.04   14.79 4956.71   12.45  4977.3    1.25 5002.94    -.15
 5020.23    1.13 5024.65    3.71 5052.04   13.96  5078.9   22.38  5098.9   27.24
  5168.9   38.35  5519.7   43.28  5699.7   45.89  5839.7   45.04  5894.7   45.82
#Mann= 6 ,-1 , 0
  4178.6      .1       0  4608.6     .12       0  4928.9     .06       0
  5078.9     .12       0  5168.9     .05       0  5519.7      .1       0
Bank Sta=4928.9,5078.9
XS Rating Curve= 0
Exp/Cntr=.3,.1