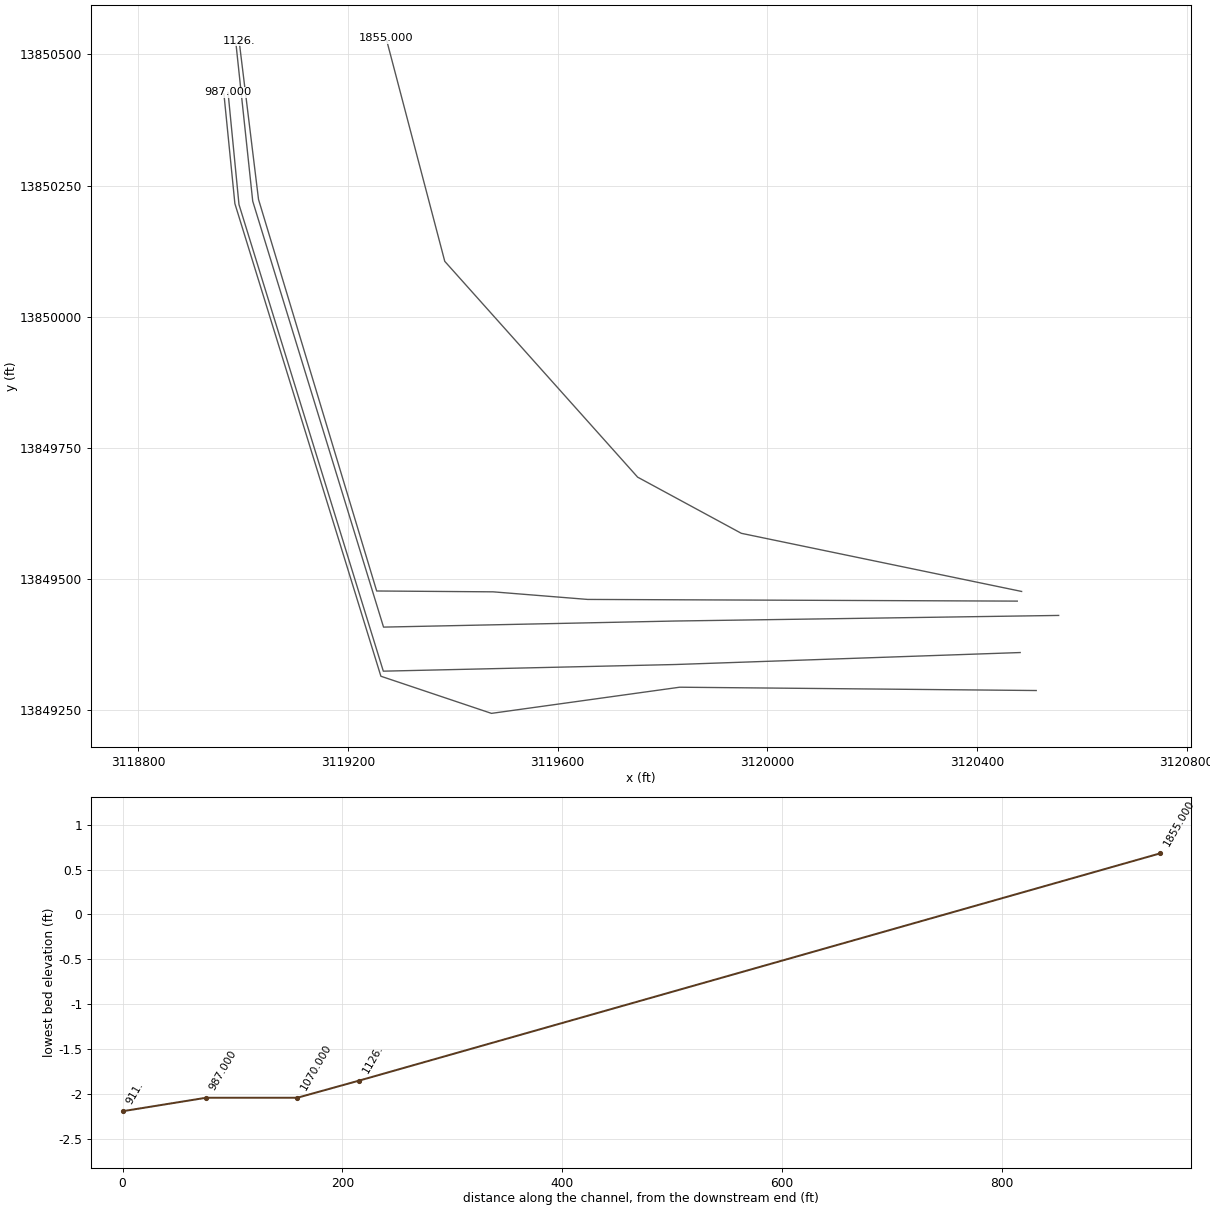
HEC-RAS study E101_00_00.prj: E101-00-00

--- E101_00_00.g01 (geometry) --- (continued)

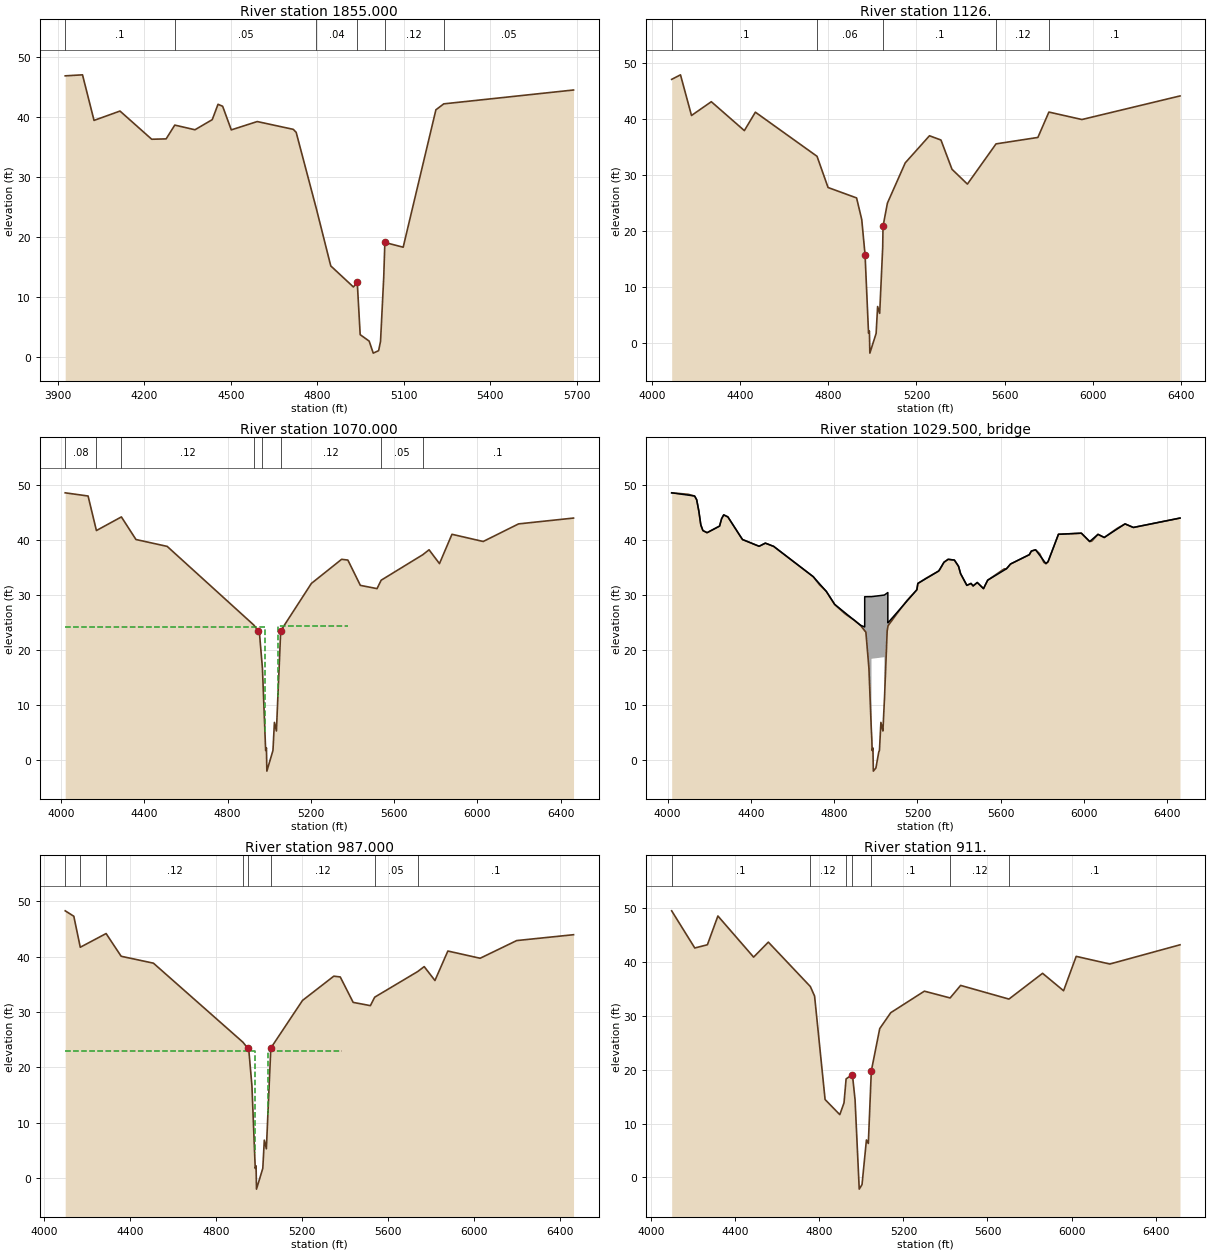
Type RM Length L Ch R = 1 ,1855.000,205.4,729,602.2
BEGIN DESCRIPTION:
Cross Section x1
END DESCRIPTION:
XS GIS Cut Line= 5
       3120485.3     13849475.76      3119950.65     13849586.65
      3119752.85     13849693.78      3119384.96     13850105.45
      3119273.16     13850530.83
#Sta/Elev= 30
  3926.1   46.91  3986.1   47.08  4026.1   39.48  4116.1   41.04  4226.1   36.34
  4276.1    36.4  4306.1    38.7  4376.1   37.92  4436.1   39.61  4456.1   42.17
  4472.1   41.84  4502.1    37.9  4592.1   39.29  4717.1   37.99  4727.1   37.49
  4797.1   24.76  4847.1   15.22  4925.6   11.71    4939   12.47  4949.1    3.76
  4980.3    2.68  4994.4     .68    5013    1.09  5019.7    2.65  5030.8   13.37
  5034.7   19.13  5098.2   18.34  5211.7   41.25    5239   42.24    5689   44.55
#Mann= 6 ,-1 , 0
  3926.1      .1       0  4306.1     .05       0  4797.1     .04       0
    4939     .06       0  5034.7     .12       0    5239     .05       0
Bank Sta=4939,5034.7
XS Rating Curve= 0
Exp/Cntr=.3,.1

Type RM Length L Ch R = 1 ,1126.   ,43.1,56,72.6
BEGIN DESCRIPTION:
US structure no 4 WrightWood St.-XS4
END DESCRIPTION:
XS GIS Cut Line= 6
      3120477.03     13849457.31      3119657.56     13849460.53
      3119477.24     13849475.02      3119255.07     13849476.63
      3119029.67     13850223.65      3118992.64     13850526.32
#Sta/Elev= 30
  4088.9   47.03  4128.9   47.84  4178.9   40.58  4268.9   43.04  4418.9   37.88
  4468.9   41.17  4748.9   33.29  4798.9   27.72  4928.4   25.86 4951.89   21.99
 4966.94   15.67 4982.71     1.7  4986.6    2.09 4988.64   -1.85 5017.12    1.67
 5023.92    6.47 5033.25    5.25 5047.02   17.08  5048.4   20.77  5068.4   24.94
  5149.3   32.12  5259.3   36.96  5311.5    36.2  5361.5   30.98  5431.5   28.33
  5561.5   35.51  5751.5   36.66  5801.5   41.19  5951.5   39.86  6396.7   44.07
#Mann= 5 ,-1 , 0
  4088.9      .1       0  4748.9     .06       0  5048.4      .1       0
  5561.5     .12       0  5801.5      .1       0
Bank Sta=4966.94,5048.4
XS Rating Curve= 0
Exp/Cntr=.5,.3

Type RM Length L Ch R = 1 ,1070.000,82.8,83,90.6
BEGIN DESCRIPTION:
WRIGHTWOOD u/s
Upstream Section of Bridge/Culvert/Weir
END DESCRIPTION:
XS GIS Cut Line= 5
      3120555.95       13849430.      3119823.44     13849419.33
      3119268.17     13849407.74      3119018.63     13850220.22
      3118986.45     13850522.47
#Sta/Elev= 30
  4019.5   48.57  4129.4   47.99  4169.4   41.71  4289.4   44.19  4359.4   40.08
  4509.4   38.83  4925.1   24.54 4946.59    23.5  4952.3   23.23    4967   16.65
  4982.4    1.71  4986.2    2.18  4988.2   -2.04  5017.5    1.72  5024.5    6.82
  5034.1    5.26  5054.7   23.47    5202   32.09  5347.4   36.48  5377.4   36.34
  5437.4   31.74  5517.4   31.15  5537.4   32.68  5737.4   37.32  5767.4   38.21
  5817.4    35.7  5877.4   41.03  6027.4   39.72  6197.3   42.92  6461.4   43.98
#Mann= 8 ,-1 , 0
  4019.5     .08       0  4169.4     .05       0  4289.4     .12       0
  4925.1     .04       0    4967     .06       0  5054.7     .12       0
  5537.4     .05       0  5737.4      .1       0
#XS Ineff= 3 ,-1
 5379.04 5641.06   34.78    5041 5379.04   24.39  4019.5  4979.5   24.08
Permanent Ineff=
       F       F       F
Bank Sta=4946.59,5054.7
XS Rating Curve= 0
Exp/Cntr=.5,.3

Type RM Length L Ch R = 3 ,1029.500,,,
BEGIN DESCRIPTION:
WRIGHTWOOD
Structure ID: E101-00-00-02
END DESCRIPTION:
Bridge Culvert--1,0,-1,-1, 0
Deck Dist Width WeirC Skew NumUp NumDn MinLoCord MaxHiCord MaxSubmerge Is_Ogee
10,61,2.6,0, 60, 60, , , .95, 0, ,,,
  4019.4  4129.4  4139.4  4149.4  4159.4  4169.4  4189.4  4249.4  4259.4  4269.4
  4289.4  4359.4  4439.4  4469.4  4509.4  4699.4    4762  4802.5  4925.1 4946.59
  4946.7  4952.3    4967 4979.43  4979.5 5040.99  5041.1  5054.7  5057.8 5057.91
  5058.8  5197.3    5202    5302  5327.4  5347.4  5377.4  5397.4  5407.4  5437.4
  5457.4  5467.4  5487.4  5517.4  5537.4  5627.4  5647.4  5737.4  5747.4  5767.4
  5817.4  5827.4  5877.4  5987.4  6027.4  6067.4  6097.4  6197.3  6237.3  6461.3
   48.57   47.99   47.32   45.35   42.74   41.71   41.32   42.52   43.88   44.56
   44.19   40.08   38.85   39.42   38.83   33.32   30.66   28.29   24.52   24.18
   29.68   29.68   29.69   29.69   29.69   29.98   29.98   30.35   30.43   24.93
   24.95   30.94   32.09   34.35   35.94   36.48   36.34   35.21   33.86   31.74
   32.09   31.64   32.26   31.15   32.68   34.75   35.63   37.32   37.98   38.21
    35.7   36.04   41.03   41.23   39.72   41.02   40.45   42.92   42.27   43.98
   48.57   47.99   47.32   45.35   42.74   41.71   41.32   42.52   43.88   44.56
   44.19   40.08   38.85   39.42   38.83   33.32   30.66   28.22   24.51   23.47
   23.47    23.2   16.62    4.83   18.39   18.68   10.66   23.44   24.09   24.12
   24.36   30.93   32.09   34.35   35.94   36.48   36.34   35.21   33.86   31.74
   32.09   31.64   32.26   31.15   32.68   34.75   35.63   37.32   37.98   38.21
    35.7   36.04   41.03   41.23   39.72   41.02   40.45   42.92   42.27   43.98
  4019.4  4129.4  4139.4  4149.4  4159.4  4169.4  4189.4  4249.4  4259.4  4269.4
  4289.4  4359.4  4439.4  4469.4  4509.4  4699.4    4762  4802.5  4925.1 4946.59
  4946.7  4952.3    4967 4979.43  4979.5 5040.99  5041.1  5054.7  5057.8 5057.91
  5058.8  5197.3    5202    5302  5327.4  5347.4  5377.4  5397.4  5407.4  5437.4
  5457.4  5467.4  5487.4  5517.4  5537.4  5627.4  5647.4  5737.4  5747.4  5767.4
  5817.4  5827.4  5877.4  5987.4  6027.4  6067.4  6097.4  6197.3  6237.3  6461.3
   48.57   47.99   47.32   45.35   42.74   41.71   41.32   42.52   43.88   44.56
   44.19   40.08   38.85   39.42   38.83   33.32   30.66   28.29   24.52   24.18
   29.68   29.68   29.69   29.69   29.69   29.98   29.98   30.35   30.43   24.93
   24.95   30.94   32.09   34.35   35.94   36.48   36.34   35.21   33.86   31.74
   32.09   31.64   32.26   31.15   32.68   34.75   35.63   37.32   37.98   38.21
    35.7   36.04   41.03   41.23   39.72   41.02   40.45   42.92   42.27   43.98
   48.57   47.99   47.32   45.35   42.74   41.71   41.32   42.52   43.88   44.56
   44.19   40.08   38.85   39.42   38.83   33.32   30.66   28.22   24.51   23.47
   23.47    23.2   16.62    4.83   18.39   18.68   10.66   23.44   24.09   24.12
   24.36   30.93   32.09   34.35   35.94   36.48   36.34   35.21   33.86   31.74
   32.09   31.64   32.26   31.15   32.68   34.75   35.63   37.32   37.98   38.21
    35.7   36.04   41.03   41.23   39.72   41.02   40.45   42.92   42.27   43.98
BR Coef= 1 , 1 , 0 ,1.25, 0 ,,,.8,0,2,0,
WSPro=,,,, 1 ,,,, 0 ,,,, 0 ,,,,-1 ,-1 ,-1 , 0 , 0 , 0 , 0 , 0
BR U #Sta/Elev= 102
  4019.4   48.57  4099.4    48.3  4129.4   47.99  4139.4   47.32  4149.4   45.35
  4159.4   42.74  4169.4   41.71  4189.4   41.32  4249.4   42.52  4259.4   43.88
  4269.4   44.56  4289.4   44.19  4359.4   40.08  4439.4   38.85  4469.4   39.42
  4509.4   38.83  4699.4   33.32  4729.4   31.87    4762   30.66  4800.9   28.34
  4802.5   28.25  4835.1   27.16  4849.9   26.66  4855.1   26.49  4888.6   25.62
  4897.7   25.38    4925   24.54  4925.1   24.54  4927.2   24.43 4946.59    23.5
  4946.7    23.5 4946.81   23.49  4952.3   23.23    4958   20.69    4967   16.65
  4978.2    5.78 4979.31    4.95 4979.43    4.86  4979.5    4.81    4981    3.69
  4982.4    1.71  4984.8    2.01  4986.2    2.18  4988.2   -2.04  5000.5   -1.47
  5014.2    1.43  5017.5    1.72  5024.5    6.82  5034.1    5.26  5034.7    5.73
  5034.9    5.88 5040.99    10.6  5041.1   10.69  5041.8   11.23  5054.7   23.47
  5057.6   24.07 5057.69   24.09  5057.8   24.12 5057.91   24.15  5058.8   24.39
  5072.3   25.09  5105.7   26.81    5109   26.97  5149.6   28.98    5150      29
  5192.5   30.75  5197.3   30.96    5202   32.09    5242   33.05    5302   34.35
  5307.4    34.6  5327.4   35.94  5347.4   36.48  5377.4   36.34  5397.4   35.21
  5407.4   33.86  5437.4   31.74  5457.4   32.09  5467.4   31.64  5487.4   32.26
  5517.4   31.15  5537.4   32.68  5617.4   34.75  5627.4   34.75  5647.4   35.63
  5737.4   37.32  5747.4   37.98  5767.4   38.21  5787.4   37.48  5807.4   35.91
  5817.4    35.7  5827.4   36.04  5877.4   41.03  5987.4   41.23  6027.4   39.72
  6037.4   39.78  6067.4   41.02  6097.4   40.45  6157.3   42.05  6197.3   42.92
  6237.3   42.27  6461.3   43.98
BR U #Mann= 8
  4019.4     .08  4169.4     .05  4289.4     .12  4925.1     .04    4967     .05
  5054.7     .12  5537.4     .05  5737.4     .99
BR D #Sta/Elev= 102
  4019.4   48.57  4099.4    48.3  4129.4   47.99  4139.4   47.32  4149.4   45.35
  4159.4   42.74  4169.4   41.71  4189.4   41.32  4249.4   42.52  4259.4   43.88
  4269.4   44.56  4289.4   44.19  4359.4   40.08  4439.4   38.85  4469.4   39.42
  4509.4   38.83  4699.4   33.32  4729.4   31.87    4762   30.66  4800.9   28.34
  4802.5   28.25  4835.1   27.16  4849.9   26.66  4855.1   26.49  4888.6   25.62
  4897.7   25.38    4925   24.54  4925.1   24.54  4927.2   24.43 4946.59    23.5
  4946.7    23.5 4946.81   23.49  4952.3   23.23    4958   20.69    4967   16.65
  4978.2    5.78 4979.31    4.95 4979.43    4.86  4979.5    4.81    4981    3.69
  4982.4    1.71  4984.8    2.01  4986.2    2.18  4988.2   -2.04  5000.5   -1.47
  5014.2    1.43  5017.5    1.72  5024.5    6.82  5034.1    5.26  5034.7    5.73
  5034.9    5.88 5040.99    10.6  5041.1   10.69  5041.8   11.23  5054.7   23.47
  5057.6   24.07 5057.69   24.09  5057.8   24.12 5057.91   24.15  5058.8   24.39
  5072.3   25.09  5105.7   26.81    5109   26.97  5149.6   28.98    5150      29
  5192.5   30.75  5197.3   30.96    5202   32.09    5242   33.05    5302   34.35
  5307.4    34.6  5327.4   35.94  5347.4   36.48  5377.4   36.34  5397.4   35.21
  5407.4   33.86  5437.4   31.74  5457.4   32.09  5467.4   31.64  5487.4   32.26
  5517.4   31.15  5537.4   32.68  5617.4   34.75  5627.4   34.75  5647.4   35.63
  5737.4   37.32  5747.4   37.98  5767.4   38.21  5787.4   37.48  5807.4   35.91
  5817.4    35.7  5827.4   36.04  5877.4   41.03  5987.4   41.23  6027.4   39.72
  6037.4   39.78  6067.4   41.02  6097.4   40.45  6157.3   42.05  6197.3   42.92
  6237.3   42.27  6461.3   43.98
BR D #Mann= 8
  4019.4     .08  4169.4     .05  4289.4     .12  4925.1     .04    4967     .05
  5054.7     .12  5537.4     .05  5737.4     .99
BC Design=,, 0 ,, 0 ,,,,,,
BC HTab HWMax=48.57

Type RM Length L Ch R = 1 ,987.000 ,56.2,76,62.1
BEGIN DESCRIPTION:
WRIGHTWOOD
Downstream Section of Bridge/Culvert/Weir
END DESCRIPTION:
XS GIS Cut Line= 5
 3120482.571364113849359.2289353      3119825.08     13849336.39
      3119267.74     13849323.69      3118992.42     13850213.82
 3118971.559717313850427.5721094
#Sta/Elev= 30
  4099.4    48.3  4139.4   47.32  4169.4   41.71  4289.4   44.19  4359.4   40.08
  4509.4   38.83  4925.1   24.54 4946.59    23.5  4952.3   23.23    4967   16.65
  4982.4    1.71  4986.2    2.18  4988.2   -2.04  5017.5    1.72  5024.5    6.82
  5034.1    5.26  5054.7   23.47    5202   32.09  5347.4   36.48  5377.4   36.34
  5437.4   31.74  5517.4   31.15  5537.4   32.68  5737.4   37.32  5767.4   38.21
  5817.4    35.7  5877.4   41.03  6027.4   39.72  6197.3   42.92  6461.3   43.98
#Mann= 8 ,-1 , 0
  4099.4     .08       0  4169.4     .05       0  4289.4     .12       0
  4925.1     .04       0 4946.59     .06       0  5054.7     .12       0
  5537.4     .05       0  5737.4      .1       0
#XS Ineff= 3 ,-1
 5384.95 5656.82   34.78    5041 5384.95      23  4099.4  4979.5      23
Permanent Ineff=
       F       F       F
Bank Sta=4946.59,5054.7
XS Rating Curve= 0
Exp/Cntr=.5,.3

Type RM Length L Ch R = 1 ,911.    ,162.6,155,86.9
BEGIN DESCRIPTION:
DS structure no 4 WrightWood St.-XS1
END DESCRIPTION:
XS GIS Cut Line= 6
      3120513.16     13849286.77      3119833.04     13849293.09
      3119474.02     13849243.18      3119263.12     13849314.02
      3118984.59      13850215.6      3118963.67     13850424.89
#Sta/Elev= 30
  4097.2   49.56  4207.2   42.65  4267.2   43.25  4317.2    48.6  4487.2   40.95
  4557.2   43.74  4757.2   35.48  4777.3   33.71  4827.3   14.47  4897.3   11.66
  4917.3   13.84  4927.3   18.31  4957.3   19.11 4969.92   14.44 4989.81   -2.19
  5003.1   -1.34 5024.04    6.95  5033.1     6.3  5047.3   19.78  5087.3   27.66
  5139.8   30.62  5299.8   34.62  5422.3   33.36  5472.3   35.69  5702.3   33.15
  5862.3   37.94  5962.3    34.7  6022.3   41.09  6182.3   39.67  6516.3   43.24
#Mann= 7 ,-1 , 0
  4097.2      .1       0  4757.2     .12       0  4927.3     .04       0
  4957.3     .06       0  5047.3      .1       0  5422.3     .12       0
  5702.3      .1       0
Bank Sta=4957.3,5047.3
XS Rating Curve= 0
Exp/Cntr=.3,.1