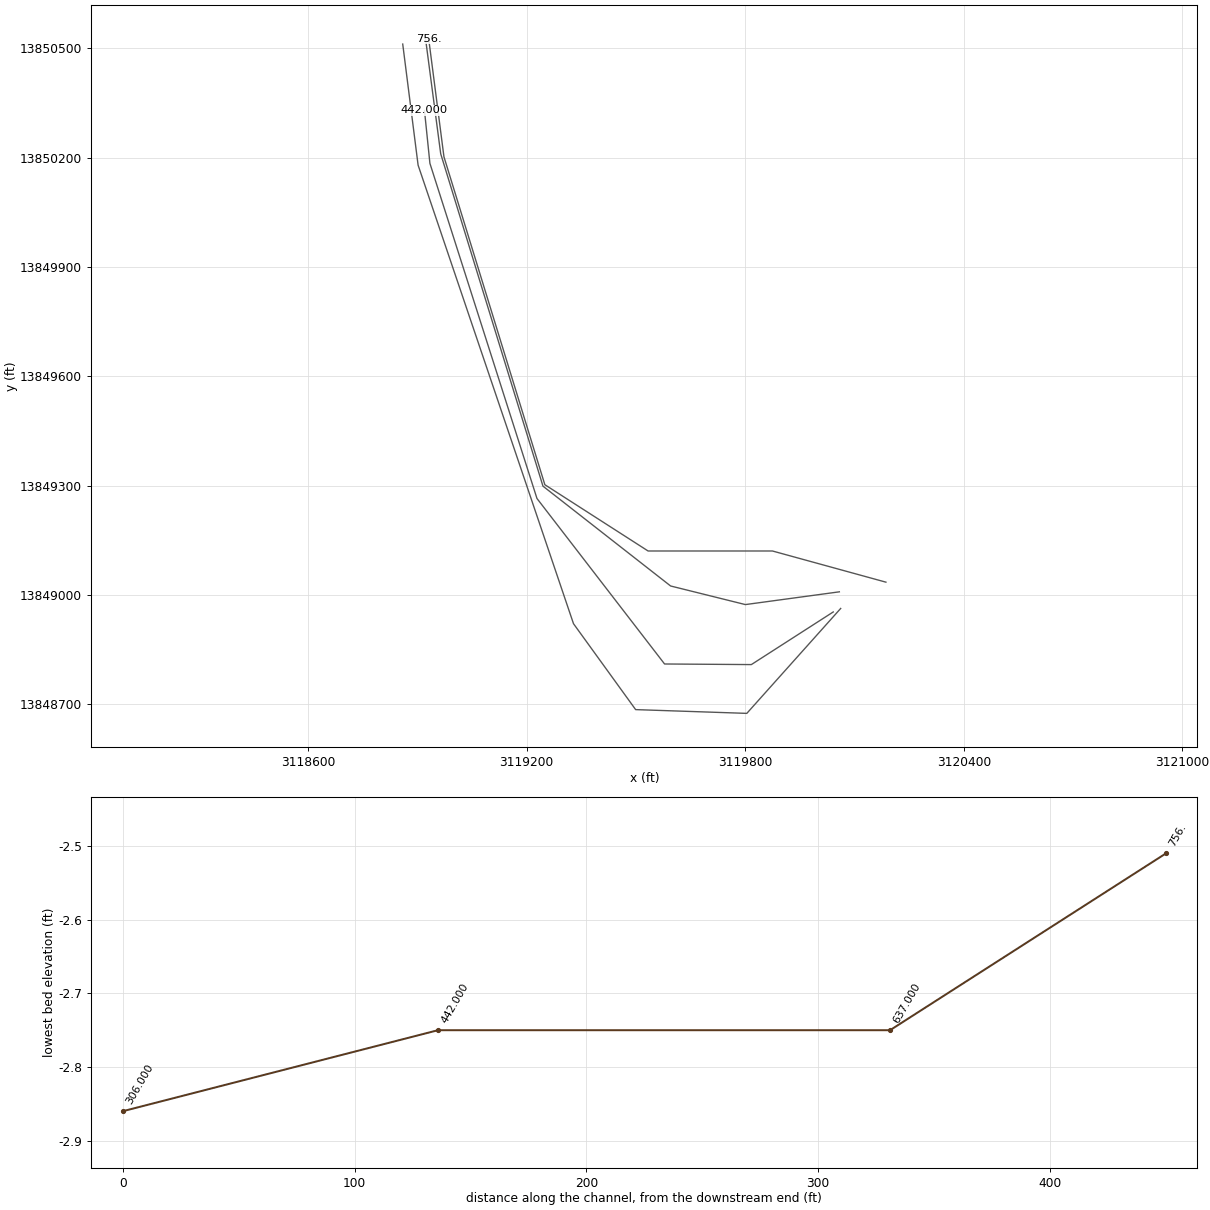
HEC-RAS study E101_00_00.prj: E101-00-00

--- E101_00_00.g01 (geometry) --- (continued)

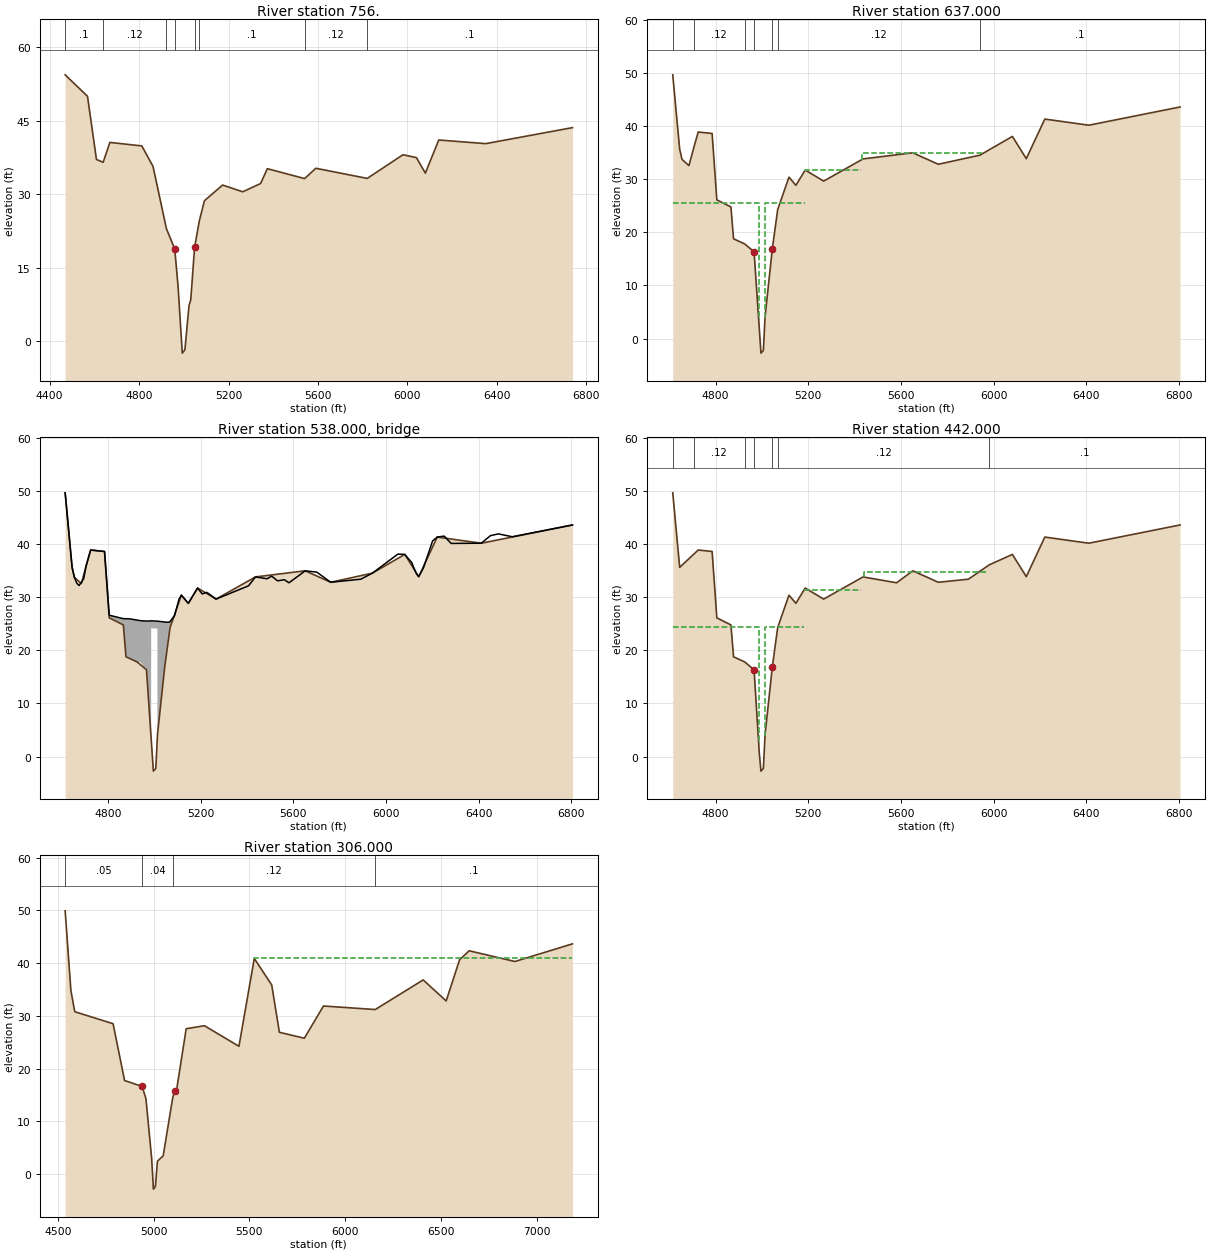
Type RM Length L Ch R = 1 ,756.    ,139,119,33.2
BEGIN DESCRIPTION:
struc 1 u/s of White Oak Rd-XS4
END DESCRIPTION:
XS GIS Cut Line= 6
      3120186.34     13849035.28       3119874.9     13849120.83
      3119533.59     13849120.83      3119250.24     13849302.75
      3118973.32     13850202.72      3118931.47     13850526.32
#Sta/Elev= 30
  4469.2    54.4  4569.2   50.01  4609.2   37.09  4639.2   36.52  4669.2   40.58
  4812.2   39.86  4862.2   35.67  4922.2   22.93 4959.33   18.78 4974.11   11.22
 4993.08   -2.51 5004.74   -1.85 5023.12    7.21 5031.06    8.43  5048.1   19.15
 5069.62   24.59  5092.2   28.66  5173.5   31.86  5263.5   30.48  5343.5   32.18
  5373.5   35.21  5540.2   33.18  5590.2   35.29  5820.2   33.22  5980.2   38.06
  6040.2   37.47  6080.2    34.3  6140.2   41.07  6350.2   40.33  6738.1    43.6
#Mann= 8 ,-1 , 0
  4469.2      .1       0  4639.2     .12       0  4922.2     .04       0
 4959.33     .05       0  5048.1     .04       0 5069.62      .1       0
  5540.2     .12       0  5820.2      .1       0
Bank Sta=4959.33,5048.1
XS Rating Curve= 0
Exp/Cntr=.5,.3

Type RM Length L Ch R = 1 ,637.000 ,180.1,195,135.6
BEGIN DESCRIPTION:
QUITMAN/WHITE OAK DRIVE u/s
Upstream Section of Bridge/Culvert/Weir
END DESCRIPTION:
XS GIS Cut Line= 6
      3120058.55     13849008.77      3119800.63     13848973.75
      3119595.39      13849024.8      3119245.05     13849298.83
      3118964.44     13850210.82      3118922.62     13850527.85
#Sta/Elev= 30
  4614.7   49.71  4644.7   35.66  4654.7   33.77  4684.7    32.6  4704.7   35.85
  4724.7   38.93  4784.7   38.65  4805.1   26.14  4865.9   24.81  4877.3    18.8
  4925.9   17.82  4965.9   16.35  4995.6   -2.75    5006   -2.24  5013.5    4.18
  5044.7   16.92  5067.8   24.31  5116.5   30.42  5146.5   28.88  5186.5   31.76
  5266.5   29.68  5436.5   33.86  5651.3   35.01  5761.3   32.85  5941.3   34.57
  6081.3    38.1  6141.3   33.91  6221.3   41.37  6411.3   40.21  6805.2   43.65
#Mann= 7 ,-1 , 0
  4614.7      .1       0  4704.7     .12       0  4925.9     .04       0
  4965.9     .05       0  5044.7     .04       0  5067.8     .12       0
  5941.3      .1       0
#XS Ineff= 4 ,-1
 5431.84 5959.81      35 5183.61 5425.93   31.69  5013.1 5183.61    25.5
  4614.7    4986    25.5
Permanent Ineff=
       F       F       F       F
Bank Sta=4965.9,5044.7
XS Rating Curve= 0
Exp/Cntr=.5,.3

Type RM Length L Ch R = 3 ,538.000 ,,,
BEGIN DESCRIPTION:
QUITMAN/WHITE OAK DRIVE
Structure ID: E101-00-00-01
END DESCRIPTION:
Bridge Culvert--1,0,-1,-1, 0
Deck Dist Width WeirC Skew NumUp NumDn MinLoCord MaxHiCord MaxSubmerge Is_Ogee
10,178,2.6,0, 60, 60, , , .95, 0, ,,,
  4614.7  4644.7  4654.7  4664.7  4674.7  4694.7  4704.7  4724.7  4784.7  4805.1
  4865.2  4894.2  4938.9  4965.9  4978.9  4982.1 4986.01  4986.1 5013.09  5013.2
  5028.6  5044.7  5053.3  5065.4  5082.2  5086.5  5106.5  5116.5  5146.5  5186.5
  5206.5  5226.5  5266.5  5406.5  5436.5  5486.5  5506.5  5531.3  5561.3  5581.3
  5651.3  5701.3  5761.3  5891.3  5941.3  6051.3  6081.3  6111.3  6131.3  6141.3
  6161.3  6201.3  6221.3  6251.3  6281.3  6411.3  6451.3  6485.4  6545.4  6805.2
   49.71   35.66   33.77   32.68   32.23   33.51   35.85   38.93   38.65   26.64
      26   25.95   25.62   25.53   25.56   25.57   25.58   25.58   25.52   25.52
   25.44   25.36   25.32   25.33    26.3   26.48   29.68   30.42   28.88   31.76
   30.65   30.95   29.68   32.18   33.86   33.51   34.01   33.12   33.33   32.75
   35.01   34.76   32.85   33.43   34.57   38.16    38.1   36.56   34.44   33.91
   35.51   40.64   41.37   41.55   40.17   40.21   41.64   41.97   41.43   43.65
   49.71   35.66   33.77   32.68   32.23   33.51   35.85   38.93   38.65   26.03
      18   17.42   17.83   16.24     7.8    4.84    2.17   24.18   24.12    3.72
    9.55   16.81   19.73   23.85   26.29   26.48   29.68   30.42   28.88   31.76
   30.65   30.95   29.68   32.18   33.86   33.51   34.01   33.12   33.33   32.75
   35.01   34.76   32.85   33.43   34.57   38.16    38.1   36.56   34.44   33.91
   35.51   40.64   41.37   41.55   40.17   40.21   41.64   41.97   41.43   43.65
  4614.7  4644.7  4654.7  4664.7  4674.7  4694.7  4704.7  4724.7  4784.7  4805.1
  4865.2  4894.2  4938.9  4965.9  4978.9  4982.1 4986.01  4986.1 5013.09  5013.2
  5028.6  5044.7  5053.3  5065.4  5082.2  5086.5  5106.5  5116.5  5146.5  5186.5
  5206.5  5226.5  5266.5  5406.5  5436.5  5486.5  5506.5  5531.3  5561.3  5581.3
  5651.3  5701.3  5761.3  5891.3  5941.3  6051.3  6081.3  6111.3  6131.3  6141.3
  6161.3  6201.3  6221.3  6251.3  6281.3  6411.3  6451.3  6485.4  6545.4  6805.2
   49.71   35.66   33.77   32.68   32.23   33.51   35.85   38.93   38.65   26.64
      26   25.95   25.62   25.53   25.56   25.57   25.58   25.58   25.52   25.52
   25.44   25.36   25.32   25.33    26.3   26.48   29.68   30.42   28.88   31.76
   30.65   30.95   29.68   32.18   33.86   33.51   34.01   33.12   33.33   32.75
   35.01   34.76   32.85   33.43   34.57   38.16    38.1   36.56   34.44   33.91
   35.51   40.64   41.37   41.55   40.17   40.21   41.64   41.97   41.43   43.65
   49.71   35.66   33.77   32.68   32.23   33.51   35.85   38.93   38.65   26.03
      18   17.42   17.83   16.24     7.8    4.84    2.17   24.18   24.12    3.72
    9.55   16.81   19.73   23.85   26.29   26.48   29.68   30.42   28.88   31.76
   30.65   30.95   29.68   32.18   33.86   33.51   34.01   33.12   33.33   32.75
   35.01   34.76   32.85   33.43   34.57   38.16    38.1   36.56   34.44   33.91
   35.51   40.64   41.37   41.55   40.17   40.21   41.64   41.97   41.43   43.65
BR Coef= 1 , 1 , 0 ,1.25, 0 ,,,.8,0,2,0,
WSPro=,,,, 1 ,,,, 0 ,,,, 0 ,,,,-1 ,-1 ,-1 , 0 , 0 , 0 , 0 , 0
BC Design=,, 0 ,, 0 ,,,,,,
BC HTab HWMax=49.71

Type RM Length L Ch R = 1 ,442.000 ,101.7,136,137.3
BEGIN DESCRIPTION:
QUITMAN/WHITE OAK DRIVE
Downstream Section of Bridge/Culvert/Weir
END DESCRIPTION:
XS GIS Cut Line= 6
 3120041.823423513848953.5447019      3119816.98     13848809.07
      3119578.83     13848810.71      3119228.63     13849264.93
       3118934.8     13850184.71 3118919.865610713850329.9039756
#Sta/Elev= 30
  4614.7   49.71  4644.7   35.66  4724.7   38.93  4784.7   38.65  4805.1   26.14
  4865.9   24.81  4877.3    18.8  4925.9   17.82  4965.9   16.35  4988.4     .65
  4995.6   -2.75    5006   -2.24  5013.5    4.18  5044.7   16.92  5067.8   24.31
  5116.5   30.42  5146.5   28.88  5186.5   31.76  5266.5   29.68  5436.5   33.86
  5581.3   32.75  5651.3   35.01  5761.3   32.85  5891.3   33.43  5981.3   36.13
  6081.3    38.1  6141.3   33.91  6221.3   41.37  6411.3   40.21  6805.2   43.65
#Mann= 7 ,-1 , 0
  4614.7      .1       0  4704.7     .12       0  4925.9     .04       0
  4965.9     .05       0  5044.7     .04       0  5067.8     .12       0
  5981.3      .1       0
#XS Ineff= 4 ,-1
 5439.72  5973.6   34.78 5181.64 5425.93   31.47  5013.1 5181.64    24.5
  4614.7    4986    24.5
Permanent Ineff=
       F       F       F       F
Bank Sta=4965.9,5044.7
XS Rating Curve= 0
Exp/Cntr=.5,.3

Type RM Length L Ch R = 1 ,306.000 ,0,0,0
BEGIN DESCRIPTION:
Cross Section Xsec1a
END DESCRIPTION:
XS GIS Cut Line= 6
  3120062.17910413848963.1404616      3119804.56     13848675.16
      3119499.43     13848685.49      3119328.87     13848921.31
      3118902.38     13850179.79 3118860.179995613850512.1211443
#Sta/Elev= 30
  4538.8   49.92  4568.8    34.8  4588.8   30.79  4788.8   28.51  4848.8   17.74
  4940.2   16.61  4960.2   14.31  4990.2    2.92  4999.2   -2.86  5009.6   -2.35
  5020.2    2.44  5050.2    3.45  5100.2   14.53  5110.2   15.82  5120.2   15.95
  5170.2   27.56  5265.5   28.13  5445.5   24.23  5525.5   40.89  5616.5   35.85
  5656.5   26.88  5786.5   25.76  5886.5   31.87  6156.5    31.2  6406.5   36.82
  6526.5   32.83  6596.5   40.64  6646.5   42.34  6885.3   40.31  7185.3   43.66
#Mann= 4 ,-1 , 0
  4538.8     .05       0  4940.2     .04       0  5100.2     .12       0
  6156.5      .1       0
#XS Ineff= 2 , 0
                            5526           40.96
Permanent Ineff=
       F       F
Bank Sta=4940.2,5110.2
XS Rating Curve= 0
Exp/Cntr=.3,.1

Chan Stop Cuts=-1